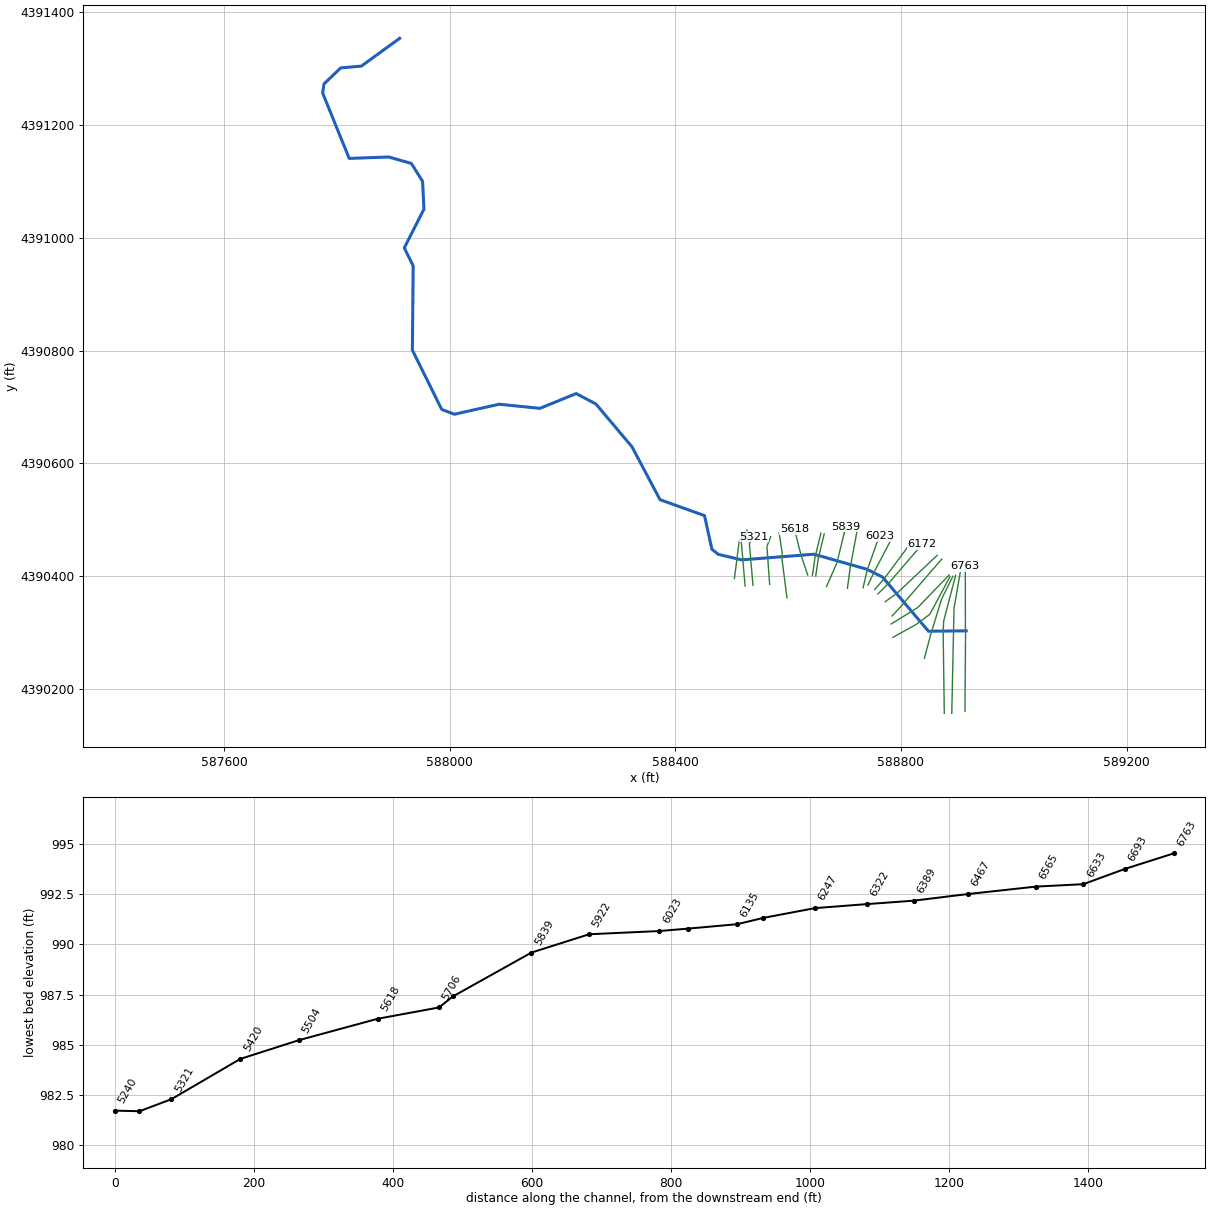
--- BurroughsRun.prj (project) ---

Proj Title=Burroughs Run
Current Plan=p01
Default Exp/Contr=0.3,0.1
English Units
Geom File=g01
Geom File=g02
Flow File=f01
Flow File=f02
Plan File=p01
Plan File=p02
Y Axis Title=Elevation
X Axis Title(PF)=Main Channel Distance
X Axis Title(XS)=Station
BEGIN DESCRIPTION:
Detailed Study for Burroughs Run
Upper Monongahela Watershed, Monongalia County, WV
Submitted by RAMPP for FEMA Region III
Model date: October 2015
This HEC-RAS model incorporates the HEC-RAS model developed by the Morgantown Utility Board (MUB) for stormwater improvements. The structure modeling was taken directly from the MUB HEC-RAS model.
HEC-RAS version 4.1.0
Vertical Datum: NAVD88 (feet)
Horizontal Datum: NAD_1983_StatePlane_West_Virginia_North_FIPS_4701_Feet
END DESCRIPTION:
DSS Export Rating Curves= 0
DSS Export Rating Curve Sorted= 0
DSS Export Volume Flow Curves= 0
DXF Filename=..\..\..\..\..\DETAILED\Basin_HUC_Stream\HEC-RAS\Burroughs Run\BurroughsRun.
DXF OffsetX= 0
DXF OffsetY= 0
DXF ScaleX= 1
DXF ScaleY= 10

--- BurroughsRun.p01 (plan) ---

Plan Title=Burroughs Run - Multiprofile
Program Version=4.10
Short Identifier=Multiprofile
Geom File=g01
Flow File=f01
Subcritical Flow
K Sum by GR= 0
Std Step Tol= 0.01
Critical Tol= 0.01
Num of Std Step Trials= 20
Max Error Tol= 0.3
Flow Tol Ratio= 0.001
Split Flow NTrial= 30
Split Flow Tol= 0.02
Split Flow Ratio= 0.02
Log Output Level= 0
Friction Slope Method= 1
Unsteady Friction Slope Method= 2
Unsteady Bridges Friction Slope Method= 1
Parabolic Critical Depth
Global Vel Dist= 0 , 0 , 0
Global Log Level= 0
CheckData=True
Encroach Param=-1 ,0,0, 0
Computation Interval=1HOUR
Output Interval=1HOUR
Run HTab= 0
Run UNet= 0
Run PostProcess= 0
Run WQNet= 0
UNET Theta= 1
UNET Theta Warmup= 1
UNET ZTol= 0.02
UNET ZSATol= 0.05
UNET MxIter= 20
UNET MaxInSteps= 0
UNET DtIC= 0
UNET DtMin= 0
UNET MaxCRTS= 20
UNET WFStab= 2
UNET SFStab= 1
UNET WFX= 1
UNET SFX= 1
UNET DSS MLevel= 4
UNET DZMax Abort= 98.43
UNET Convert EG Bridges= 0
UNET Use Existing IB Tables=-1
UNET Froude Reduction=False
UNET Froude Limit= 1
UNET Froude Power= 10
UNET Time Slicing=0,0, 5
UNET Junction Losses=0
Instantaneous Interval=1HOUR
DSS File=dss
Write IC File= 0
Write IC File at Sim End=0
Echo Input=False
Echo Parameters=False
Echo Output=False
Write Detailed= 0
WQ AD Non Conservative
WQ ULTIMATE=-1
WQ Max Comp Step=1HOUR
WQ Output Interval=15MIN
WQ Output Selected Increments= 0
WQ Output face flow=0
WQ Output face velocity=0
WQ Output face area=0
WQ Output face dispersion=0
WQ Output cell volume=0
WQ Output cell surface area=0
WQ Output cell continuity=0
WQ Output cumulative cell continuity=0
WQ Output face conc=0
WQ Output face dconc_dx=0
WQ Output face courant=0
WQ Output face peclet=0
WQ Output face adv mass=0
WQ Output face disp mass=0
WQ Output cell mass=0
WQ Output cell source sink temp=0
WQ Output cell source sink nsm=0
WQ Output MaxMinRange=-1
WQ Daily Max Min Mean=-1
WQ Daily Range=0
WQ Daily Time=0
WQ Create Restart=0
WQ Fixed Restart=0
WQ System Summary=0
WQ Use Fixed Temperature=0
Sorting and Armoring Iterations= 10
XS Update Threshold= 0.02
Hydraulics Update Threshold= 0.02
Energy Slope Method= 1
Volume Change Method= 0
XS Weighting Method= 0
Number of US Weighted Cross Sections= 1
Number of DS Weighted Cross Sections= 1
Upstream XS Weight=0.25
Main XS Weight=0.5
Downstream XS Weight=0.25
Number of DS XS's Weighted with US Boundary= 1
Upstream Boundary Weight= 1
Weight of XSs Associated with US Boundary= 0
Number of US XS's Weighted with DS Boundary= 1
Downstream Boundary Weight= 0.5
Weight of XSs Associated with DS Boundary= 0.5
Sediment Output Level= 4
Mass or Volume Output= 0
Output Increment Type= 1
Profile and TS Output Increment= 10
XS Output Flag= 0
XS Output Increment= 10
Disregard all LS=0
Disregard all Conn=0
Disregard all Breaches=0
Disregard all Pumps=0

--- BurroughsRun.p02 (plan) ---

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Plan Title=Burroughs Run - Floodway
Short Identifier=Floodway
Geom File=g01
Flow File=f02
Encroach Param=-1 ,0,0, 2
Encroach River=Burroughs Run
Encroach Reach=Reach 1
Encroach Node=6763
       1   -8.55   11.35
Encroach Node=6693
       1     -12      10
Encroach Node=6633
       1  -12.35   12.63
Encroach Node=6565
       1  -12.65   23.64
Encroach Node=6467
       1  -16.04      23
Encroach Node=6389
       1   -9.58    8.47
Encroach Node=6322
       1   -8.33      25
Encroach Node=6247
       1   -12.8      60
Encroach Node=6172
       1   -9.09    38.9
Encroach Node=6135
       1     -12    27.9
Encroach Node=6064
       1   -12.5   22.31
Encroach Node=6023
       1  -11.61      10
Encroach Node=5922
       1     -10     9.4
Encroach Node=5839
       1   -8.89      15
Encroach Node=5726
       1  -17.22      33
Encroach Node=5706
       1     -20    25.5
Encroach Node=5618
       1     -20    28.5
Encroach Node=5504
       1     -12    12.5
Encroach Node=5420
       1  -24.52     6.5
Encroach Node=5321
       1     -25      16
Encroach Node=5275
       1     -15    12.6
Encroach Node=5240
       1   -11.5   22.02
Encroach Node=5127
       1     -10      13
Encroach Node=5001
       1     -15      15
Encroach Node=4950
       1     -25      20
Encroach Node=4903
       1     -25      20
Encroach Node=4896
       1     -25      20
Encroach Node=4579
       1  -14.55   20.49
Encroach Node=4439
       1  -63.83   19.35
Encroach Node=4310
       1  -37.79   13.08
Encroach Node=4227
       1    -4.6   39.68
Encroach Node=4094
       1     -25      25
Encroach Node=3986
       1  -11.16      30
Encroach Node=3919
       1     -35      35
Encroach Node=3851
       1     -11      40
Encroach Node=3770
       1    -9.5      22
Encroach Node=3689
       1  -29.47      20
Encroach Node=3636
       1     -40      20
Encroach Node=3553
       1     -40   69.57
Encroach Node=3464
       1     -29   80.42
Encroach Node=3290
       1     -47      53
Encroach Node=3002
       1     -25     100
Encroach Node=2857
       1  -18.83      36
Encroach Node=2795
       1   -11.5      50
Encroach Node=2752
       1   -11.5      80
Encroach Node=2715
       1     -30      90
Encroach Node=2656
       1     -14   12.55
Encroach Node=2591
       1     -12      30
Encroach Node=2475
       1   -15.3      23
Encroach Node=2421
       1   -18.5      25
Encroach Node=2364
       1  -20.28   12.24
Encroach Node=2318
       1     -40      14
Encroach Node=2273
       1     -20   11.19
Encroach Node=2164
       1  -17.62   17.55
Encroach Node=2069
       1  -20.41   13.42
Encroach Node=2015
       1  -36.76   11.76
Encroach Node=1885
       1  -12.27   15.06
Encroach Node=1724
       1     -15      16
Encroach Node=1425
       1     -60    18.3
Encroach Node=1209
       1     -20     120
Encroach Node=981
       1     -20     150
Encroach Node=890
       1     -33      35
Encroach Node=792
       1     -22      33
Encroach Node=706
       1  -20.09    8.43
Encroach Node=577
       1     -17      15
Encroach Node=301
       1  -34.81   16.34
Encroach Node=214
       1   -19.6    20.9
Encroach Node=109
       1  -46.53   10.62
Encroach Node=8
       1  -42.72   10.75

--- BurroughsRun.f01 (steady flow) ---

Flow Title=Burroughs Run - Multiprofile
Program Version=4.10
Number of Profiles= 6
Profile Names=10PCT,4PCT,2PCT,1PCT,1PCT_PLUS,0.2PCT
River Rch & RM=Burroughs Run,Reach 1         ,6763
     421     551     662     765    1013    1018
River Rch & RM=Burroughs Run,Reach 1         ,6064
     426     560     672     778    1031    1037
River Rch & RM=Burroughs Run,Reach 1         ,5618
     451     594     714     827    1096    1105
River Rch & RM=Burroughs Run,Reach 1         ,5127
     465     614     738     857    1135    1146
River Rch & RM=Burroughs Run,Reach 1         ,4896
     510     676     815     947    1255    1269
River Rch & RM=Burroughs Run,Reach 1         ,3986
     536     715     868    1012    1341    1362
River Rch & RM=Burroughs Run,Reach 1         ,3689
     560     753     917    1073    1422    1455
River Rch & RM=Burroughs Run,Reach 1         ,2715
     556     758     930    1095    1451    1497
River Rch & RM=Burroughs Run,Reach 1         ,2015
     516     695     850     999    1324    1363
River Rch & RM=Burroughs Run,Reach 1         ,890
     519     700     856    1006    1333    1373
Boundary for River Rch & Prof#=Burroughs Run,Reach 1         , 1
Up Type= 0
Dn Type= 3
Dn Slope=0.0063
Boundary for River Rch & Prof#=Burroughs Run,Reach 1         , 2
Up Type= 0
Dn Type= 3
Dn Slope=0.0063
Boundary for River Rch & Prof#=Burroughs Run,Reach 1         , 3
Up Type= 0
Dn Type= 3
Dn Slope=0.0063
Boundary for River Rch & Prof#=Burroughs Run,Reach 1         , 4
Up Type= 0
Dn Type= 3
Dn Slope=0.0063
Boundary for River Rch & Prof#=Burroughs Run,Reach 1         , 5
Up Type= 0
Dn Type= 3
Dn Slope=0.0063
Boundary for River Rch & Prof#=Burroughs Run,Reach 1         , 6
Up Type= 0
Dn Type= 3
Dn Slope=0.0063
DSS Import GetInterval= 0
DSS Import GetPeak= 0
DSS Import FillOption= 0

--- BurroughsRun.f02 (steady flow) ---

Flow Title=Burroughs Run - Floodway
Program Version=4.10
Number of Profiles= 2
Profile Names=1PCT,Floodway
River Rch & RM=Burroughs Run,Reach 1         ,6763
     765     765
River Rch & RM=Burroughs Run,Reach 1         ,6064
     778     778
River Rch & RM=Burroughs Run,Reach 1         ,5618
     827     827
River Rch & RM=Burroughs Run,Reach 1         ,5127
     857     857
River Rch & RM=Burroughs Run,Reach 1         ,4896
     947     947
River Rch & RM=Burroughs Run,Reach 1         ,3986
    1012    1012
River Rch & RM=Burroughs Run,Reach 1         ,3689
    1073    1073
River Rch & RM=Burroughs Run,Reach 1         ,2715
    1095    1095
River Rch & RM=Burroughs Run,Reach 1         ,2015
     999     999
River Rch & RM=Burroughs Run,Reach 1         ,890
    1006    1006
Boundary for River Rch & Prof#=Burroughs Run,Reach 1         , 1
Up Type= 0
Dn Type= 3
Dn Slope=0.0063
Boundary for River Rch & Prof#=Burroughs Run,Reach 1         , 2
Up Type= 0
Dn Type= 3
Dn Slope=0.0063
DSS Import GetInterval= 0
DSS Import GetPeak= 0
DSS Import FillOption= 0

--- BurroughsRun.g01 (geometry) ---

Geom Title=Burroughs Run
Program Version=4.10

River Reach=Burroughs Run   ,Reach 1
Reach XY= 30
588915.5904303894390303.41587562588848.7447415634390302.66911561
588767.311324556 4390398.6933088588739.8214122174390412.49465297
588645.757083054 4390439.1920853 588517.610017474390429.16416517
588476.236464959 4390438.9970133588464.9070488194390448.00994941
588451.7244486564390507.62883014588372.9305996824390535.83502249
588323.1872390684390629.63112765588259.4230782794390705.30077659
588224.3649818464390723.95453682588160.0735170524390697.76002449
588087.7079001574390705.03560058 588008.597059184390687.30843236
  587985.97480294390695.77577647587933.9850662574390800.94701777
587935.4420102754390950.17405161587919.6990900814390982.18719601
587954.4920105114391050.84644486587952.1084744814391100.05945347
587932.1318822344391131.81046986587892.181745741  4391143.188654
587822.0045928744391140.73501397587774.931280292 4391256.6717914
587777.354440322 4391272.7682796587807.0236726884391301.14820795
587843.4808011394391304.24802399587911.496921979 4391353.5311366

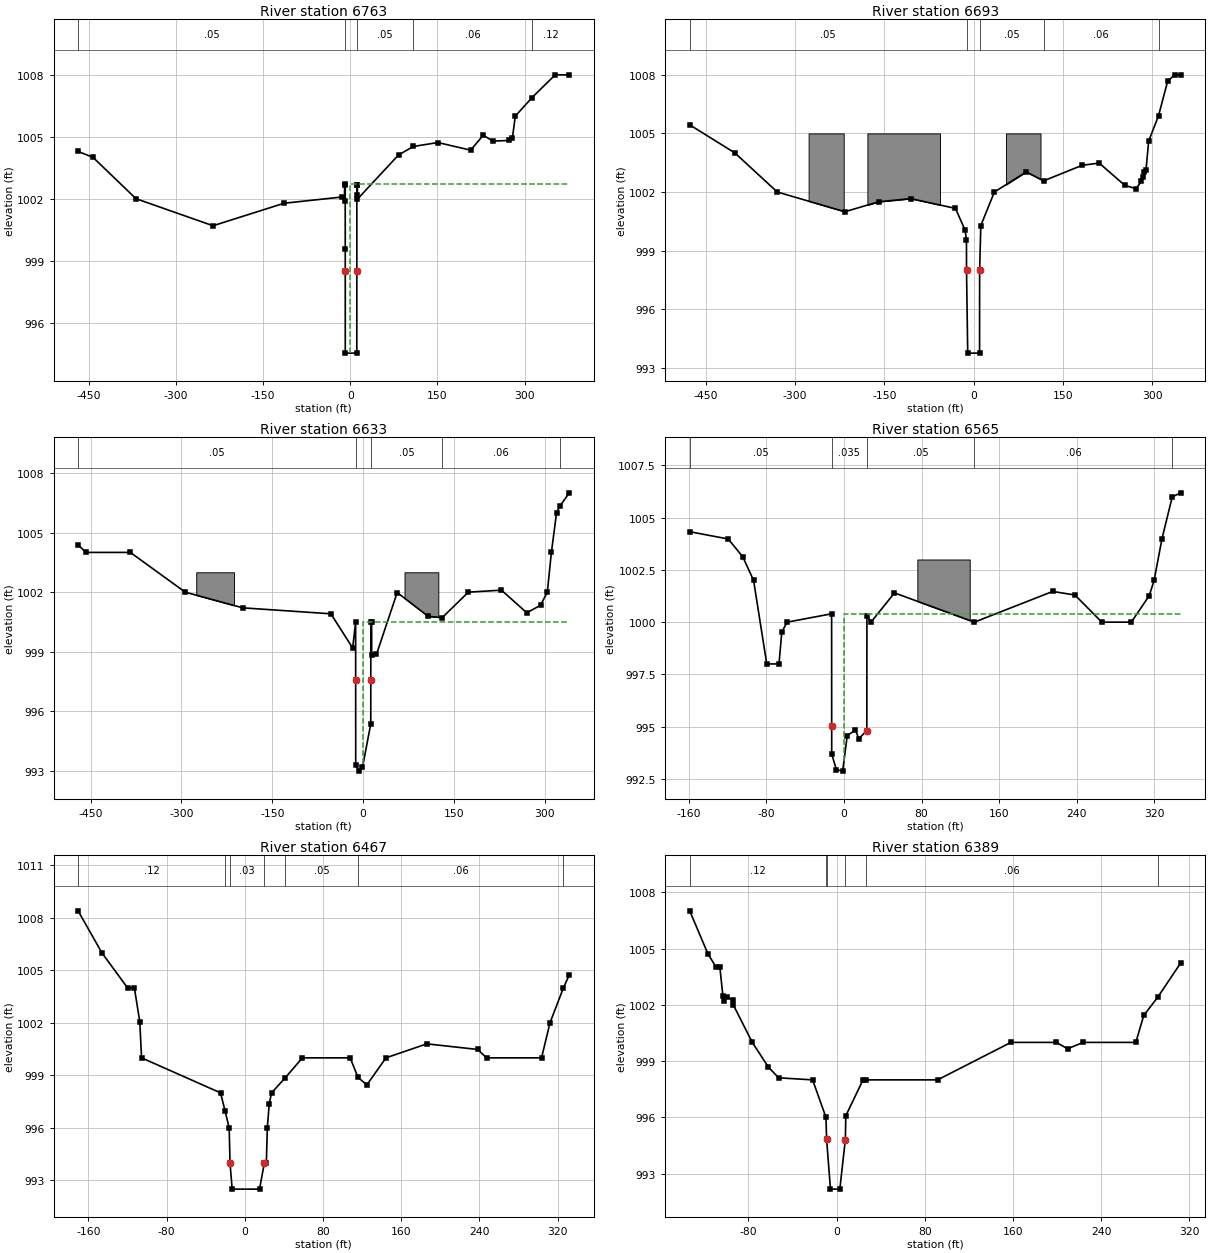
Type RM Length L Ch R = 1 ,6763    ,70.96,70,68.9
XS GIS Cut Line= 5
588913.3684383624390160.75728186588914.4657183754390300.01430758
588914.3102703734390303.35796362588914.1517743714390306.70466766
588914.0054703694390418.14564504
#Sta/Elev= 30
-467.881 1004.29-442.159    1004 -368.34    1002-235.892 1000.69-113.714 1001.78
   -14.6 1002.08    -9.8 1001.89    -9.7 1002.67    -8.6  1002.7   -8.55 999.541
  -8.545   998.5    -8.5  994.52    11.3  994.52   11.35   998.5   11.37 1002.18
    11.4 1002.67    12.3 1002.67    12.4 1001.98  83.104 1004.12 108.563 1004.53
 150.787 1004.72 207.087 1004.35 228.806 1005.08 244.948 1004.79 273.261 1004.82
  278.74 1004.92 283.858    1006 312.336 1006.89 352.428    1008 376.608    1008
#Mann= 5 ,-1 , 0
-467.881     .05       0  -8.545     .03       0   11.35     .05       0
 108.563     .06       0 312.336     .12       0
#XS Ineff= 2 , 0
       0    -8.6  1002.7    11.4       0 1002.67
Permanent Ineff=
       F       F
Bank Sta=-8.545,11.35
XS Rating Curve= 0 ,0
Exp/Cntr=0.3,0.1

Type RM Length L Ch R = 1 ,6693    ,59.08,60,59.42
XS GIS Cut Line= 3
588890.0238060734390157.10577781588893.9923021224390343.10693211
 588905.105310264390407.40144491
#Sta/Elev= 30
-476.673 1005.44 -400.82    1004-329.659    1002-216.175 1000.99-159.547  1001.5
-105.315 1001.66 -30.512 1001.16 -14.337 1000.04 -12.106  999.54     -12     998
     -10  993.75     9.9  993.75      10     998  11.975 1000.28  34.777    1002
  88.222 1003.03 117.323 1002.57 182.349 1003.37 210.728 1003.48 253.707 1002.34
 272.441 1002.17  281.66 1002.55 284.744 1002.75  286.22 1003.01 289.239 1003.12
 293.766 1004.61 310.335 1005.91 325.722 1007.69 337.927    1008 347.769    1008
#Mann= 5 ,-1 , 0
-476.673     .05       0     -12     .03       0      10     .05       0
 117.323     .06       0 310.335     .12       0
#Block Obstruct= 3 ,-1
-277.067-218.143    1005-178.379 -56.562    1005  54.167 112.172    1005
Bank Sta=-12,10
XS Rating Curve= 0 ,0
Exp/Cntr=0.3,0.1

Type RM Length L Ch R = 1 ,6633    ,75.61,68,60.83
BEGIN DESCRIPTION:
Channel from MUB HEC-RAS
END DESCRIPTION:
XS GIS Cut Line= 5
588876.7497659094390157.26732181588874.7868538854390297.73440355
588874.738085884 4390301.5565956588875.6921098964390320.78033184
588896.8604701584390401.74130884
#Sta/Elev= 30
-470.735 1004.38 -457.71    1004-384.449    1004-293.898    1002-198.819 1001.21
 -53.314 1000.91   -17.3  999.19   -12.4  1000.5  -12.35   997.6   -12.3  993.29
    -7.1  992.99    -1.1  993.18    12.6  995.37   12.63   997.6    12.7 1000.48
      14  1000.5    14.1  998.86  22.014  998.87  56.234 1001.98  107.48 1000.78
 130.676 1000.72 173.688    1002 228.412  1002.1 270.308 1000.96 292.913 1001.34
 304.134    1002  310.86    1004 319.423    1006 324.738 1006.32 340.387    1007
#Mann= 5 ,-1 , 0
-470.735     .05       0  -12.35     .03       0   12.63     .05       0
 130.676     .06       0 324.738     .12       0
#XS Ineff= 2 , 0
       0   -12.4  1000.5      14       0  1000.5
Permanent Ineff=
       F       F
#Block Obstruct= 2 ,-1
-275.656-213.255    1003  68.307 124.147    1003
Bank Sta=-12.35,12.63
XS Rating Curve= 0 ,0
Exp/Cntr=0.3,0.1

Type RM Length L Ch R = 1 ,6565    ,115.98,98,80.64
BEGIN DESCRIPTION:
Channel from MUB HEC-RAS
END DESCRIPTION:
XS GIS Cut Line= 5
588841.5606054744390254.89781102588853.4417096214390299.99906758
588855.2735576444390305.22943564 588871.988789854390359.93798832
588892.0964460994390400.15330082
#Sta/Elev= 30
-159.022 1004.33-119.324 1003.98-104.298 1003.13 -93.143    1002  -79.56     998
 -66.962     998 -64.042  999.53 -58.596    1000   -12.7  1000.4  -12.62 995.032
   -12.6  993.69    -7.8  992.94    -1.3  992.87     3.4  994.57    11.9  994.84
    15.3  994.42    23.6  994.81    23.7  1000.3  27.887    1000  52.133  1001.4
 134.482    1000 215.223 1001.47 238.156  1001.3 265.912    1000 296.325    1000
 314.797 1001.27 319.783    1002 327.953    1004 338.517    1006 347.375 1006.19
#Mann= 5 ,-1 , 0
-159.022     .05       0  -12.62    .035       0    23.6     .05       0
 134.482     .06       0 338.517     .12       0
#XS Ineff= 2 , 0
       0   -12.8  1000.4   50.76       0
Permanent Ineff=
       F       F
#Block Obstruct= 2 ,-1
-159.022-110.794    1003  75.689 129.692    1003
Bank Sta=-12.62,23.6
XS Rating Curve= 0 ,0
Exp/Cntr=0.3,0.1

Type RM Length L Ch R = 1 ,6467    ,78.48,78,79.72
BEGIN DESCRIPTION:
Channel from MUB HEC-RAS
END DESCRIPTION:
XS GIS Cut Line= 4
588785.4682607814390291.67497948588826.0493332824390314.23017975
588851.0856055924390332.68581998588886.8051180334390399.36082081
#Sta/Elev= 30
-170.604  1008.4 -146.26    1006-120.013    1004-113.025    1004-107.513 1002.07
-105.676    1000 -24.836     998 -20.243  996.97 -16.043     996 -15.157     994
     -13   992.5      15   992.5      20     994      22     994      23     996
  24.967  997.39  27.362     998  41.273  998.86  58.891    1000 107.776    1000
 115.781  998.88 124.869  998.46  144.39    1000 186.155  1000.8 238.156 1000.48
 247.375    1000 303.576    1000 312.172    1002 325.951    1004 331.923 1004.74
#Mann= 7 ,-1 , 0
-170.604     .12       0 -20.243     .09       0 -15.157     .03       0
      20     .09       0  41.273     .05       0 115.781     .06       0
 325.951     .12       0
#XS Ineff= 2 , 0
       0                   58.89       0
Permanent Ineff=
       F       F
Bank Sta=-15.157,20
XS Rating Curve= 0 ,0
Exp/Cntr=0.3,0.1

Type RM Length L Ch R = 1 ,6389    ,59.22,67,75.47
BEGIN DESCRIPTION:
Channel from MUB HEC-RAS
END DESCRIPTION:
XS GIS Cut Line= 3
588782.5604687454390315.48595577588829.6551173274390344.59130813
588885.4822860174390402.53378884
#Sta/Elev= 30
-133.202 1007.02-116.765 1004.74-109.121    1004-105.807    1004-103.018 1002.45
-101.804 1002.23 -99.245 1002.41 -94.127 1002.26 -93.635    1002 -76.411    1000
 -61.909  998.69 -52.559  998.11 -21.686     998   -9.58     996      -9  994.85
    -5.5  992.17       3  992.17       8 994.805   8.465  996.09  24.049     998
  26.804     998  91.699     998 158.268    1000 199.311    1000 209.711  999.66
 223.819    1000 271.555    1000  278.74 1001.44 291.306  1002.4 312.402 1004.25
#Mann= 6 ,-1 , 0
-133.202     .12       0   -9.58     .06       0      -9    .045       0
       8     .09       0  26.804     .06       0 291.306     .12       0
#XS Ineff= 2 , 0
       0                      80       0
Permanent Ineff=
       F       F
Bank Sta=-9,8
XS Rating Curve= 0 ,0
Exp/Cntr=0.5,0.3

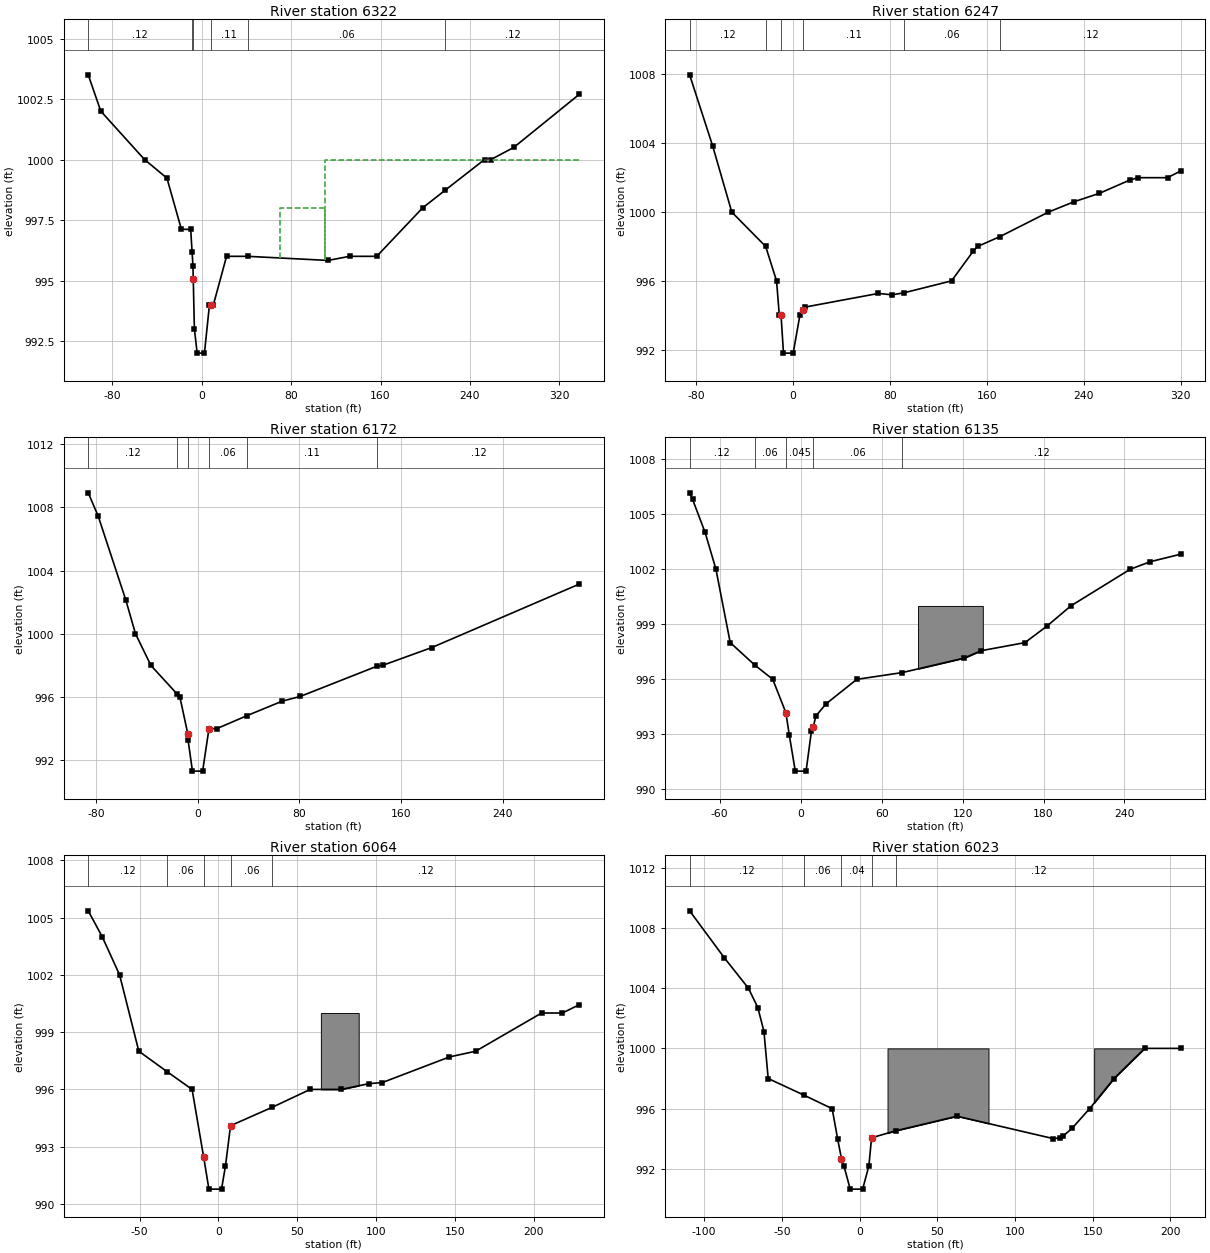
Type RM Length L Ch R = 1 ,6322    ,80.44,75,71.13
BEGIN DESCRIPTION:
Channel from MUB HEC-RAS
END DESCRIPTION:
XS GIS Cut Line= 5
588784.1454287654390329.77497995588803.643485005 4390350.6476842
588805.0333730234390352.55573223 588806.420213044390354.46378025
588872.2539658534390430.58148519
#Sta/Elev= 26
-101.444  1003.5 -90.223    1002 -51.083    1000 -31.037  999.23 -18.143  997.12
  -9.777  997.11   -8.53  996.16  -7.743  995.58    -7.5 995.076    -6.5     993
      -4     992     2.5     992       7     994   8.301     994  10.531     994
  22.277     996  41.306     996 112.992  995.83 132.283     996 156.594     996
 197.605     998 218.045  998.74 253.018    1000 258.825    1000 279.167  1000.5
 337.927  1002.7
#Mann= 6 ,-1 , 0
-101.444     .12       0   -8.53     .11       0    -7.5    .045       0
   8.301     .11       0  41.306     .06       0 218.045     .12       0
#XS Ineff= 2 ,-1
      70     110     998     110 337.927    1000
Permanent Ineff=
       F       F
Bank Sta=-7.5,8.301
XS Rating Curve= 0 ,0
Exp/Cntr=0.3,0.1

Type RM Length L Ch R = 1 ,6247    ,71.38,75,77.63
XS GIS Cut Line= 5
588771.9747646144390354.90878826 588791.073532854390368.82290843
588792.9571968734390370.36214845588794.8439088974390371.90443647
588864.0517977524390437.19564527
#Sta/Elev= 26
 -85.499 1007.98 -66.503 1003.85 -50.689    1000 -22.703     998 -13.714     996
  -11.45  994.01 -10.007     994      -8   991.8       0   991.8   5.545     994
   8.465  994.31  10.072  994.48  70.308  995.27  81.726  995.19  91.699  995.31
 130.774     996 148.524  997.71 152.231     998 170.932  998.58 210.794    1000
  231.89  1000.6 252.887 1001.09 278.215 1001.87  284.81    1002 309.186    1002
 320.144  1002.4
#Mann= 6 ,-1 , 0
 -85.499     .12       0 -22.703     .11       0 -10.007    .045       0
   8.465     .11       0  91.699     .06       0 170.932     .12       0
#XS Ineff= 2 , 0
       0                     110       0
Permanent Ineff=
       F       F
Bank Sta=-10.007,8.465
XS Rating Curve= 0 ,0
Exp/Cntr=0.3,0.1

Type RM Length L Ch R = 1 ,6172    ,35.11,37,39.21
BEGIN DESCRIPTION:
Channel from MUB HEC-RAS
END DESCRIPTION:
XS GIS Cut Line= 5
588759.0116204544390368.66746043588775.7359966614390385.44670063
588777.5251726834390387.20844466588779.3143487054390388.97018868
588837.3269334224390456.51082151
#Sta/Elev= 20
 -85.958 1008.92  -78.15 1007.45 -56.463 1002.15 -48.786    1000  -36.68     998
 -16.076  996.19 -13.878     996  -7.612  993.65    -7.5  993.31      -4  991.31
       4  991.31       9     994   15.19     994  38.878  994.82  66.634  995.74
  80.906  996.04 141.437  997.96 145.472     998 184.219  999.13 300.328 1003.15
#Mann= 6 ,-1 , 0
 -85.958     .12       0 -16.076     .06       0  -7.612    .045       0
       9     .06       0  38.878     .11       0 141.437     .12       0
Bank Sta=-7.612,9
XS Rating Curve= 0 ,0
Exp/Cntr=0.3,0.1

Type RM Length L Ch R = 1 ,6135    ,63.87,71,75.78
BEGIN DESCRIPTION:
Channel from MUB HEC-RAS
END DESCRIPTION:
XS GIS Cut Line= 3
588753.4551163854390376.60750053588771.1457086044390396.92851678
588821.1877732224390464.44781361
#Sta/Elev= 25
 -82.316 1006.16 -80.118  1005.8 -70.833    1004 -62.828    1002 -52.231     998
 -34.219  996.79 -20.702     996 -10.958  994.18    -8.5  992.99      -4     991
       4     991       8   993.2   9.318  993.41  11.253     994  18.701  994.66
  41.601     996  75.427  996.37 121.227  997.16 133.793  997.56  166.24     998
  182.71  998.91  200.23    1000 244.324    1002 259.219 1002.41 281.791 1002.82
#Mann= 5 ,-1 , 0
 -82.316     .12       0 -34.219     .06       0 -10.958    .045       0
   9.318     .06       0  75.427     .12       0
#Block Obstruct= 1 ,-1
      87     135    1000
Bank Sta=-10.958,9.318
XS Rating Curve= 0 ,0
Exp/Cntr=0.3,0.1

Type RM Length L Ch R = 1 ,6064    ,35.91,41,44.73
BEGIN DESCRIPTION:
Channel from MUB HEC-RAS
END DESCRIPTION:
XS GIS Cut Line= 5
588741.4703802374390384.66336462 588751.385524364390405.36538088
588752.327356371 4390407.3618209588753.2691883834390409.35826093
588784.6757807714390469.21183767
#Sta/Elev= 21
 -82.546 1005.35  -73.72    1004 -62.664    1002 -50.459     998 -32.546  996.93
 -16.667     996  -9.318  992.45      -6  990.78       2  990.78     4.5     992
    7.71   994.1  34.285  995.07  58.235     996  77.887     996  95.374   996.3
 104.003  996.36 146.522   997.7 163.189     998 204.987    1000 218.176    1000
 229.003 1000.44
#Mann= 5 ,-1 , 0
 -82.546     .12       0 -32.546     .06       0  -9.318     .04       0
    7.71     .06       0  34.285     .12       0
#Block Obstruct= 1 ,-1
      65      89    1000
Bank Sta=-9.318,7.71
XS Rating Curve= 0 ,0
Exp/Cntr=0.3,0.1

Type RM Length L Ch R = 1 ,6023    ,98.04,101,105.02
BEGIN DESCRIPTION:
Channel from MUB HEC-RAS
END DESCRIPTION:
XS GIS Cut Line= 5
 588732.817108134390379.78046856588739.8823722174390409.85203694
588740.6047482264390412.17766096588741.3271242354390414.50328499
588761.657284487 4390471.5923257
#Sta/Elev= 25
 -109.35 1009.13 -86.942    1006 -71.555    1004 -65.453 1002.71 -61.516 1001.12
 -58.793     998 -35.827   996.9 -17.618     996 -14.108     994 -11.614  992.67
     -10  992.18      -6  990.66       2  990.66       6   992.2   7.743  994.07
  23.655  994.54   62.73   995.5 124.803  994.01 128.707  994.06 131.004  994.18
 136.713  994.69 148.064     996 163.747     998 183.497    1000 206.791    1000
#Mann= 5 ,-1 , 0
 -109.35     .12       0 -35.827     .06       0 -11.614     .04       0
   7.743     .06       0  23.655     .12       0
#XS Ineff= 1 ,-1
   62.73     200   995.5
Permanent Ineff=
       F
#Block Obstruct= 2 ,-1
      18      83    1000     151     194    1000
Bank Sta=-11.614,7.743
XS Rating Curve= 0 ,0
Exp/Cntr=0.3,0.1

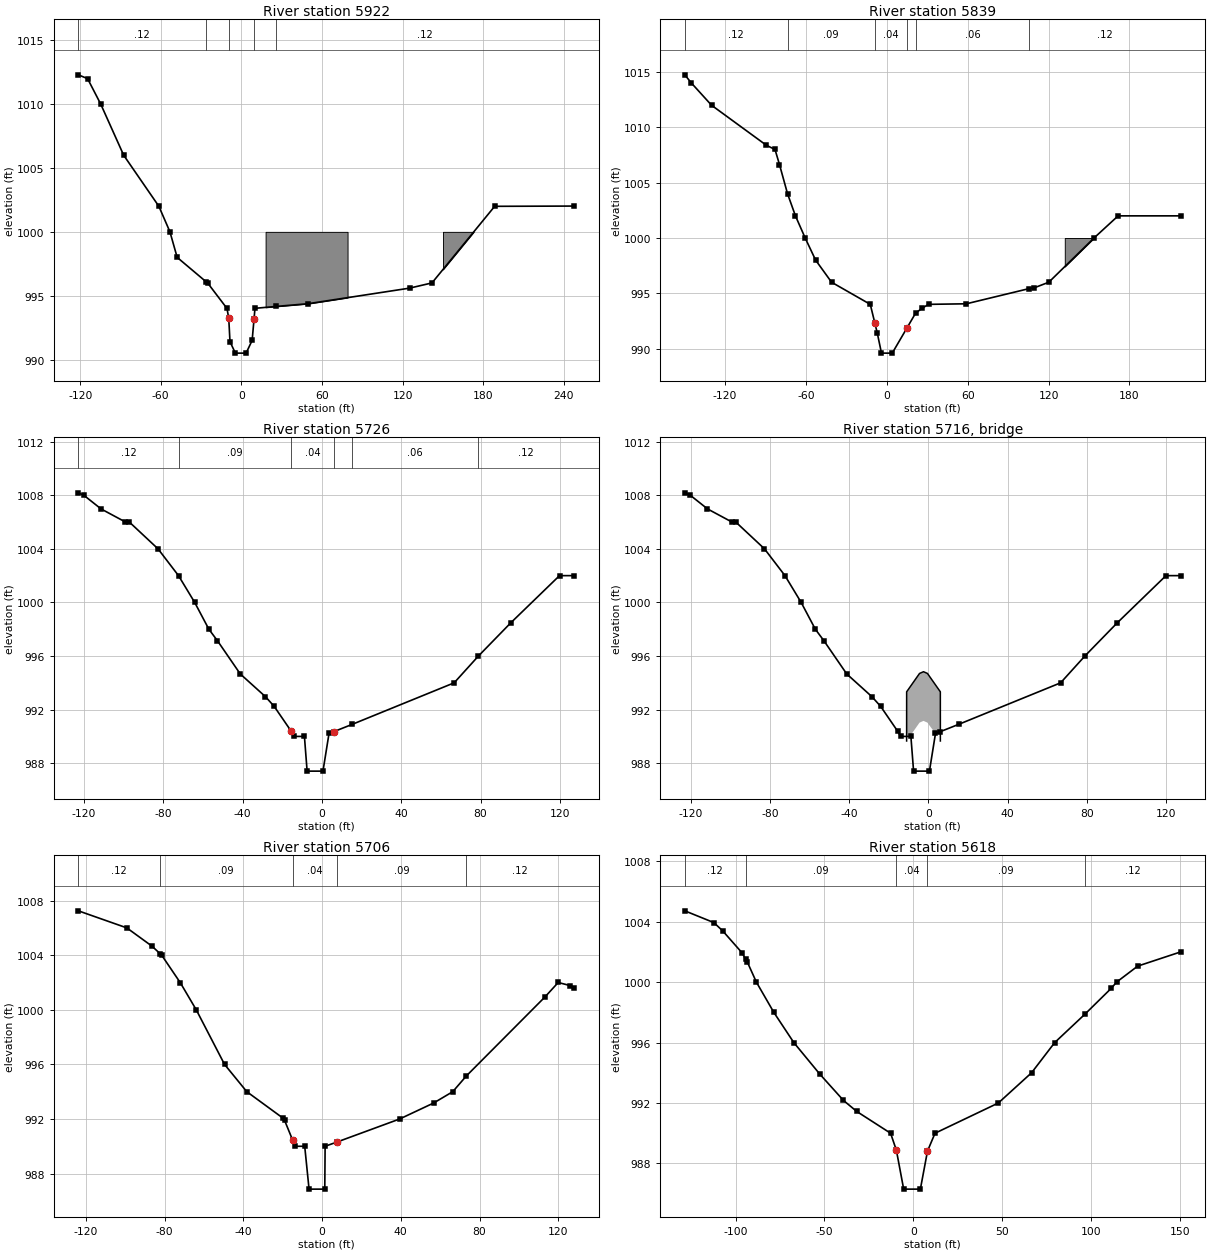
Type RM Length L Ch R = 1 ,5922    ,90.21,83,81.24
BEGIN DESCRIPTION:
Channel from MUB HEC-RAS
END DESCRIPTION:
XS GIS Cut Line= 5
588705.0345877874390378.72281255588709.8412838464390414.22591699
588710.2680038524390416.70089302588710.6916758574390419.17586905
588723.8224600194390489.58466992
#Sta/Elev= 23
-121.358  1012.3-114.468    1012-104.659    1010 -87.598    1006 -61.417    1002
 -53.182    1000 -47.802     998 -26.378   996.1 -25.164     996 -10.728     994
  -9.416  993.23    -8.5   991.4    -4.5   990.5     3.5   990.5       8   991.5
     9.4 993.169  10.105  994.01  26.083  994.16  49.541  994.37 125.131  995.59
 141.831     996 188.484    1002 247.638 1002.02
#Mann= 5 ,-1 , 0
-121.358     .12       0 -26.378     .06       0  -9.416     .04       0
     9.4     .06       0  26.083     .12       0
#Block Obstruct= 2 ,-1
      18      79    1000     150     194    1000
Bank Sta=-9.416,9.4
XS Rating Curve= 0 ,0
Exp/Cntr=0.3,0.1

Type RM Length L Ch R = 1 ,5839    ,107.42,113,113.19
BEGIN DESCRIPTION:
Channel from MUB HEC-RAS
END DESCRIPTION:
XS GIS Cut Line= 3
588667.9952913294390381.89882859588686.5789475594390424.19592511
588702.126795751 4390488.2618379
#Sta/Elev= 27
-149.902 1014.75-144.948    1014-130.052    1012  -89.37 1008.38 -82.972    1008
 -79.659 1006.64 -73.688    1004 -67.815    1002 -60.597    1000 -52.854     998
  -41.01     996 -12.303     994  -8.891   992.3  -7.054  991.38      -4  989.59
       4  989.59      15 991.884   21.26  993.19  25.886  993.63  30.938     994
  58.989  994.05 105.741  995.43 109.022  995.48 120.144     996 153.707    1000
 171.588    1002 217.946    1002
#Mann= 6 ,-1 , 0
-149.902     .12       0 -73.688     .09       0  -8.891     .04       0
      15     .09       0   21.26     .06       0 105.741     .12       0
#Block Obstruct= 1 ,-1
     132     163    1000
Bank Sta=-8.891,15
XS Rating Curve= 0 ,0
Exp/Cntr=0.5,0.3

Type RM Length L Ch R = 1 ,5726    ,19.707,20,19.704
XS GIS Cut Line= 3
588648.8660430934390400.44895682588653.6087311514390432.69679722
588663.8957312784390475.10666974
#Sta/Elev= 26
  -122.9 1008.18-120.144    1008 -111.45 1006.98 -99.114    1006 -97.178    1006
  -82.71    1004 -72.375    1002 -64.206    1000 -57.054     998 -52.723  997.14
 -41.207  994.66 -28.543  992.97 -24.147  992.25 -15.584   990.4 -13.976     990
  -8.858     990    -7.5  987.41      .5  987.41   3.543  990.22   6.037  990.36
  15.223   990.9  66.667     994  78.904     996  95.177  998.47 119.816    1002
 127.198    1002
#Mann= 6 ,-1 , 0
  -122.9     .12       0 -72.375     .09       0 -15.584     .04       0
   6.037     .09       0  15.223     .06       0  78.904     .12       0
Bank Sta=-15.584,6.037
XS Rating Curve= 0 ,0
Exp/Cntr=0.5,0.3

Type RM Length L Ch R = 3 ,5716    ,,,
BEGIN DESCRIPTION:
Pedestrian Bridge (structure dimensions from field reconnaissance)
END DESCRIPTION:
Bridge Culvert--1,0,-1,-1, 0
Deck Dist Width WeirC Skew NumUp NumDn MinLoCord MaxHiCord MaxSubmerge Is_Ogee
6.5,4,2.6,0, 7, 7, , , 0.98, 0, 0,0,,
  -11.01     -11    -4.5    -2.5     -.5       6    6.01
  989.66  993.33   994.7  994.83   994.7  993.33  989.66
          989.66  991.03  991.16  991.03  989.66
  -11.01     -11    -4.5    -2.5     -.5       6    6.01
  989.66  993.33   994.7  994.83   994.7  993.33  989.66
          989.66  991.03  991.16  991.03  989.66
BR Coef=-1 , 0 , 0 ,, 0 ,,,0.8,0,,0,
WSPro=,,,, 1 ,,,, 0 ,,,, 0 ,,,,-1 ,-1 ,-1 , 0 , 0 , 0 , 0 , 0
BC Design=,, 0 ,, 0 ,,,,,,
BC Use User HTab Curves=0
BC User HTab FreeFlow(D)= 0

Type RM Length L Ch R = 1 ,5706    ,74.18,88,100.94
XS GIS Cut Line= 3
588642.9315870194390401.32068483588647.7138990784390433.84284523
588658.0649072064390476.52094176
#Sta/Elev= 26
-123.852 1007.25 -99.213    1006 -86.417 1004.66 -82.382 1004.12 -81.496    1004
 -71.982 1001.97 -63.944    1000 -49.573     996 -38.255     994 -19.849  992.06
 -19.029  991.89     -15 990.464 -13.681     990  -8.825     990   -6.62  986.86
    1.37  986.86   1.542     990     7.5 990.307  39.436     992  56.693  993.17
  66.404     994  73.294  995.15 113.255 1000.94  119.98    1002 126.115 1001.77
 128.084 1001.59
#Mann= 5 ,-1 , 0
-123.852     .12       0 -82.382     .09       0     -15     .04       0
     7.5     .09       0  73.294     .12       0
Bank Sta=-15,7.5
XS Rating Curve= 0 ,0
Exp/Cntr=0.5,0.3

Type RM Length L Ch R = 1 ,5618    ,122.28,114,107.73
XS GIS Cut Line= 3
588634.6928429174390402.24727684588622.391114765 4390439.2896213
588611.0129306254390483.86966985
#Sta/Elev= 26
-128.576 1004.72-112.205 1003.94-107.218 1003.39 -96.358 1001.94 -94.357 1001.52
 -93.307 1001.31 -88.287    1000 -78.478     998 -67.224     996 -52.657  993.92
 -39.272  992.17 -31.791  991.44 -12.762     990    -9.5  988.87    -5.4   986.3
       4   986.3       8 988.816  12.238     990  47.867     992  66.568     994
  79.593     996  96.522  997.87 111.483   999.6 114.403    1000  126.28 1001.06
 150.459    1002
#Mann= 5 ,-1 , 0
-128.576     .12       0 -94.357     .09       0    -9.5     .04       0
       8     .09       0  96.522     .12       0
Bank Sta=-9.5,8
XS Rating Curve= 0 ,0
Exp/Cntr=0.3,0.1

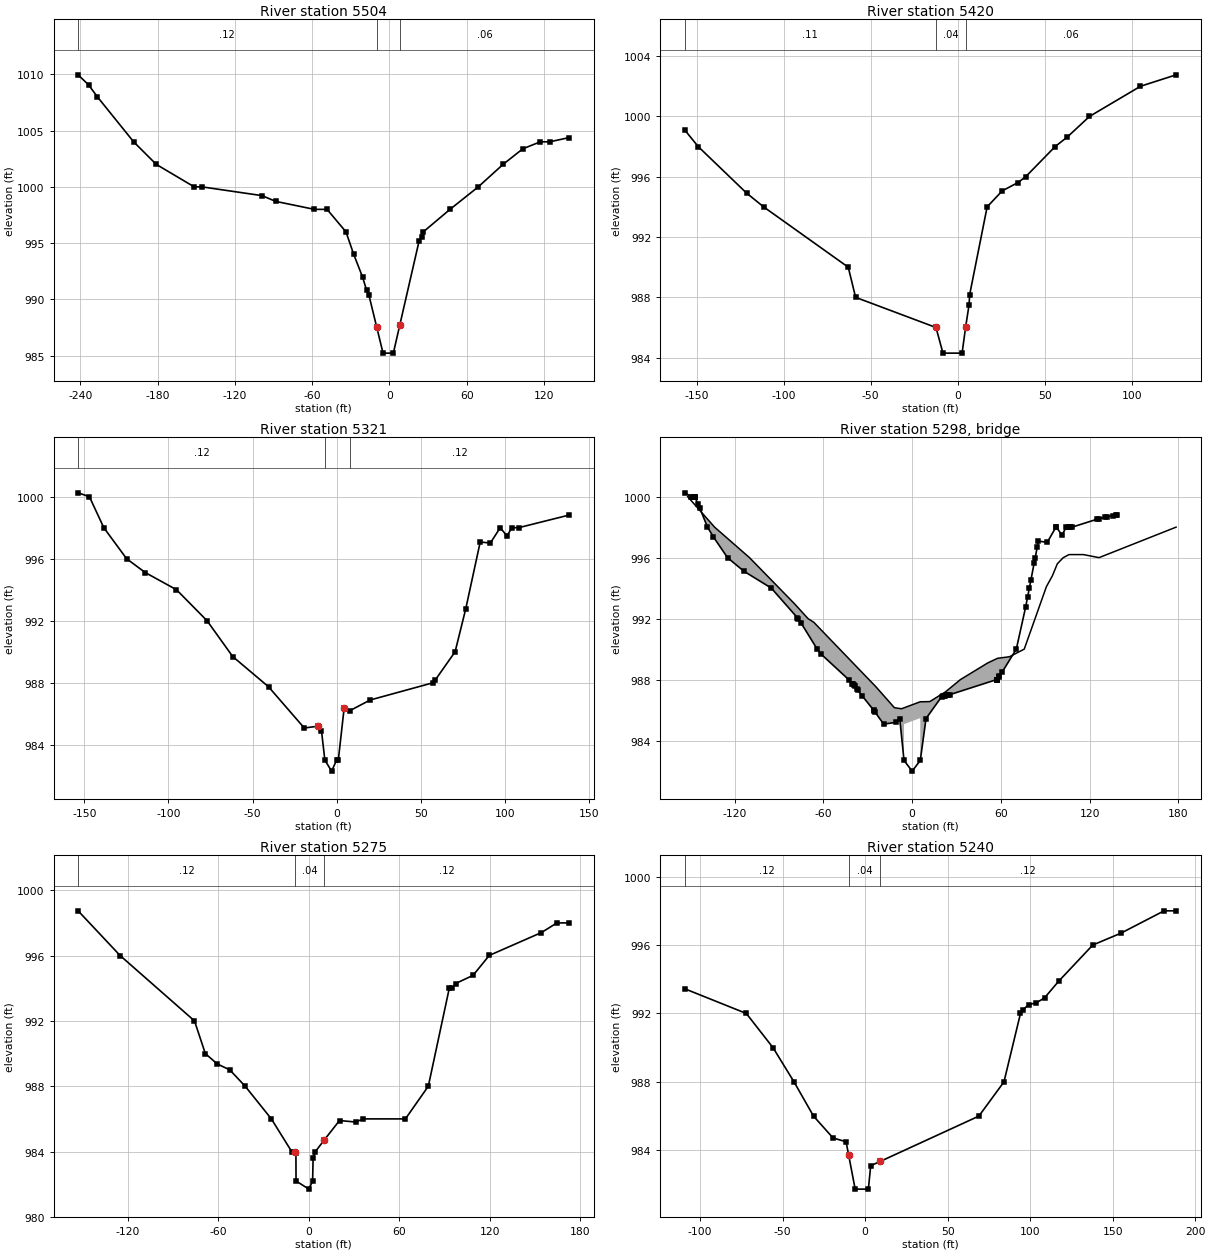
Type RM Length L Ch R = 1 ,5504    ,82.65,84,85.17
BEGIN DESCRIPTION:
Channel from MUB HEC-RAS
END DESCRIPTION:
XS GIS Cut Line= 5
588597.9431064634390361.80336434588589.3233623574390428.98128517
588589.4330903584390434.91574125588589.5428183594390440.85019732
588583.9771702914390477.04519777
#Sta/Elev= 30
-241.699 1009.95-233.596 1009.06-226.772    1008-198.589    1004 -181.07    1002
-151.608    1000-145.669    1000  -98.95  999.22 -88.353  998.71 -58.268     998
 -48.458     998  -33.76     996 -27.756     994 -20.932     992 -17.749  990.81
     -16   990.4     -10  987.58      -5  985.23       3  985.23       8 987.723
      23   995.2  25.033  995.53  26.247     996  46.982     998   68.93    1000
  88.222    1002  103.51 1003.38 117.093    1004 124.442    1004   139.6 1004.38
#Mann= 3 ,-1 , 0
-241.699     .12       0     -10     .04       0       8     .06       0
Bank Sta=-10,8
XS Rating Curve= 0 ,0
Exp/Cntr=0.3,0.1

Type RM Length L Ch R = 1 ,5420    ,98.61,99,99.39
XS GIS Cut Line= 3
588567.1887860834390385.86732464588562.4247620244390453.06962947
588569.0389221064390470.53466969
#Sta/Elev= 21
-156.824  999.09-149.147     998-121.391  994.92-111.549     994 -62.927     990
 -58.694     988   -12.5     986    -8.5   984.3     2.5   984.3     4.5     986
     6.5   987.5   6.857  988.18  16.896     994  25.525  995.06  34.547  995.61
  39.042     996  55.971     998  63.025  998.64  75.722    1000  105.02    1002
 125.492 1002.76
#Mann= 3 ,-1 , 0
-156.824     .11       0   -12.5     .04       0     4.5     .06       0
Bank Sta=-12.5,4.5
XS Rating Curve= 0 ,0
Exp/Cntr=0.5,0.3

Type RM Length L Ch R = 1 ,5321    ,45.938,46,45.938
BEGIN DESCRIPTION:
Channel from MUB HEC-RAS
END DESCRIPTION:
XS GIS Cut Line= 3
588537.6506177184390384.08424462588531.2559136394390458.51640554
588539.5525697424390470.17805368
#Sta/Elev= 30
-153.707 1000.25-146.982    1000-138.419     998-124.869     996-113.812  995.11
  -95.21     994 -77.034     992 -61.778  989.69 -40.486  987.74 -19.226  985.08
     -11   985.2      -9   984.9      -7  983.01      -3   982.3       0  983.01
       1  983.01     4.5   986.4   7.841   986.2  20.013  986.89  57.349     988
  58.727  988.19   70.44     990  76.706  992.74  85.367  997.08  91.404  997.01
  97.244     998  101.28  997.47 104.199     998 108.169     998 138.353  998.82
#Mann= 3 ,-1 , 0
-153.707     .12       0      -7     .04       0   7.841     .12       0
Bank Sta=-11,4.5
XS Rating Curve= 0 ,0
Exp/Cntr=0.5,0.3

Type RM Length L Ch R = 3 ,5298    ,,,
BEGIN DESCRIPTION:
Corvet Avenue (structure from MUB HEC-RAS model)
END DESCRIPTION:
Bridge Culvert--1,0,-1,-1, 0
Deck Dist Width WeirC Skew NumUp NumDn MinLoCord MaxHiCord MaxSubmerge Is_Ogee
15.2,22,2.6,0, 28, 28, , , 0.98, 0, 0,0,,
  -151.8  -133.6    -110   -79.8   -70.4   -66.5   -24.5     -12    -7.2    -5.5
    -5.5     5.5    7.45    11.9    22.6    32.6    51.2    57.8    65.8    75.8
    90.8    94.8    98.2   102.2   106.1   115.8   126.4   178.5
    1000     998     996     993     992  991.76  987.53  986.16  986.09  986.15
  986.15  986.55  986.55  986.56   987.2     988   989.1   989.4   989.5     990
   994.1   994.8   995.6     996   996.2   996.2     996     998
                                                                                
  985.08  985.48
                                                                
  -151.8  -133.6    -110   -79.8   -70.4   -66.5   -24.5     -12    -7.2    -5.5
    -5.5     5.5    7.45    11.9    22.6    32.6    51.2    57.8    65.8    75.8
    90.8    94.8    98.2   102.2   106.1   115.8   126.4   178.5
    1000     998     996     993     992  991.76  987.53  986.16  986.09  986.15
  986.15  986.55  986.55  986.56   987.2     988   989.1   989.4   989.5     990
   994.1   994.8   995.6     996   996.2   996.2     996     998
                                                                                
  985.08  985.48
                                                                
BR Coef=-1 , 1 , 0 ,, 0 ,,,0.8,0,1.2,0,
WSPro=,,,, 1 ,,,, 0 ,,,, 0 ,,,,-1 ,-1 ,-1 , 0 , 0 , 0 , 0 , 0
BR U #Sta/Elev= 81
-153.707 1000.25-149.278    1000-148.327    1000-147.113    1000-146.982    1000
-146.785  999.95-144.783  999.51-143.504  999.23-138.419     998-134.416  997.36
-124.869     996-113.812  995.11  -95.21     994 -77.625  992.06 -77.034     992
  -75.23  991.73 -64.206     990 -61.778  989.69 -42.913     988 -40.486  987.74
 -40.125   987.7   -39.6  987.64 -38.812  987.55 -37.467  987.39 -36.811   987.3
 -33.891  986.95  -26.05     986 -25.689  985.96 -25.394  985.91 -19.226  985.08
     -11   985.2    -8.4  985.45    -5.5   982.7       0     982     5.5   982.7
     9.4  985.45  20.013  986.89  20.801  986.91  21.654  986.93  22.507  986.95
  23.425  986.97  24.377  986.99  25.361  987.01  57.054     988  57.087     988
  57.152     988  57.349     988  58.727  988.19  58.989  988.23  61.089  988.53
   70.44     990  76.706  992.74  78.051   993.4  79.265     994  80.348  994.55
  82.579  995.68  83.235     996  84.646  996.72  85.367  997.08  91.404  997.01
  97.244     998  97.605     998  101.28  997.47 104.199     998 105.873     998
 105.971     998  106.07     998 106.168     998 106.266     998 106.332     998
  106.43     998 106.529     998 106.627     998 108.169     998 125.033  998.52
 126.345  998.55 130.413  998.64 131.988  998.68 135.696  998.76 137.598  998.81
 138.353  998.82
BR U #Mann= 3
-153.707     .12    -8.4    .045     9.4     .12
BR U Banks=-8.4,9.4
BR D #Sta/Elev= 116
-153.051  998.74-151.017  998.55-148.064  998.29-144.882     998-143.898   997.9
-140.223  997.53-125.164     996-115.387  995.21-100.689     994-100.098     994
 -99.902     994 -99.672     994 -98.228  993.85 -76.411     992 -75.853     992
  -73.36  991.35  -72.08  991.02 -71.358  990.82 -68.668     990 -60.827  989.37
 -52.428     989 -42.224     988 -31.594  986.71 -24.869     986 -19.652  985.26
 -16.634  984.82 -11.385     984    -8.4     984    -5.5   982.2       0   981.8
     5.5   982.2     9.4     984  12.664  984.99  15.912  985.37  17.356  985.54
  18.176  985.64  18.734   985.7  19.423  985.79  19.816  985.83  20.046  985.86
   20.21  985.88  20.341   985.9  30.479  985.83  30.971  985.81  36.188     986
  53.773     986  59.875     986   60.63     986  61.319     986  61.975     986
  62.598     986  63.058     986   63.32     986  63.615     986  63.976     986
  64.042     986  64.239  986.03  64.272  986.03  65.289  986.16  66.207  986.27
  67.028  986.38  67.717  986.47   68.34  986.55  79.232     988  82.546  989.39
  83.629  989.87  83.924     990  84.252  990.14   88.55     992   92.52  993.72
  93.143     994   95.21     994   97.31  994.28  97.375  994.29  98.852  994.36
  100.23  994.42 101.969  994.53 103.314  994.58 104.593  994.63 106.726   994.7
 107.021  994.72 107.349  994.74 108.399  994.77  108.76  994.79 108.924  994.79
 110.203  994.94  110.86  995.03 111.352  995.09 112.467  995.22 113.058  995.29
 113.845  995.38 114.468  995.45 115.125  995.53  115.65  995.59 116.306  995.66
 117.028  995.74 117.323  995.77 118.045  995.85 118.832  995.93 118.898  995.94
 119.488     996 119.521     996 119.685  996.01 120.374  996.03 121.588  996.07
 122.769  996.11 123.064  996.12 124.278  996.16 125.459   996.2 126.017  996.23
 130.249  996.37 137.992  996.75 154.265  997.41 158.563  997.67 164.534     998
 172.769     998
BR D #Mann= 3
-153.051     .12    -8.4    .045     9.4     .12
BR D Banks=-8.4,9.4
BC Design=,, 0 ,, 0 ,,,,,,
BC Use User HTab Curves=0
BC User HTab FreeFlow(D)= 0

Type RM Length L Ch R = 1 ,5275    ,40.62,35,29.38
BEGIN DESCRIPTION:
Channel from MUB HEC-RAS
END DESCRIPTION:
XS GIS Cut Line= 3
588523.699921546 4390382.8863806588516.8663054614390462.44222959
588528.1469536014390478.29487778
#Sta/Elev= 30
-153.051  998.74-125.164     996 -75.853     992 -68.668     990 -60.827  989.37
 -52.428     989 -42.224     988 -24.869     986 -11.385     984  -9.088     984
   -8.58  983.92    -8.5   982.2       0   981.7     2.5   982.2   2.822  983.61
   4.331     984  10.302  984.72  20.341   985.9  30.971  985.81  36.188     986
  64.042     986  79.232     988  93.143     994   95.21     994  97.375  994.29
 108.924  994.79 119.685  996.01 154.265  997.41 164.534     998 172.769     998
#Mann= 3 ,-1 , 0
-153.051     .12       0  -9.088     .04       0  10.302     .12       0
Bank Sta=-9.088,10.302
XS Rating Curve= 0 ,0
Exp/Cntr=0.5,0.3

Type RM Length L Ch R = 1 ,5240    ,122.85,113,100.53
BEGIN DESCRIPTION:
Channel from MUB HEC-RAS
END DESCRIPTION:
XS GIS Cut Line= 3
588504.7474573114390396.18480477588513.2117534164390462.06732558
588527.2356015894390481.90980583
#Sta/Elev= 24
-109.186  993.44 -71.949     992 -55.774     990 -43.045     988 -31.234     986
  -19.39  984.72   -11.5   984.5     -10 983.745      -6  981.73       2  981.73
   3.412   983.1   9.186  983.35  68.963     986  84.154     988   94.16     992
  95.768  992.22  99.147  992.52  103.74  992.62 108.727  992.91 117.356  993.89
 137.959     996 154.954  996.69 181.201     998 188.451     998
#Mann= 3 ,-1 , 0
-109.186     .12       0     -10     .04       0   9.186     .12       0
Bank Sta=-10,9.186
XS Rating Curve= 0 ,0
Exp/Cntr=0.3,0.1