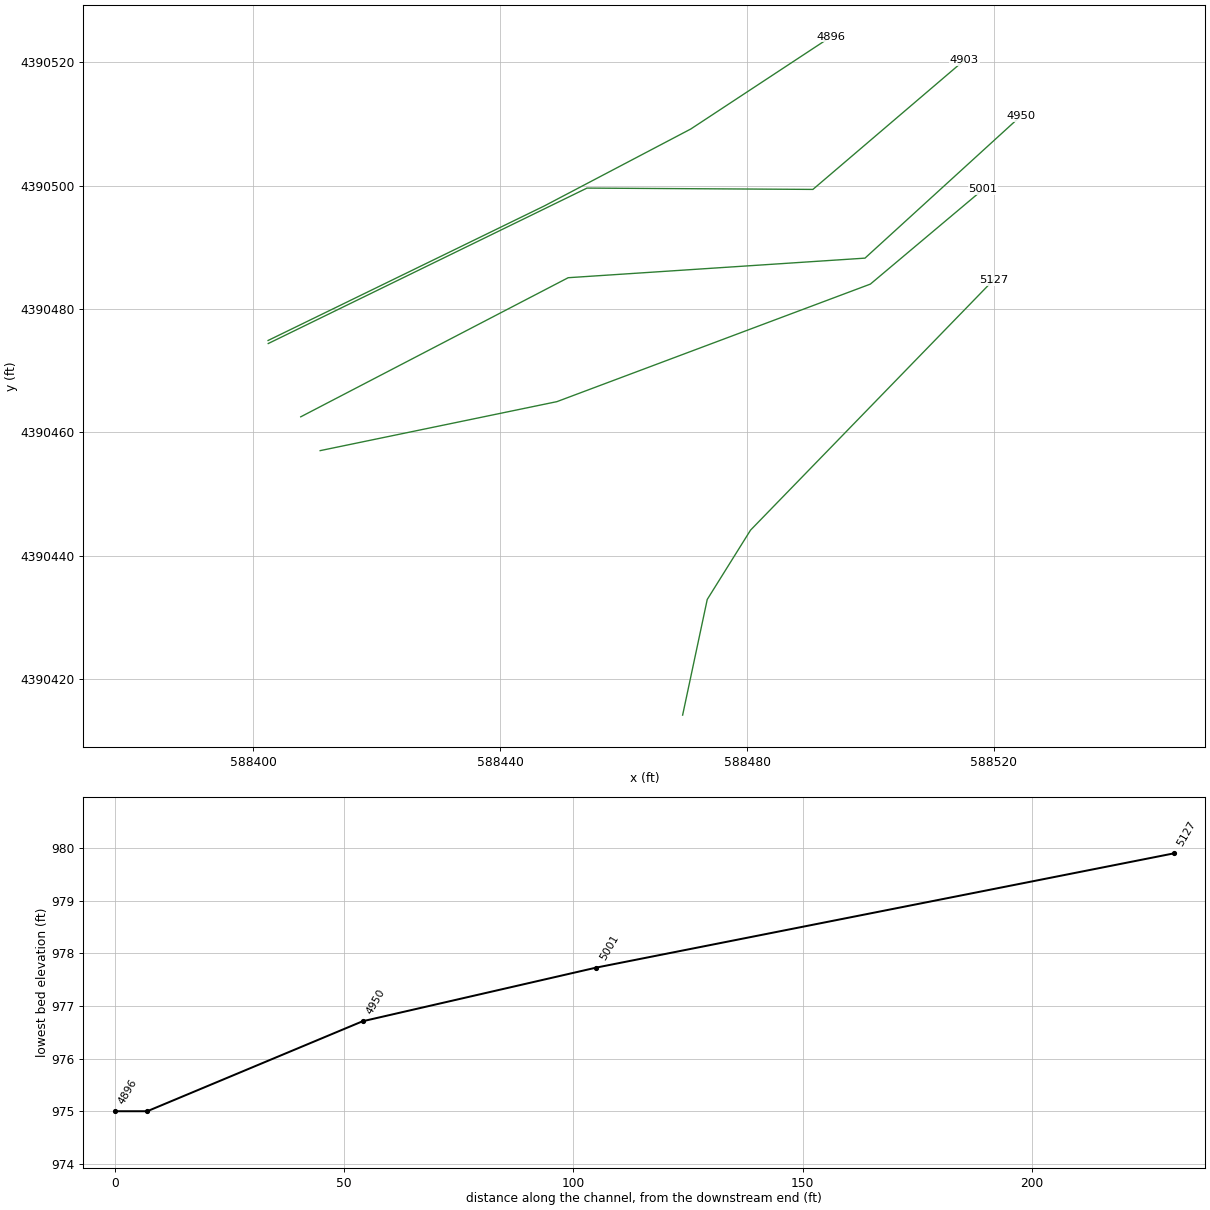
HEC-RAS study BurroughsRun.prj: Burroughs Run

--- BurroughsRun.g01 (geometry) --- (continued)

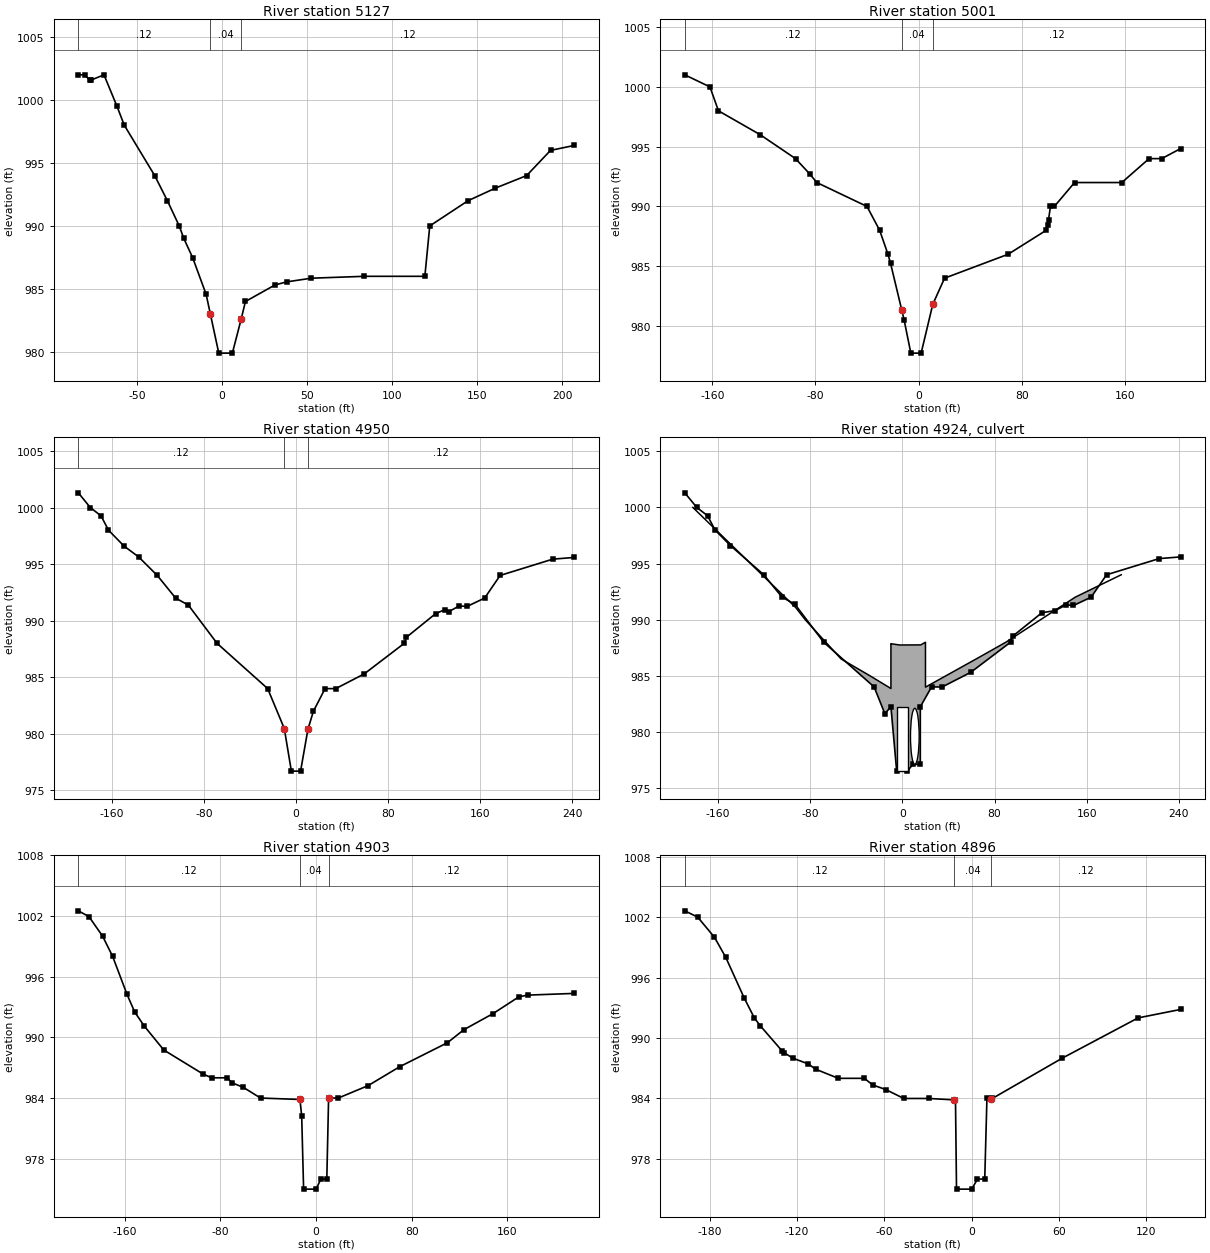
Type RM Length L Ch R = 1 ,5127    ,145.2,126,109.15
BEGIN DESCRIPTION:
Channel from MUB HEC-RAS
END DESCRIPTION:
XS GIS Cut Line= 5
588469.5552488774390414.17714899588473.5450809264390432.92234922
588477.0533289694390438.53981329588480.5615770134390444.15422936
588519.9173534994390484.67738986
#Sta/Elev= 29
 -84.613    1002 -80.873    1002 -77.953 1001.58 -77.362 1001.57 -69.521    1002
 -61.844  999.49 -57.579     998 -39.698     994 -32.218     992 -25.262     990
 -22.572  989.01 -17.356  987.48  -9.416  984.56      -7 983.037      -2   979.9
       6   979.9  11.155  982.59  13.681     984  31.004  985.31  37.992  985.56
  52.461  985.85  83.629     986 119.226     986 122.113     990 144.587     992
 160.663     993 179.101     994 193.143     996 207.054  996.39
#Mann= 3 ,-1 , 0
 -84.613     .12       0      -7     .04       0  11.155     .12       0
Bank Sta=-7,11.155
XS Rating Curve= 0 ,0
Exp/Cntr=0.3,0.1

Type RM Length L Ch R = 1 ,5001    ,58.72,51,43.28
BEGIN DESCRIPTION:
channel invert from mub hec-ras
END DESCRIPTION:
XS GIS Cut Line= 4
588410.8172401514390457.03812552588449.1824166254390464.97816562
588499.9834332534390484.02816585588518.2409534784390499.37179804
#Sta/Elev= 28
 -181.43 1001.01-161.909    1000-155.315     998  -122.9     996 -95.505     994
 -84.646  992.74  -78.97     992 -40.026     990 -30.184     988 -23.753     986
 -21.785  985.26     -13 981.311 -11.286  980.54      -6  977.73       2  977.73
  11.024  981.81  20.177     984  69.488     986  98.983     988 100.394  988.46
 100.853  988.89 102.362     990 105.381     990 121.063     992 157.743     992
 178.904     994 188.681     994 203.379  994.84
#Mann= 3 ,-1 , 0
 -181.43     .12       0     -13     .04       0  11.024     .12       0
Bank Sta=-13,11.024
XS Rating Curve= 0 ,0
Exp/Cntr=0.5,0.3

Type RM Length L Ch R = 1 ,4950    ,40.799,47,44.541
XS GIS Cut Line= 4
588407.6686561124390462.51842959588451.0081686474390485.06143786
588499.108657242 4390488.2344059588524.3491455544390511.25595019
#Sta/Elev= 30
-188.976  1001.3-178.576    1000-169.226  999.26-162.795     998-149.344   996.6
-136.647  995.64 -120.44     994-104.495     992 -93.438  991.38 -68.504     988
 -24.573     984 -10.138  980.47      -4  976.71       4  976.71  10.367   980.4
  15.125     982  25.262     984  34.514     984  59.252   985.3  93.996     988
  95.702  988.52 121.161  990.62 129.462  990.99 132.644   990.8 141.798  991.31
 148.491  991.26 163.812     992 177.264     994 222.933  995.44 241.535  995.59
#Mann= 3 ,-1 , 0
-188.976     .12       0 -10.138     .04       0  10.367     .12       0
Bank Sta=-10.138,10.367
XS Rating Curve= 0 ,0
Exp/Cntr=0.5,0.3

Type RM Length L Ch R = 2 ,4924    ,,,
BEGIN DESCRIPTION:
Killarney Drive (structure from MUB HEC-RAS model & field reconnaissance)
END DESCRIPTION:
Bridge Culvert--1,0,-1,-1, 0
Deck Dist Width WeirC Skew NumUp NumDn MinLoCord MaxHiCord MaxSubmerge Is_Ogee
18,28,2.6,0, 17, 17, 983.75, , 0.95, 0, 0,0,,
    -182   -92.7   -84.4   -53.3   -27.6  -10.01     -10    -9.8    -2.4    15.9
      20   20.01      66      90     120     150     190
    1000  991.08  989.99   986.5  984.96983.8625987.8625  987.85  987.74  987.75
987.9841983.9841  986.61     988     990     992     994
                                                                                
                                                        
    -182   -92.7   -84.4   -53.3   -27.6  -10.01     -10    -9.8    -2.4    15.9
      20   20.01      66      90     120     150     190
    1000  991.08  989.99   986.5  984.96983.8625987.8625  987.85  987.74  987.75
987.9841983.9841  986.61     988     990     992     994
                                                                                
                                                        
BR Coef=-1 , 0 , 0 ,, 0 ,,,0.8,-1,,0,
WSPro=,,,, 1 ,,,, 0 ,,,, 0 ,,,,-1 ,-1 ,-1 , 0 , 0 , 0 , 0 , 0
Culvert=2,5.7,10,28,0.013,0.5,1,8,1,976.5,0,975,-3,Culvert #1  , 0 ,18
Culvert Bottom n=0.013
Culvert=4,5,7.5,28,0.013,0.5,1,29,1,977.1,10.75,975.5,7.75,Culvert #2  , 0 ,18
Culvert Bottom n=0.013
BR U #Sta/Elev= 30
-188.976  1001.3-178.576    1000-169.226  999.26-162.795     998-149.344   996.6
 -120.44     994-104.495     992 -93.438  991.38 -68.504     988 -24.573     984
 -15.289  981.62     -10  982.23      -5   976.5     4.3   976.5       9   977.1
    15.5   977.1   15.51  982.23  25.262     984  34.514     984  59.252   985.3
  93.996     988  95.702  988.52 121.161  990.62 132.644   990.8 141.798  991.31
 148.491  991.26 163.812     992 177.264     994 222.933  995.44 241.535  995.59
BR U #Mann= 3
-188.976     .12     -10    .035   15.51     .12
BR U Banks=-10,15.51
BR D #Sta/Elev= 30
-198.753  1002.5-189.895 1001.93-178.478    1000-170.112  998.01-158.038  994.24
-151.608   992.5-143.602  991.11-127.329  988.75-104.823  987.03 -87.336     986
 -74.475     986 -70.276  985.51 -60.728  985.05 -46.391     984 -17.815  983.84
    -9.7     983    -8.4     975     2.1     975       6   975.5      12   975.5
    12.5     983  17.946  983.98   37.27  984.84  69.849  987.09 109.908  989.47
 123.556  990.75 147.933  992.34 169.587     994 176.804  994.17 215.814  994.34
BR D #Mann= 3
-198.753     .12    -9.7    .035    12.5     .12
BR D Banks=-9.7,12.5
BC Design=,, 0 ,, 0 ,,,,,,
BC Use User HTab Curves=0
BC User HTab FreeFlow(D)= 0

Type RM Length L Ch R = 1 ,4903    ,1.51,7,20.08
BEGIN DESCRIPTION:
Channel from MUB HEC-RAS
END DESCRIPTION:
XS GIS Cut Line= 4
588402.4047600474390474.39648573588454.0531206854390499.58515804
588490.6687451374390499.37179804588515.223433441 4390520.3267983
#Sta/Elev= 30
-198.753  1002.5-189.895 1001.93-178.478    1000-170.112  998.01-158.038  994.24
-151.608   992.5-143.602  991.11-127.329  988.75 -94.718  986.39 -87.336     986
 -74.475     986 -70.276  985.51 -60.728  985.05 -46.391     984 -13.451  983.86
     -12  982.23   -10.4     975.0999999     975       4     976       9     976
    10.5     984  18.602     984   43.57  985.23  69.849  987.09 109.908  989.47
 123.556  990.75 147.933  992.34 169.587     994 176.804  994.17 215.814  994.34
#Mann= 3 ,-1 , 0
-198.753     .12       0 -13.451     .04       0    10.5     .12       0
Bank Sta=-13.451,10.5
XS Rating Curve= 0 ,0
Exp/Cntr=0.5,0.3

Type RM Length L Ch R = 1 ,4896    ,310.764,317,324.467
BEGIN DESCRIPTION:
Channel from MUB HEC-RAS
END DESCRIPTION:
XS GIS Cut Line= 4
588402.3773280464390474.89026174  588447.14330464390496.69260601
588470.8780808934390509.16197416588493.6344491744390524.13679835
#Sta/Elev= 30
-197.113 1002.63-188.222    1002-176.706    1000 -168.93     998-156.365     994
-149.344     992-145.144   991.2-130.184  988.71-128.675  988.53  -122.9     988
-112.238  987.43-107.283  986.91 -91.601     986 -73.688     986  -68.11  985.35
 -58.924  984.88 -46.621     984 -29.396     984 -11.877  983.86   -11.1  983.82
   -10.4     975.0999999     975       4     976       9     976    10.5     984
  13.091  983.99  14.206     984  62.238     988  114.37     992 143.602  992.84
#Mann= 3 ,-1 , 0
-197.113     .12       0 -11.877     .04       0  13.091     .12       0
Bank Sta=-11.877,13.091
XS Rating Curve= 0 ,0
Exp/Cntr=0.5,0.3