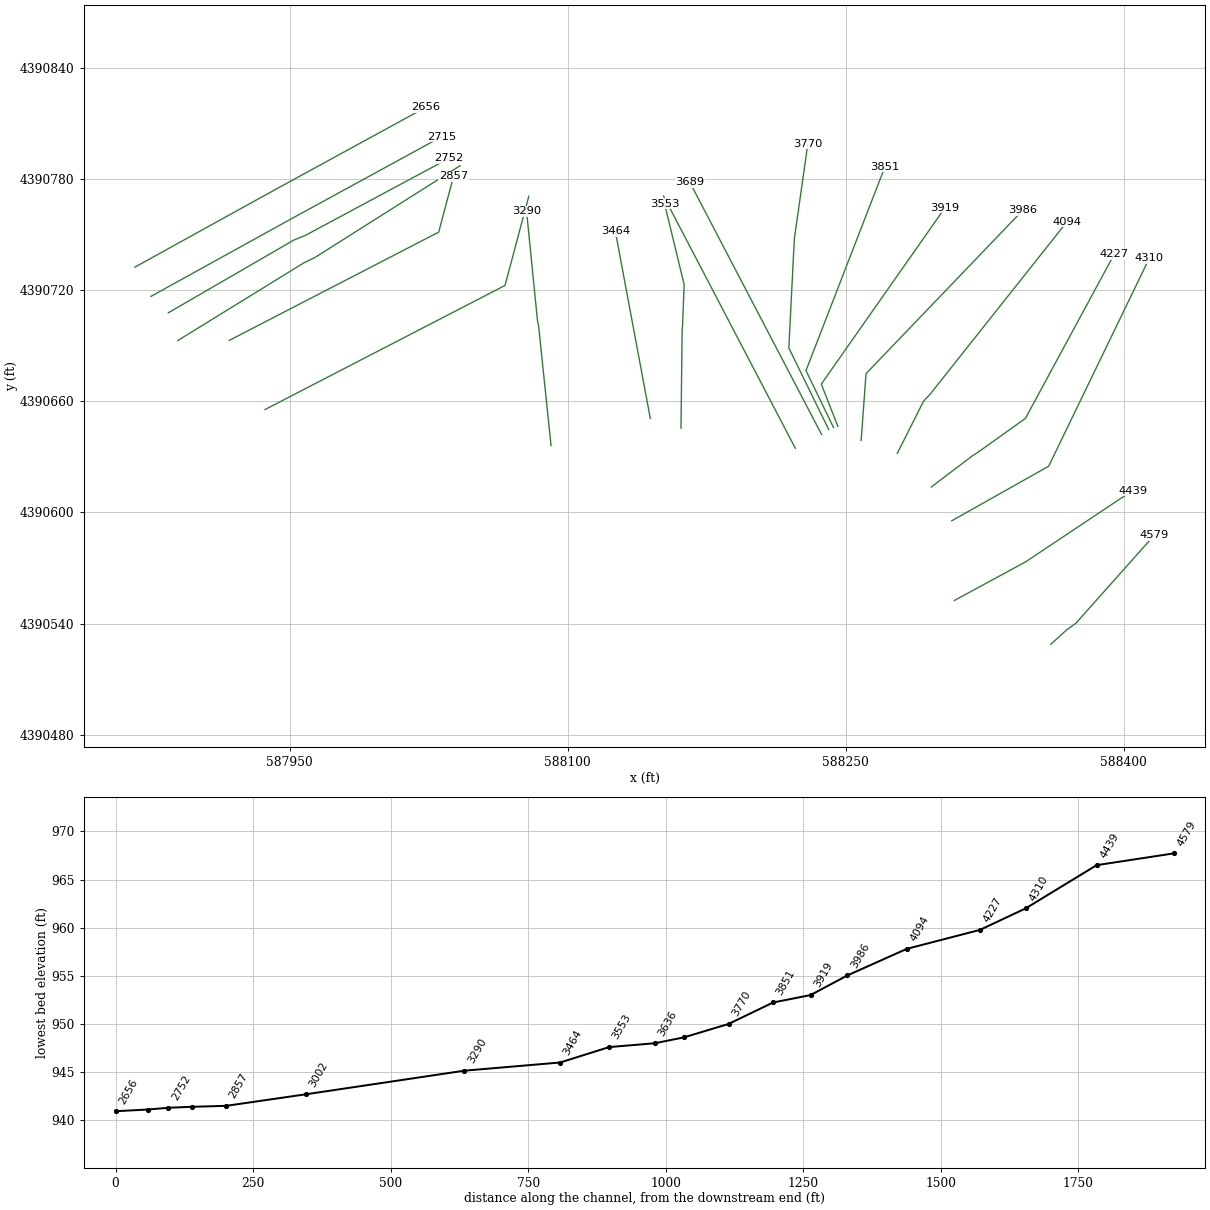
HEC-RAS study BurroughsRun.prj: Burroughs Run

--- BurroughsRun.g01 (geometry) --- (continued)

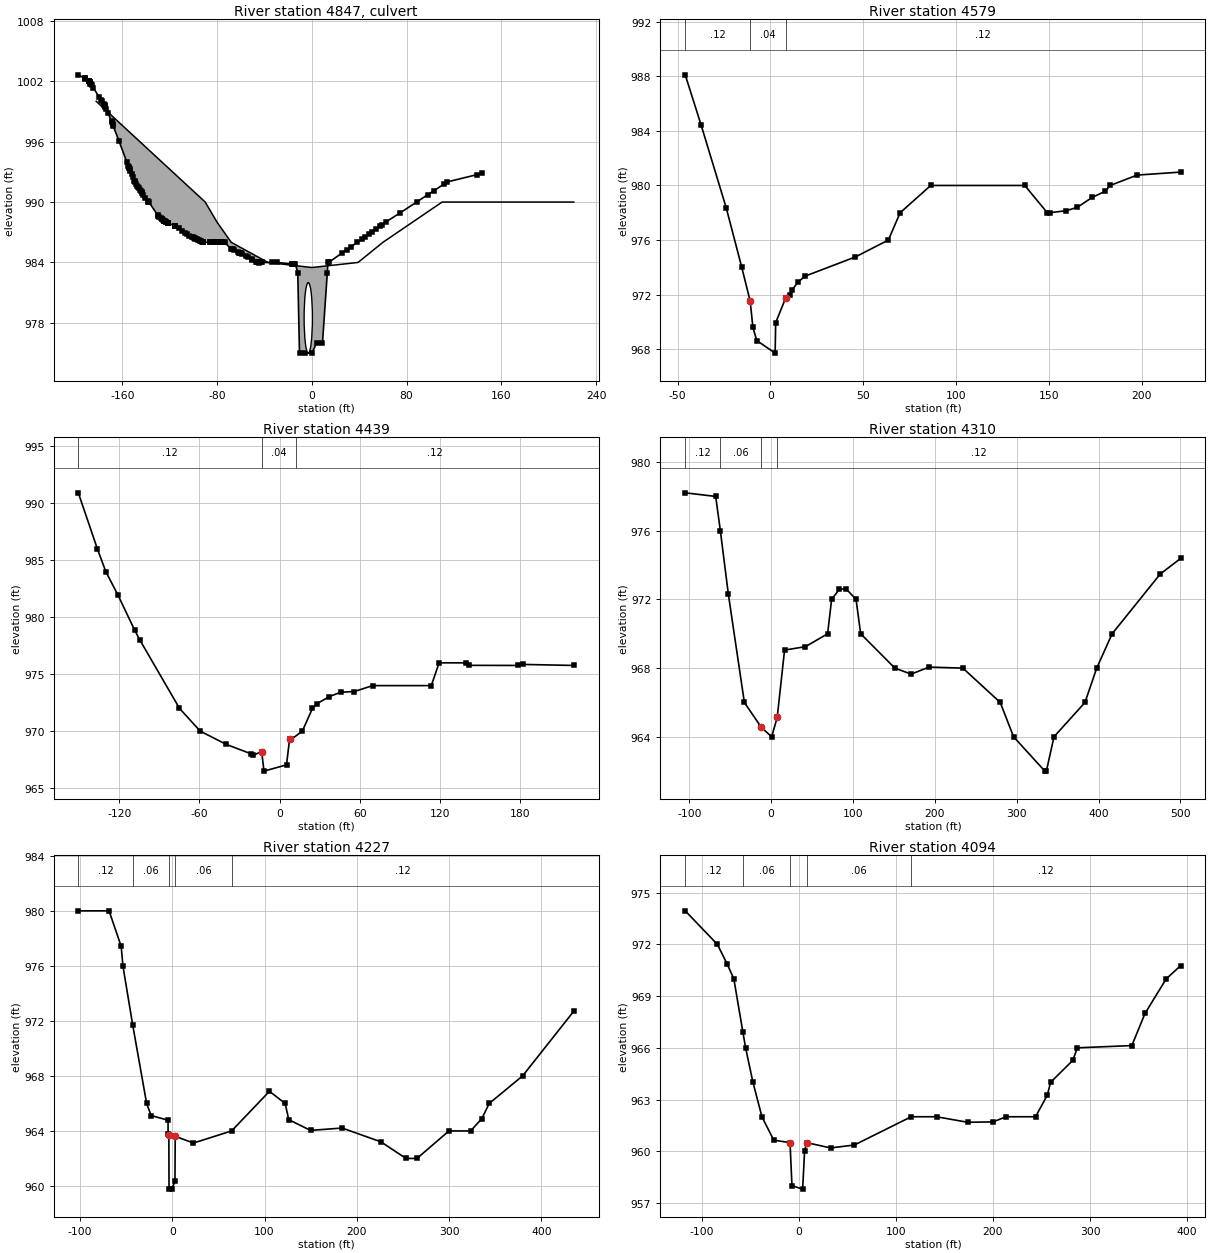
Type RM Length L Ch R = 2 ,4847    ,,,
BEGIN DESCRIPTION:
Dogwood Avenue (structure from MUB HEC-RAS model)
END DESCRIPTION:
Bridge Culvert--1,0,-1,-1, 0
Deck Dist Width WeirC Skew NumUp NumDn MinLoCord MaxHiCord MaxSubmerge Is_Ogee
1,290,2.8,0, 11, 11, , , 0.98, 0, 0,0,,
    -182     -90     -80     -68     -37       0      39      60      85     110
   221.1
    1000     990     988     986     984   983.5     984     986     988     990
     990
                                                                                
        
    -182     -90     -80     -68     -37       0      39      60      85     110
   221.1
     978     978     978     978     978     978     978     978     978     978
     978
                                                                                
        
BR Coef=-1 , 0 , 0 ,, 0 ,,,0.8,-1,,0,
WSPro=,,,, 1 ,,,, 0 ,,,, 0 ,,,,-1 ,-1 ,-1 , 0 , 0 , 0 , 0 , 0
Culvert=1,7,,290,0.024,0.5,1,2,1,975,-3,969.25,0,Culvert #1  , 0 ,1
Culvert Bottom n=0.024
BR U #Sta/Elev= 164
-197.113 1002.63-191.437 1002.28-191.339 1002.27 -191.24 1002.26 -188.32    1002
-188.287    1002-188.255    1002-188.222    1002-187.598 1001.88  -187.5 1001.87
-186.909 1001.74-186.516 1001.68-185.892 1001.58-184.678 1001.37-179.593 1000.45
-177.625 1000.15-176.706    1000-175.394  999.69-175.197  999.64-174.967  999.59
-174.639  999.51-174.213   999.4-173.458  999.21-172.014  998.83 -168.93     998
-168.832  997.97-168.176  997.73-167.684  997.55-162.697  996.04-156.365     994
-154.856  993.54-154.626  993.47-154.331  993.38-153.904  993.25-153.215  993.05
  -152.1  992.74 -151.28   992.5-149.705  992.09-149.606  992.07-149.344     992
-148.392   991.8-147.474  991.62 -146.85  991.51-145.932  991.35-145.144   991.2
-144.357  991.07-143.766  990.98-143.241  990.92-142.126   990.7-140.518  990.44
-138.255   990.1-137.927  990.05  -137.5     990-130.184  988.71-129.495  988.62
-128.675  988.53-127.493  988.42-126.148  988.29 -126.05  988.28-125.919  988.26
-124.475  988.13-124.442  988.13-124.377  988.12-124.344  988.12  -122.9     988
-122.835     988-121.161  987.92-121.129  987.92-121.063  987.91 -121.03  987.91
-115.814  987.65 -115.65  987.63-115.453  987.61-112.238  987.43-109.613  987.09
-107.283  986.91-105.151   986.8-103.478  986.66-100.886  986.54-100.131  986.48
 -99.344  986.44 -99.016  986.41 -98.196  986.37 -97.343  986.33 -96.457  986.28
 -95.472  986.23 -94.455  986.17 -93.832  986.12 -92.946  986.07 -92.028  986.02
 -91.995  986.02 -91.601     986 -85.564     986 -85.531     986 -83.301     986
 -83.235     986 -81.135     986  -81.07     986 -81.037     986 -79.068     986
 -79.035     986  -78.97     986 -77.165     986   -77.1     986 -77.001     986
 -76.017     986 -74.836     986 -74.803     986 -73.688     986  -68.11  985.35
 -66.732  985.31 -65.453  985.26 -62.434  985.03 -61.056  984.97 -60.696  984.96
 -60.302  984.94 -59.941  984.93 -59.613  984.91 -58.924  984.88 -55.676  984.66
  -53.51  984.51 -50.787  984.31 -50.525  984.29 -47.113  984.04 -46.621     984
 -44.915  983.94 -42.815     984 -42.126     984 -33.727     984 -29.396     984
 -17.126  983.84 -16.404  983.84 -15.617  983.84 -14.797  983.85 -13.878  983.85
 -11.877     983   -10.4     975      -6     975      .1     975       4     976
       9     976  13.091     983  13.517     984  14.206     984  25.098  984.92
  29.396  985.27   32.94  985.56   38.55     986  42.552  986.33  44.488  986.49
  48.294   986.8   50.82  987.01  54.232   987.3  57.743  987.61  59.055  987.72
  62.238     988  74.344  988.91  88.451     990  97.867  990.74 103.051  991.13
 111.417  991.77  114.37     992 139.042  992.71 143.602  992.84
BR U #Mann= 3
-197.113     .12 -11.877    .045  13.091     .12
BR D #Sta/Elev= 81
 -45.965  988.11 -45.702     988 -44.718  987.57 -41.142     986 -39.501  985.34
 -38.911  985.09 -37.664  984.53 -37.369  984.42 -37.205  984.34  -36.45     984
 -35.564  983.62 -33.071   982.5 -32.415  982.22 -31.955     982  -31.43  981.78
 -27.625     980 -23.819  978.34     -12  978.51     -11  974.79    -7.5  969.61
    -5.4  968.63       0  968.09     4.5  967.71     4.8  969.94     6.8  970.11
     7.6  974.79  45.768  974.76  46.621  974.82  47.605  974.89  48.753  974.97
  51.148  975.12  52.493  975.21  54.068  975.32   55.84  975.44   63.55     976
  66.864  977.02  67.749  977.31   69.39  977.84  69.587   977.9  69.685  977.93
  69.718  977.94  69.882     978  83.661  979.71  86.385     980  88.189     980
  88.484     980   96.26     980  97.966     980 104.396     980 107.612     980
 112.566     980 125.689     980 137.073     980 147.605  978.27  148.72  978.08
 148.917  978.05 149.213     978 150.426     978 154.199  978.05 154.232  978.05
 154.265  978.05 156.791  978.09 156.824  978.09 156.857  978.09  156.89   978.1
 156.923   978.1 159.449  978.15 160.269  978.22 162.959  978.31  165.42   978.4
 166.634  978.51 168.734   978.7  173.36  979.12 180.381  979.57 183.071     980
 184.547  980.08 184.744  980.09 197.638  980.76 199.114  980.79 217.979  980.92
 221.096  980.98
BR D #Mann= 3
 -45.965     .12     -11    .035     7.6     .12
BR D Banks=-11,7.6
BC Design=,, 0 ,, 0 ,,,,,,
BC Use User HTab Curves=0
BC User HTab FreeFlow(D)= 0

Type RM Length L Ch R = 1 ,4579    ,144.63,140,135.92
BEGIN DESCRIPTION:
Channel from MUB HEC-RAS
END DESCRIPTION:
XS GIS Cut Line= 5
588360.6654475314390528.84900641588369.236423637 4390536.6153105
588371.6717756674390538.34047852588374.1040796974390540.06259855
588416.5779602224390587.75465513
#Sta/Elev= 28
 -45.965  988.11 -37.369  984.42 -23.819  978.34 -15.486     974 -10.925  971.51
    -9.5  969.61    -7.4  968.63     2.5  967.71     2.8  969.94   8.235  971.77
  10.433     972   11.68  972.35  14.993  972.94  18.799  973.36  45.768  974.76
   63.55     976  69.882     978  86.385     980 137.073     980 149.213     978
 150.426     978 159.449  978.15  165.42   978.4  173.36  979.12 180.381  979.57
 183.071     980 197.638  980.76 221.096  980.98
#Mann= 3 ,-1 , 0
 -45.965     .12       0 -10.925     .04       0   8.235     .12       0
#XS Ineff= 2 , 0
       0                      87       0
Permanent Ineff=
       F       F
Bank Sta=-10.925,8.235
XS Rating Curve= 0 ,0
Exp/Cntr=0.5,0.3

Type RM Length L Ch R = 1 ,4439    ,129.28,129,127
BEGIN DESCRIPTION:
Channel from MUB HEC-RAS
END DESCRIPTION:
XS GIS Cut Line= 5
588308.626942888 4390552.4588147588346.9494473614390573.22788696
588349.5951113944390574.99267898588352.240775427  4390576.757471
588404.8004880764390611.79118343
#Sta/Elev= 30
-150.755  990.93 -136.45     986-130.118     984 -121.26     982-108.629  978.89
-104.626     978 -74.967     972 -59.416     970 -39.797  968.83 -21.096     968
 -20.013  967.87   -13.4  968.21   -11.7  966.49     5.2  967.04     7.5  969.31
    8.75  969.28  17.028     970  24.639     972   28.15  972.42  37.303  973.04
  45.801  973.42  56.004  973.48  69.685     974 113.648     974 119.488     976
 139.403     976 141.831  975.78 178.707  975.77 182.349  975.86 220.341  975.77
#Mann= 3 ,-1 , 0
-150.755     .12       0   -13.4     .04       0  12.336     .12       0
Bank Sta=-13.4,7.5
XS Rating Curve= 0 ,0
Exp/Cntr=0.3,0.1

Type RM Length L Ch R = 1 ,4310    ,80.35,83,85.81
XS GIS Cut Line= 3
588307.2583908714390595.47219123588359.5133035174390624.90672759
588413.7524641874390737.02436098
#Sta/Elev= 30
-105.052  978.21 -67.815     978 -62.106     976 -52.362  972.31 -32.776     966
     -12 964.547    .591     964   7.349  965.13  16.339  969.05  41.896  969.25
   68.93     970  73.852     972  83.366   972.6  91.699  972.61 103.707     972
  109.35     970 151.148     968 170.997  967.65 192.946  968.06 234.252     968
 279.888     966 296.194     964 334.416     962 336.253     962 345.571     964
 383.432     966 397.769     968 416.601     970 475.361  973.48 500.328  974.39
#Mann= 4 ,-1 , 0
-105.052     .12       0 -62.106     .06       0     -12     .04       0
   7.349     .12       0
#XS Ineff= 2 , 0
       0                    91.7       0
Permanent Ineff=
       F       F
Bank Sta=-12,7.349
XS Rating Curve= 0 ,0
Exp/Cntr=0.3,0.1

Type RM Length L Ch R = 1 ,4227    ,123.79,133,140.1
BEGIN DESCRIPTION:
Channel from MUB HEC-RAS
END DESCRIPTION:
XS GIS Cut Line= 6
588296.1606227344390613.69618346588318.3592070084390630.51809566
588319.6881350244390631.35019967588321.0140150414390632.18230368
588346.9463993614390650.70195191588394.9036319544390739.33779301
#Sta/Elev= 30
-101.804     980 -68.504     980 -55.348  977.42 -53.478     976 -42.815  971.68
 -27.789     966   -22.9  965.12    -4.6  964.78    -4.5  963.79    -3.7  963.74
    -3.5  959.78     -.5  959.77     2.9  960.33     3.2  963.61  22.966  963.12
  64.272     964 105.315  966.88 122.343     966 126.214  964.82 149.803  964.04
 184.154  964.21 226.017  963.21 253.346     962 265.157     962 299.803     964
 323.261     964   335.4  964.89 343.471     966 379.626     968 435.039   972.7
#Mann= 5 ,-1 , 0
-101.804     .12       0 -42.815     .06       0    -3.7     .04       0
     3.2     .06       0  64.272     .12       0
#XS Ineff= 2 , 0
       0                   103.5       0
Permanent Ineff=
       F       F
Bank Sta=-3.7,3.2
XS Rating Curve= 0 ,0
Exp/Cntr=0.3,0.1

Type RM Length L Ch R = 1 ,4094    ,112.13,108,105.82
XS GIS Cut Line= 5
588277.8238545074390631.85311968588291.9879106824390659.97701603
588293.7527027044390661.86982405588295.5174947264390663.76263207
588369.4345436394390756.86684122
#Sta/Elev= 30
-116.962  973.95 -83.793     972 -73.556  970.84 -66.864     970 -57.513   966.9
 -54.757     966  -47.31  964.03 -37.959     962 -25.755  960.64      -9   960.5
      -7     958       4   957.8       6     960       8   960.5   32.81  960.19
  57.251  960.36 115.814     962 141.929     962  173.95  961.68 200.033   961.7
  213.55     962  243.93     962 255.971  963.25 259.449     964 282.251  965.27
 286.975     966  343.11  966.13 356.693     968 378.478     970 393.373  970.77
#Mann= 5 ,-1 , 0
-116.962     .12       0 -57.513     .06       0      -9     .04       0
       8     .06       0 115.814     .12       0
#XS Ineff= 2 , 0
       0                     114       0
Permanent Ineff=
       F       F
Bank Sta=-9,8
XS Rating Curve= 0 ,0
Exp/Cntr=0.3,0.1

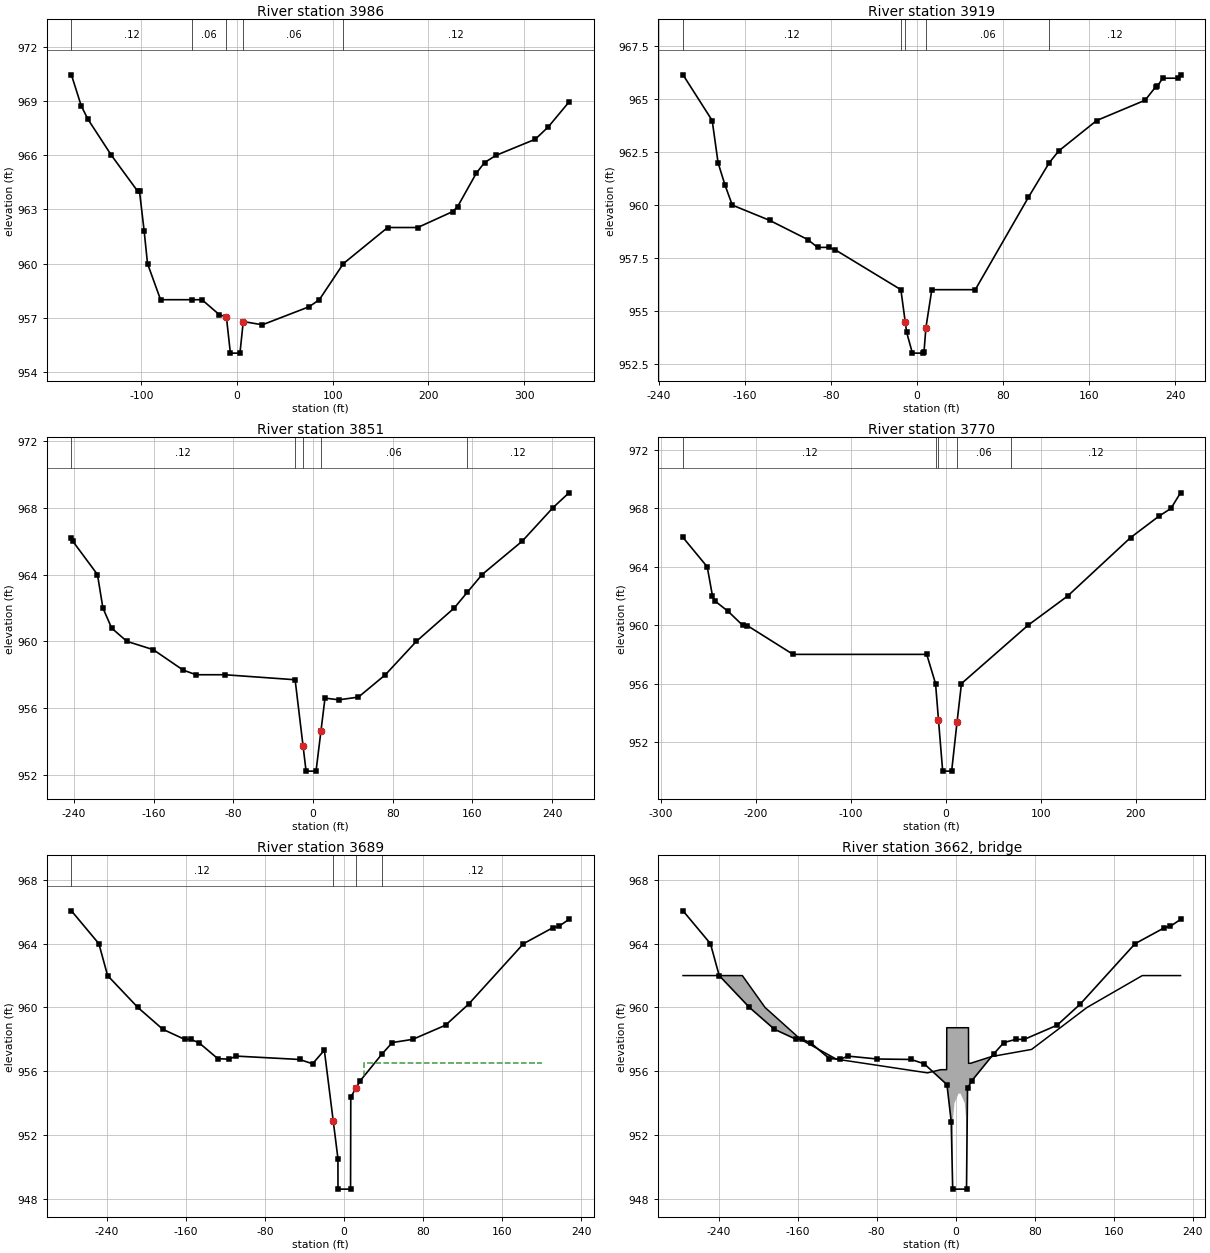
Type RM Length L Ch R = 1 ,3986    ,62.65,67,71.29
BEGIN DESCRIPTION:
Channel from MUB HEC-RAS
END DESCRIPTION:
XS GIS Cut Line= 3
588258.3105582664390638.79646377588260.9562222984390674.84516021
588345.623567345 4390763.1518173
#Sta/Elev= 30
 -173.13  970.46-162.861  968.74-155.873     968-131.332     966 -103.74     964
-101.969     964 -97.146  961.82 -93.602     960 -79.954     958 -47.113     958
 -36.713     958  -18.56  957.17  -11.16  957.04      -7  955.04       3  955.04
    6.46  956.79  26.411  956.61  75.295  957.61  85.958     958 111.089     960
 157.349     962  188.78     962  225.23  962.88 230.381  963.15     250  965.01
 258.629   965.6 270.702     966 311.614  966.89 325.131  967.57 346.818  968.95
#Mann= 5 ,-1 , 0
 -173.13     .12       0 -47.113     .06       0  -11.16     .04       0
    6.46     .06       0 111.089     .12       0
Bank Sta=-11.16,6.46
XS Rating Curve= 0 ,0
Exp/Cntr=0.3,0.1

Type RM Length L Ch R = 1 ,3919    ,61.88,68,74.17
XS GIS Cut Line= 3
 588245.743654114390646.40427186   588236.8130144390669.22464814
588303.6221268264390764.47464932
#Sta/Elev= 29
-217.388  966.16-190.289     964 -184.81     962-178.346  960.94-171.621     960
-137.008  959.28-101.509  958.37 -92.388     958 -82.087     958  -75.82  957.88
 -15.026     956 -10.958  954.46  -9.646  953.98  -4.331     953   5.938     953
    6.43  953.05   8.235  954.21  13.714     956  54.068     956 103.445  960.37
 122.736     962 131.562  962.56 166.864     964 211.844  964.96 221.752   965.6
 223.261  965.62 228.117     966 242.618     966 244.718  966.13
#Mann= 5 ,-1 , 0
-217.388     .12       0 -15.026     .06       0 -10.958     .04       0
   8.235     .06       0 122.736     .12       0
Bank Sta=-10.958,8.235
XS Rating Curve= 0 ,0
Exp/Cntr=0.3,0.1

Type RM Length L Ch R = 1 ,3851    ,72.5,81,89.5
BEGIN DESCRIPTION:
Channel from MUB HEC-RAS
END DESCRIPTION:
XS GIS Cut Line= 3
588243.4271740824390645.74285585588228.5437898984390676.50022423
588271.2096944254390786.63360959
#Sta/Elev= 26
-242.618  966.16-241.339     966 -216.47     964-211.024     962-202.198  960.79
-186.942     960  -160.4   959.5-130.512  958.28-117.454     958 -88.484     958
     -18   957.7     -10 953.722      -7  952.23       3  952.23       8 954.658
      12   956.6      26   956.5  45.538  956.66  72.638     958 103.773     960
 141.864     962 154.921  962.94 169.783     964 210.105     966 240.879     968
 256.955  968.89
#Mann= 5 ,-1 , 0
-242.618     .12       0     -18     .06       0     -10     .04       0
       8     .06       0 154.921     .12       0
#XS Ineff= 2 , 0
       0     -80                       0
Permanent Ineff=
       F       F
Bank Sta=-10,8
XS Rating Curve= 0 ,0
Exp/Cntr=0.3,0.1

Type RM Length L Ch R = 1 ,3770    ,66.99,81,95.01
XS GIS Cut Line= 4
588240.7815100494390644.74920784588219.2839657834390688.73794438
 588222.261861824390747.60701711 588229.537437914390798.87132974
#Sta/Elev= 21
-276.903  966.01-251.411     964-245.866     962-243.504  961.67-229.265  960.94
-214.206     960-209.121  959.97-160.991     958 -20.276     958 -10.991     956
  -7.907  953.51  -3.478     950   5.971     950   11.68  953.38  16.306     956
  86.483     960  128.15     962 194.324     966 224.049  967.46 236.877     968
 246.982  969.07
#Mann= 5 ,-1 , 0
-276.903     .12       0 -10.039     .06       0  -7.907     .04       0
   11.68     .06       0  68.012     .12       0
Bank Sta=-7.907,11.68
XS Rating Curve= 0 ,0
Exp/Cntr=0.5,0.3

Type RM Length L Ch R = 1 ,3689    ,52.925,53,52.886
BEGIN DESCRIPTION:
Channel from MUB HEC-RAS
END DESCRIPTION:
XS GIS Cut Line= 2
588236.9867500024390641.98467181588165.8677651234390778.08701749
#Sta/Elev= 30
-276.083  966.06-248.294     964-239.436     962-208.793     960-183.465  958.63
-161.385     958-155.217     958-146.719  957.78-127.854  956.79-116.798  956.76
-108.924  956.95 -45.112  956.74  -31.89  956.47  -19.97  957.32     -11 952.897
    -6.2  950.53   -6.15  948.61    6.58  948.61     6.8  954.38      12 954.935
   16.45  955.41  38.386  957.08  48.852   957.8  69.488     958 102.789  958.89
 126.115  960.21 181.693     964 211.385     965 217.454  965.09 227.723  965.52
#Mann= 4 ,-1 , 0
-276.083     .12       0     -11     .04       0      12     .06       0
  38.386     .12       0
#XS Ineff= 1 ,-1
      20     200   956.5
Permanent Ineff=
       F
Bank Sta=-11,12
XS Rating Curve= 0 ,0
Exp/Cntr=0.5,0.3

Type RM Length L Ch R = 3 ,3662    ,,,
BEGIN DESCRIPTION:
Eastern Avenue (structure from MUB HEC-RAS model)
END DESCRIPTION:
Bridge Culvert--1,0,-1,-1, 0
Deck Dist Width WeirC Skew NumUp NumDn MinLoCord MaxHiCord MaxSubmerge Is_Ogee
13,24,2.6,0, 28, 28, 956.1, , 0.95, 0, 0,0,,
 -276.08    -216    -193    -157  -120.8   -28.5   -15.1    -9.1      -9      -3
   -2.99    -2.5    -1.2       3       4       5     9.2    10.5   10.99      11
      13    13.1    15.1    36.2    76.9     133     189  227.72
     962     962     960     958  956.76   955.9   956.1   956.1  958.73  958.73
  958.73  958.73  958.73  958.73  958.73  958.73  958.73  958.73  958.73  958.73
  958.73   956.5   956.5  956.92  957.37     960     962     962
                                                                           948.6
  951.82   953.1     954   954.6   954.6   954.6     954   953.1  951.82   948.6
                                                                
 -269.68    -216    -193    -157  -120.8   -28.5   -15.1   -13.1     -13      -7
   -6.99    -6.5    -5.2      -1       0       1     5.2     6.5    6.99       7
      13    13.1    15.1    36.2    76.9     133     189  234.12
     962     962     960     958  956.76   955.9   956.1   956.1  958.73  958.73
  958.73  958.73  958.73  958.73  958.73  958.73  958.73  958.73  958.73  958.73
  958.73   956.5   956.5  956.92  957.37     960     962     962
                                                                           948.6
  951.82   953.1     954   954.6   954.6   954.6     954   953.1  951.82   948.6
                                                                
BR Coef=-1 , 1 , 0 ,, 0 ,,0.6,0.8,0,1.2,0,954.6
WSPro=,,,, 1 ,,,, 0 ,,,, 0 ,,,,-1 ,-1 ,-1 , 0 , 0 , 0 , 0 , 0
BR U #Sta/Elev= 30
-276.083  966.06-248.294     964-239.436     962-208.793     960-183.465  958.63
-161.385     958-155.217     958-146.719  957.78-127.854  956.79-116.798  956.76
-108.924  956.95 -79.495  956.77 -45.112  956.74  -31.89  956.47    -8.8  955.16
    -4.5  952.85      -3  948.61      11  948.61      12 954.935   16.45  955.41
  38.386  957.08  48.852   957.8  60.925     958  69.488     958 102.789  958.89
 126.115  960.21 181.693     964 211.385     965 217.454  965.09 227.723  965.52
BR U #Mann= 4
-276.083     .12    -8.8    .045      12     .06  38.386     .12
BR U Banks=-8.8,12
BR D #Sta/Elev= 30
-269.685  967.17-257.579  966.15-246.883  965.58-236.352  964.69-225.164     964
-220.768  961.98-195.768  960.42-135.466  957.78 -119.39  957.11-114.862     956
 -98.458     956 -64.797  955.54 -42.028  954.88     -11   954.7    -8.5  953.52
      -7  948.25       7  948.25     9.8  954.69  44.849  954.76   98.13     956
 125.984     958 130.184     958 135.466  959.46 138.681     960 167.421     960
 178.445   961.2 181.857  961.28 188.353     962 214.173     962 234.121  963.17
BR D #Mann= 5
-269.685     .12-135.466     .06     -11    .045     9.8     .06 125.984     .12
BR D Banks=-11,9.8
BC Design=,, 0 ,, 0 ,,,,,,
BC Use User HTab Curves=0
BC User HTab FreeFlow(D)= 0

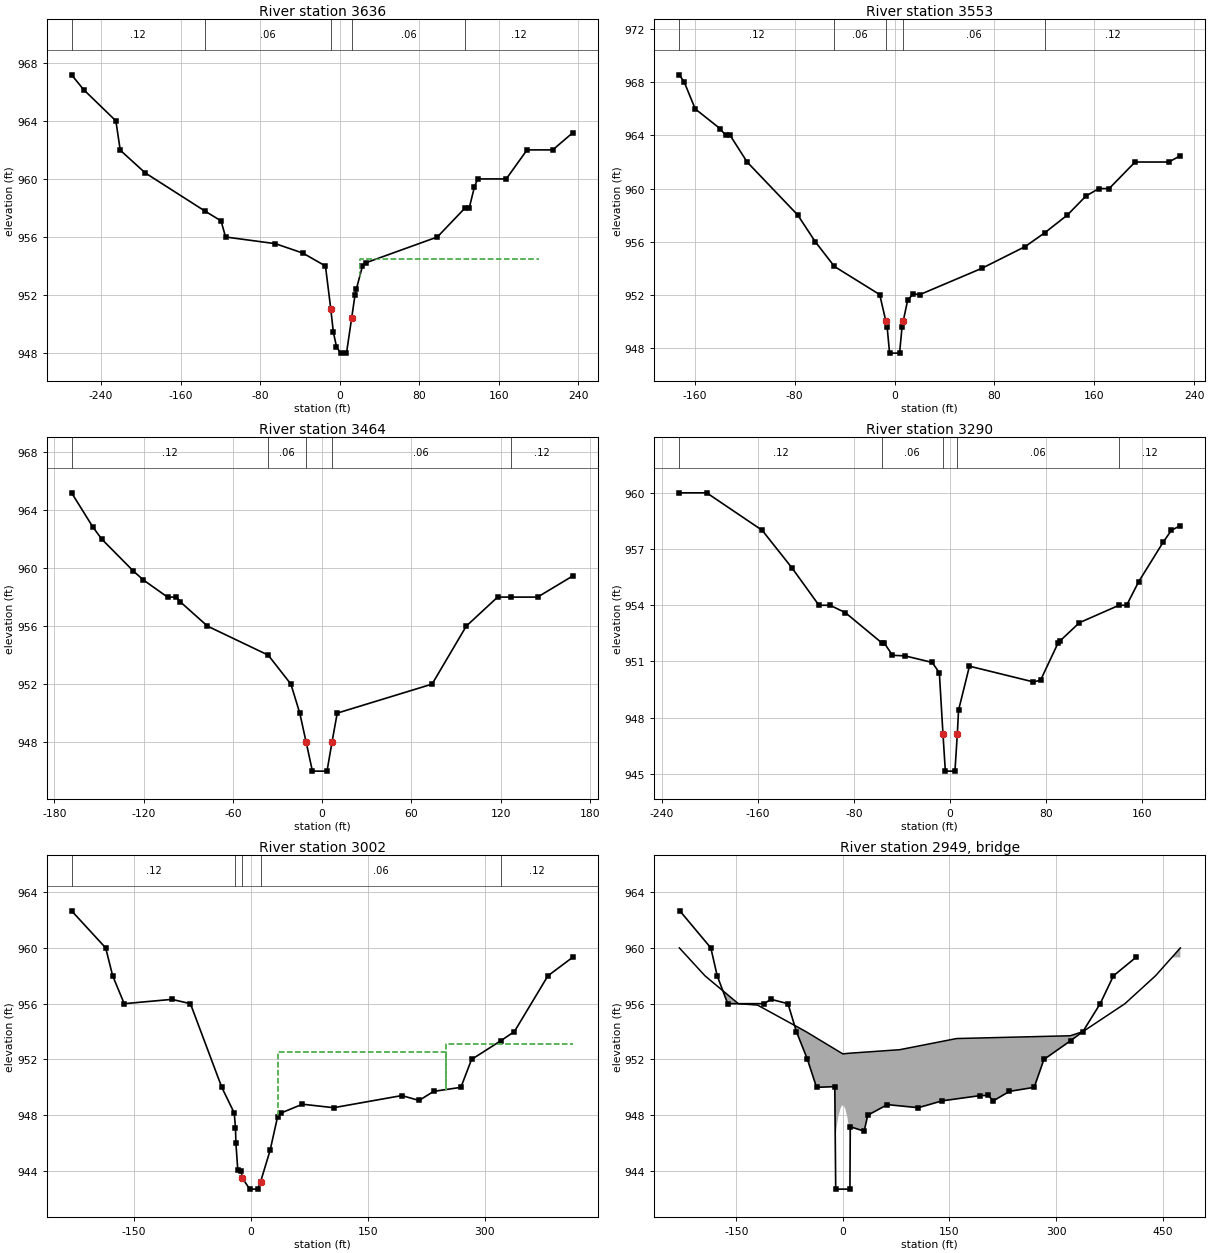
Type RM Length L Ch R = 1 ,3636    ,96,83,68.79
XS GIS Cut Line= 2
588222.8074538274390634.57498371588151.685420948 4390770.6773294
#Sta/Elev= 30
-269.685  967.17-257.579  966.15-225.164     964-220.768  961.98-195.768  960.42
-135.466  957.78 -119.39  957.11-114.862     956 -64.797  955.54 -37.073  954.89
 -14.403     954  -9.088  951.07  -6.463  949.45  -3.314  948.45    .755     948
   6.759     948  11.909  950.39  15.322     952  16.634   952.4  22.835     954
  26.115  954.22   98.13     956 125.984     958 130.184     958 135.466  959.46
 138.681     960 167.421     960 188.353     962 214.173     962 234.121  963.17
#Mann= 5 ,-1 , 0
-269.685     .12       0-135.466     .06       0  -9.088     .04       0
  11.909     .06       0 125.984     .12       0
#XS Ineff= 1 ,-1
      20     200   954.5
Permanent Ineff=
       F
Bank Sta=-9.088,11.909
XS Rating Curve= 0 ,0
Exp/Cntr=0.5,0.3

Type RM Length L Ch R = 1 ,3553    ,83.84,89,95.38
BEGIN DESCRIPTION:
Channel from MUB HEC-RAS
END DESCRIPTION:
XS GIS Cut Line= 5
588161.1037410644390645.47767985588161.7102930724390698.92436051
588161.9449890754390700.73487253588162.7984290854390722.94564881
588152.2157729554390766.55033734
#Sta/Elev= 30
-172.474  968.57-168.471     968-159.777     966-139.764  964.51-135.367     964
-131.726     964-118.176     962 -77.559     958 -63.615     956 -48.228  954.13
  -11.91  952.01      -7 950.008      -6   949.6      -4   947.6       4   947.6
       6   949.6       7 950.044    10.5   951.6   15.13  952.08  20.013     952
  70.144     954 104.692  955.63 120.505  956.68 138.419     958 153.281  959.43
 163.681     960 171.982     960 192.717     962 219.652     962 229.035  962.47
#Mann= 5 ,-1 , 0
-172.474     .12       0 -48.228     .06       0      -7     .04       0
       7     .06       0 120.505     .12       0
Bank Sta=-7,7
XS Rating Curve= 0 ,0
Exp/Cntr=0.3,0.1

Type RM Length L Ch R = 1 ,3464    ,200,174,171.33
XS GIS Cut Line= 2
 588144.540908864390650.70195191588125.6890286274390751.57551316
#Sta/Elev= 23
 -168.34  965.19-154.167  962.85-148.097     962-126.969  959.81-120.079  959.18
-103.871     958 -97.867     958 -95.374  957.68 -77.034     956  -36.22     954
 -20.965     952 -14.993     950 -10.728     948  -6.496     946   3.314     946
    6.66     948  10.171     950  73.917     952  96.916     956 117.946     958
  126.64     958 144.816     958  168.34  959.45
#Mann= 5 ,-1 , 0
 -168.34     .12       0  -36.22     .06       0 -10.728     .04       0
    6.66     .06       0  126.64     .12       0
Bank Sta=-10.728,6.66
XS Rating Curve= 0 ,0
Exp/Cntr=0.3,0.1

Type RM Length L Ch R = 1 ,3290    ,324.18,288,180.14
BEGIN DESCRIPTION:
Channel from MUB HEC-RAS
END DESCRIPTION:
XS GIS Cut Line= 5
588090.9692601984390636.03802373588084.3002361154390700.22585652
588083.9558121114390702.01808055588083.6113881074390703.81335257
588077.7561800344390762.57574529
#Sta/Elev= 30
-225.623     960-202.854     960-156.627     958-131.857     956-109.318     954
-100.066     954 -87.402  953.61 -57.054     952 -55.052     952 -48.064  951.33
   -37.6   951.3     -15  950.95      -9   950.4      -6  947.15      -4  945.15
       4  945.15       6  947.15       7   948.4   16.08  950.75   69.39  949.91
  75.328     950  90.026     952  91.404  952.09  107.71  953.07 140.715     954
 147.047     954 157.021  955.25 177.526  957.37 184.383     958 191.831  958.25
#Mann= 5 ,-1 , 0
-225.623     .12       0 -57.054     .06       0      -6     .04       0
       6     .06       0 140.715     .12       0
Bank Sta=-6,6
XS Rating Curve= 0 ,0
Exp/Cntr=0.5,0.3

Type RM Length L Ch R = 1 ,3002    ,142.34,145,221.901
XS GIS Cut Line= 3
 587936.606346294390655.47816797588066.146347891 4390722.4579688
588078.9601400494390770.56760139
#Sta/Elev= 30
-229.396  962.66-185.728     960-176.772     958-161.975     956 -100.82  956.31
 -77.165     956 -36.975     950  -21.03  948.16 -19.423  947.08 -18.898     946
  -16.47  944.06 -12.106     944  -10.86  943.51  -1.181   942.7   9.022   942.7
  12.664  943.22  24.902  945.48  34.514   947.9  38.451  948.15  66.339  948.79
 106.332  948.54 193.602  949.41 215.748  949.06 234.383  949.71 269.324     950
 282.972     952 320.702  953.35 337.861     954  380.84     958 412.402  959.32
#Mann= 5 ,-1 , 0
-229.396     .12       0 -19.423     .06       0  -10.86     .04       0
  12.664     .06       0 320.702     .12       0
#XS Ineff= 2 ,-1
      35     250   952.5     250 412.402   953.1
Permanent Ineff=
       F       F
Bank Sta=-10.86,12.664
XS Rating Curve= 0 ,0
Exp/Cntr=0.5,0.3

Type RM Length L Ch R = 3 ,2949    ,,,
BEGIN DESCRIPTION:
Aspen Street (structure from MUB HEC-RAS model)
END DESCRIPTION:
Bridge Culvert--1,0,-1,-1, 0
Deck Dist Width WeirC Skew NumUp NumDn MinLoCord MaxHiCord MaxSubmerge Is_Ogee
11,123,2.8,0, 28, 28, 952.4, , 0.95, 0, 0,0,,
    -230    -194    -147    -120     -52     -10   -9.95   -9.78   -8.48   -6.38
   -3.22   -1.29       0    1.29    3.22    6.38    8.48    9.78    9.95      10
      80     160     240     320     338     397     440     475
     960     958     956   955.9     954952.7077952.7062952.7009952.6609952.5963
952.4991952.4397   952.4952.4048952.4182952.4339952.4424952.4485952.4501952.4507
   952.7   953.5   953.6   953.7     954     956     958     960
                                           942.7  945.14  946.69  947.18  947.87
  948.49  948.67   948.7  948.67  948.49  947.87  947.18  946.69  945.14   942.7
                                                                
    -230    -194    -147    -120     -52     -10   -9.95   -9.78   -8.48   -6.38
   -3.22   -1.29       0    1.29    3.22    6.38    8.48    9.78    9.95      10
      80     160     240     320     338     397     440     475
     960     958     956   955.9     954952.7077952.7062952.7009952.6609952.5963
952.4991952.4397   952.4952.4048952.4182952.4339952.4424952.4485952.4501952.4507
   952.7   953.5   953.6   953.7     954     956     958     960
                                           942.7  945.14  946.69  947.18  947.87
  948.49  948.67   948.7  948.67  948.49  947.87  947.18  946.69  945.14   942.7
                                                                
BR Coef=-1 , 1 , 0 ,, 0 ,,,0.8,0,1.2,0,
WSPro=,,,, 1 ,,,, 0 ,,,, 0 ,,,,-1 ,-1 ,-1 , 0 , 0 , 0 , 0 , 0
BR U #Sta/Elev= 30
-229.396  962.66-185.728     960-176.772     958-161.975     956-111.385     956
 -100.82  956.31 -77.165     956 -65.322     954  -49.77     952 -36.975     950
   -11.3  950.05     -10   942.7      10   942.7    10.5  947.17  30.052  946.86
  35.072     948  62.664  948.76 106.332  948.54 139.665  949.03 193.602  949.41
 204.495  949.42 211.811  949.03 234.383  949.71 269.324     950 282.972     952
 320.702  953.35 337.861     954 362.172     956  380.84     958 412.402  959.32
BR U #Mann= 4
-229.396     .12   -11.3    .045    10.5     .06 320.702     .12
BR U Banks=-11.3,10.5
BR D #Sta/Elev= 173
-195.308  957.92-194.619  957.91-192.257  957.86-190.846  957.84-188.123  957.79
-185.597  957.73-183.202  957.67-182.874  957.66 -178.51  957.55-178.051  957.55
-177.625  957.54-177.165  957.52-176.444  957.51 -176.28   957.5-175.787  957.48
-171.457  957.15-170.833  957.09-170.112  957.01-160.039     956-155.249  954.23
 -155.02  954.14-154.757  954.04-154.626     954-148.655  953.65-146.227   953.5
-144.226  953.38 -142.52  953.28-141.043  953.19-139.797  953.11-139.633   953.1
-138.517  953.03-137.566  952.97-136.713  952.92-136.581  952.91-128.839  952.41
 -112.73     952 -110.86     952-108.104     952-108.005     952-104.954     952
-100.755     952-100.492     952 -99.902     952 -99.672     952 -99.442     952
 -99.278     952 -99.114     952 -98.983     952 -97.343     952  -91.01  950.09
 -90.748     950 -89.928  949.98 -89.797  949.97 -18.832     948 -13.419     948
     -10   941.5  -8.169   941.5   -.853   941.5   4.429   941.5    5.61   941.5
   6.496   941.5   7.677   941.5   8.629   941.5   9.646   941.5    10.5   941.5
   10.63  946.62  10.958  946.83  12.927     948  19.718  948.47  25.164  948.84
   30.61  949.22  37.172  949.66  37.238  949.67  37.402  949.68  37.467  949.69
  37.566  949.69  37.664   949.7  37.762   949.7  37.828  949.71  45.866  949.65
  57.546  949.93  62.533  949.93  67.224  949.93  71.621  949.94  75.984  949.96
  84.974     950  90.715     950  94.062  949.99  97.146  949.98 100.164  949.97
 103.215  949.97 106.299  949.97 121.358  949.97 123.688  949.97  126.05  949.97
 128.379  949.97 130.741  949.98   135.4  949.98 139.337     950 139.403     950
 140.486     950 140.617     950 140.748     950 140.879     950 141.076     950
  141.24     950 142.749     950 144.062     950 146.227     950 150.656     950
 164.665     950 171.096     950 172.047  950.07 172.113  950.07 172.146  950.08
 172.244  950.08 177.329  950.44 177.887  950.48 179.167  950.57 183.136  950.85
 184.186  950.93 185.433  951.01 188.058   951.2 189.501   951.3 191.175  951.41
 192.684  951.52 194.455  951.64 196.457  951.77 198.885  951.93  199.18  951.95
 199.934     952 200.033     952 209.908     952 211.352     952 211.909     952
 213.353     952 214.797     952 216.207     952 217.585     952 222.146  952.12
 237.402  952.41  238.78   952.4 240.157  952.39 241.535  952.37 249.311  952.31
 249.869  952.33 250.427  952.34 251.608  952.33 252.822  952.33 253.412  952.34
 254.626  952.34 264.337  952.19 264.633   952.2  267.06  952.31 267.126  952.31
 267.192  952.31 267.257  952.32 267.979  952.36 273.786  952.54 291.667  953.79
 291.699  953.79 291.765   953.8 291.798   953.8  292.29  953.83 292.356  953.83
 294.718     954 316.306  955.85 318.077     956 318.176  956.01 318.209  956.02
  319.39  956.17 319.521  956.18 324.508  956.77
BR D #Mann= 5
-195.308     .12 -13.419    .045   10.63     .08  25.164     .05  75.984     .12
BC Design=,, 0 ,, 0 ,,,,,,
BC Use User HTab Curves=0
BC User HTab FreeFlow(D)= 0

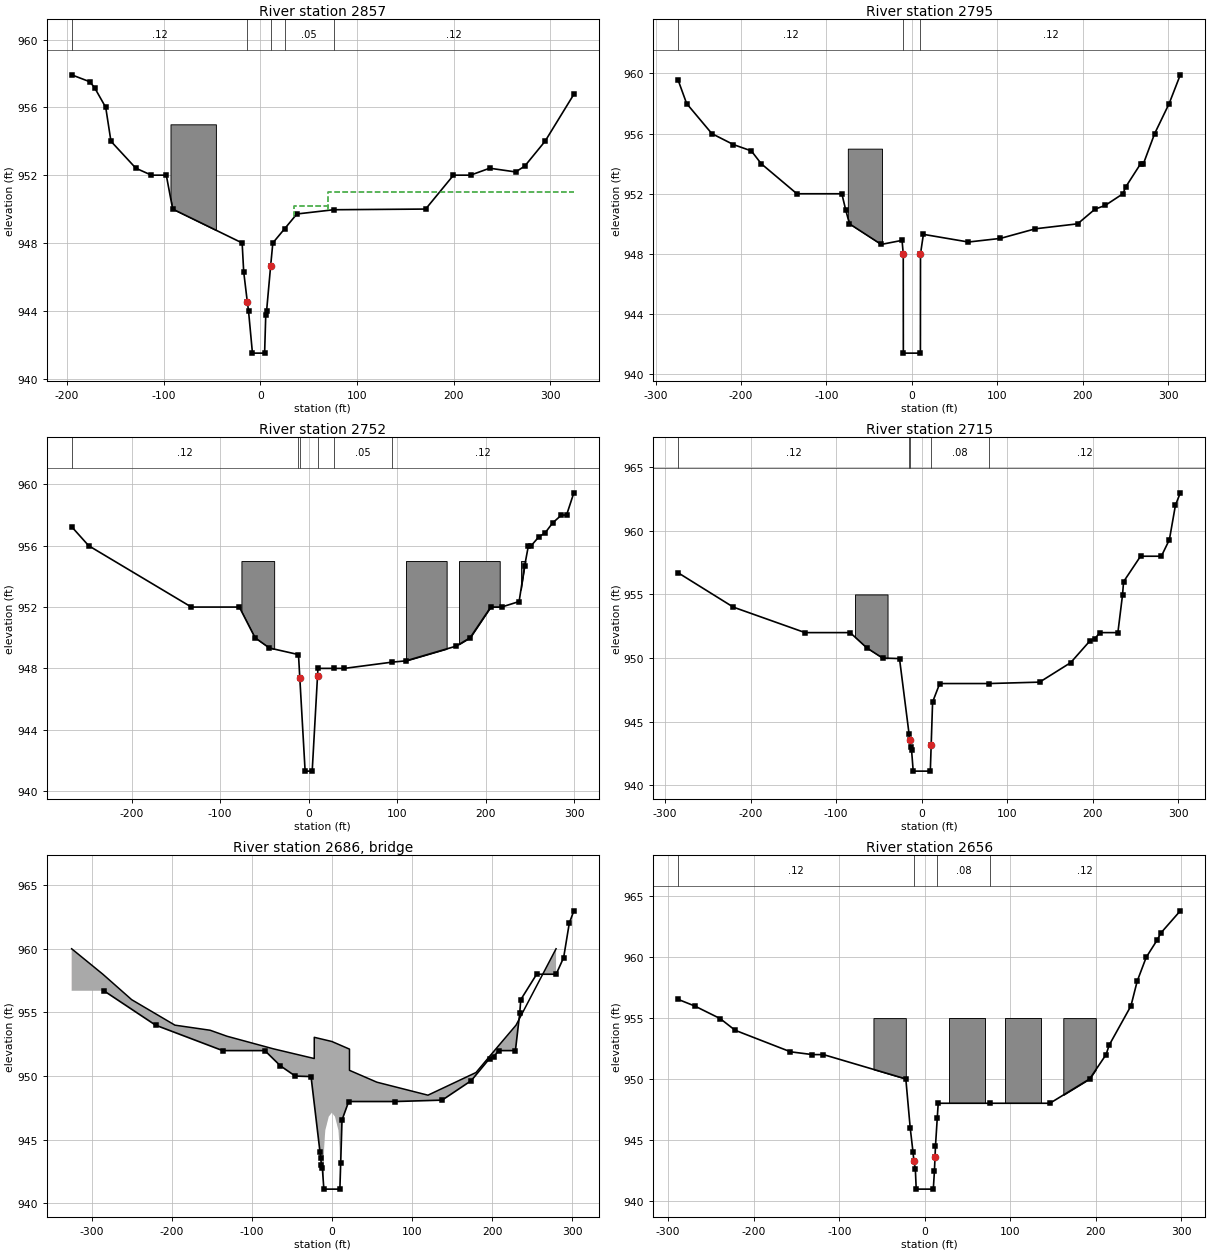
Type RM Length L Ch R = 1 ,2857    ,61.24,62,63.19
XS GIS Cut Line= 3
587917.3155540514390692.78568843588030.3445394484390751.22804115
588038.3729715484390781.37580953
#Sta/Elev= 30
-195.308  957.92-176.444  957.51-171.457  957.15-160.039     956-154.626     954
-128.839  952.41 -112.73     952 -97.343     952 -90.748     950 -18.832     948
 -17.224   946.3 -13.419  944.49 -12.238     944  -8.169   941.5   4.429   941.5
    5.61  943.75   6.496     944   10.63  946.62  12.927     948  25.164  948.84
  37.828  949.71  75.984  949.96 171.096     950 199.934     952 217.585     952
 237.402  952.41 264.337  952.19 273.786  952.54 294.718     954 324.508  956.77
#Mann= 5 ,-1 , 0
-195.308     .12       0 -13.419     .04       0   10.63     .08       0
  25.164     .05       0  75.984     .12       0
#XS Ineff= 2 ,-1
      35      70   950.2      70 324.508     951
Permanent Ineff=
       F       F
#Block Obstruct= 1 ,-1
     -93     -46     955
Bank Sta=-13.419,10.63
XS Rating Curve= 0 ,0
Exp/Cntr=0.5,0.3

Type RM Length L Ch R = 1 ,2795    ,44.03,43,41.05
BEGIN DESCRIPTION:
Channel from MUB HEC-RAS
END DESCRIPTION:
XS GIS Cut Line= 5
587889.5452257084390692.71558443587957.7076505514390734.71092895
587960.4874265854390736.03071297587963.2702506194390737.35354498
588041.936083592 4390787.0816656
#Sta/Elev= 30
-273.786  959.56-263.812     958-234.285     956-208.957  955.27-188.025  954.85
-176.476     954-134.678     952 -82.021     952 -77.428  950.91 -73.097     950
 -35.892  948.63   -11.5   948.9   -10.1     948     -10   941.4      10   941.4
    10.1     948    13.5   949.3  66.207  948.79 103.675  949.03 144.652  949.67
  194.16     950 214.337  950.97 226.608  951.23 247.211     952 250.328  952.44
 267.979     954 271.227     954  284.35     956 301.345     958 314.403  959.91
#Mann= 3 ,-1 , 0
-273.786     .12       0   -10.1     .04       0    10.1     .12       0
#Block Obstruct= 1 ,-1
     -75     -35     955
Bank Sta=-10.1,10.1
XS Rating Curve= 0 ,0
Exp/Cntr=0.3,0.1

Type RM Length L Ch R = 1 ,2752    ,36.01,37,38.37
BEGIN DESCRIPTION:
Channel from MUB HEC-RAS
END DESCRIPTION:
XS GIS Cut Line= 5
587884.4550656454390707.70564862587952.196866483 4390746.9456011
587955.3332585214390748.22271312 587958.469650564390749.50287313
588036.0077235184390791.10197765
#Sta/Elev= 30
-267.946  957.24-248.688     956-132.579     952 -78.379     952  -60.63     950
 -44.357  949.33   -11.5   948.9     -10 947.373      -4   941.3       4   941.3
      10 947.478    10.5     948  28.445     948  40.354     948  94.619  948.41
 109.777  948.49 166.667  949.45 182.579     950  205.84     952 218.077     952
 237.926  952.36  244.16  954.68 248.425     956 251.542     956 260.564   956.6
 267.093  956.82 275.886  957.49 285.794     958 291.568     958 299.803  959.45
#Mann= 6 ,-1 , 0
-267.946     .12       0   -11.5     .08       0     -10     .04       0
      10     .08       0  28.445     .05       0  94.619     .12       0
#Block Obstruct= 4 ,-1
     -76     -39     955     110     156     955     170     216     955
     240     280     955
Bank Sta=-10,10
XS Rating Curve= 0 ,0
Exp/Cntr=0.5,0.3

Type RM Length L Ch R = 1 ,2715    ,59.18,59,59.171
BEGIN DESCRIPTION:
Channel from MUB HEC-RAS
END DESCRIPTION:
XS GIS Cut Line= 3
587875.0489375294390716.55094473587951.6543224764390758.87242525
588031.8563474674390802.67828179
#Sta/Elev= 30
-284.777   956.7 -220.21     954-136.385     952 -83.727     952 -64.206   950.8
 -45.735     950 -26.017  949.96 -14.764     944 -14.009  943.57 -13.025  943.01
  -11.88  942.75     -10  941.12      10  941.12      11 943.154   12.67  946.55
  20.997     948  78.839     948  137.73  948.11 174.049  949.64 196.949  951.38
 202.001  951.51 208.301     952 229.232     952 234.646  954.95 235.892     956
 255.741     958 280.052     958 289.436   959.3  296.49     962 302.198  962.98
#Mann= 5 ,-1 , 0
-284.777     .12       0 -14.764     .08       0 -14.009     .04       0
      11     .08       0  78.839     .12       0
#XS Ineff= 2 , 0
       0     -40                       0
Permanent Ineff=
       F       F
#Block Obstruct= 1 ,-1
     -78     -40     955
Bank Sta=-14.009,11
XS Rating Curve= 0 ,0
Exp/Cntr=0.5,0.3

Type RM Length L Ch R = 3 ,2686    ,,,
BEGIN DESCRIPTION:
Meridan Street (structure from MUB HEC-RAS model)
END DESCRIPTION:
Bridge Culvert--1,0,-1,-1, 0
Deck Dist Width WeirC Skew NumUp NumDn MinLoCord MaxHiCord MaxSubmerge Is_Ogee
13,35,2.8,0, 28, 28, 948.5, , 0.95, 0, 0,0,,
    -325    -286    -250    -196    -152    -131     -73  -22.01     -22     -10
   -9.95   -9.66   -8.23   -3.86       0    3.86    8.23    9.66    9.95      10
      22   22.01    56.2     120     180     203     230     280
     960     958     956     954   953.6  953.13  952.14951.3785953.0452 952.866
952.8652952.8609952.8395952.7743952.7167952.6116952.4926952.4537952.4458952.4444
952.1177 950.451  949.52   948.5  950.28     952     954     960
                                                                          941.12
  943.56  944.37  945.73  946.82  947.12  946.82  945.73  944.37  943.56  941.12
                                                                
    -325    -286    -250    -196    -152    -131     -73  -22.01     -22     -10
   -9.95   -9.66   -8.23   -3.86       0    3.86    8.23    9.66    9.95      10
      22   22.01    56.2     120     180     203     230     280
     960     958     956     954   953.6  953.13  952.14951.3785953.0452 952.866
952.8652952.8609952.8395952.7743952.7167952.6116952.4926952.4537952.4458952.4444
952.1177 950.451  949.52   948.5  950.28     952     954     960
                                                                          941.12
  943.56  944.37  945.73  946.82  947.12  946.82  945.73  944.37  943.56  941.12
                                                                
BR Coef=-1 , 1 , 0 ,, 0 ,,,0.8,0,1.2,0,
WSPro=,,,, 1 ,,,, 0 ,,,, 0 ,,,,-1 ,-1 ,-1 , 0 , 0 , 0 , 0 , 0
BC Design=,, 0 ,, 0 ,,,,,,
BC Use User HTab Curves=0
BC User HTab FreeFlow(D)= 0

Type RM Length L Ch R = 1 ,2656    ,69.87,65,62.54
BEGIN DESCRIPTION:
Channel invert from MUB HEC-RAS
END DESCRIPTION:
XS GIS Cut Line= 3
587866.3438494214390732.30605692587942.9888583694390774.64887344
 588023.227459364390818.47606599
#Sta/Elev= 30
-288.419  956.54-269.127     956-239.239  954.96-221.752     954-157.021  952.23
-131.365     952-118.471     952 -22.146     950  -17.06     946  -13.78     944
  -12.68  943.23  -11.04  942.63     -10  940.94      10  940.94   11.32  942.45
      12 943.589   12.55  944.51  14.633  946.81  15.715     948  76.476     948
 146.325     948 192.782     950 212.008     952  215.65  952.78 241.076     956
 248.425  958.04 258.957     960 271.752  961.42 276.116     962 298.819  963.82
#Mann= 4 ,-1 , 0
-288.419     .12       0  -12.68     .04       0  14.633     .08       0
  76.476     .12       0
#XS Ineff= 2 , 0
       0  -22.15                       0
Permanent Ineff=
       F       F
#Block Obstruct= 4 ,-1
     -60  -22.15     955      28      70     955      94     136     955
     162     200     955
Bank Sta=-12.68,12
XS Rating Curve= 0 ,0
Exp/Cntr=0.5,0.3