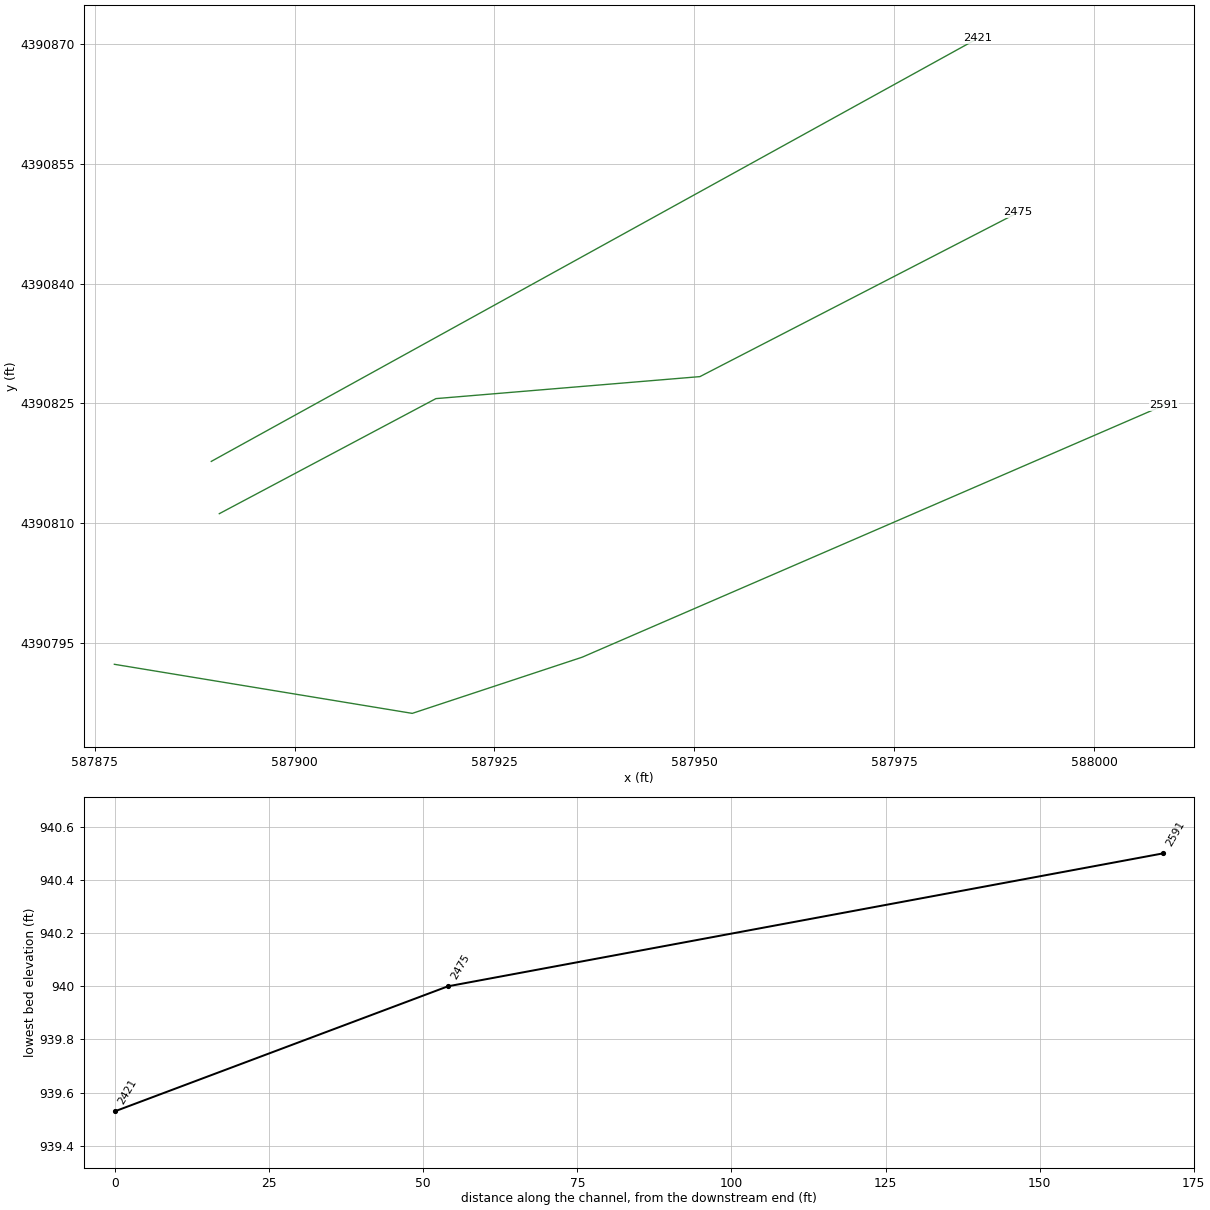
HEC-RAS study BurroughsRun.prj: Burroughs Run

--- BurroughsRun.g01 (geometry) --- (continued)

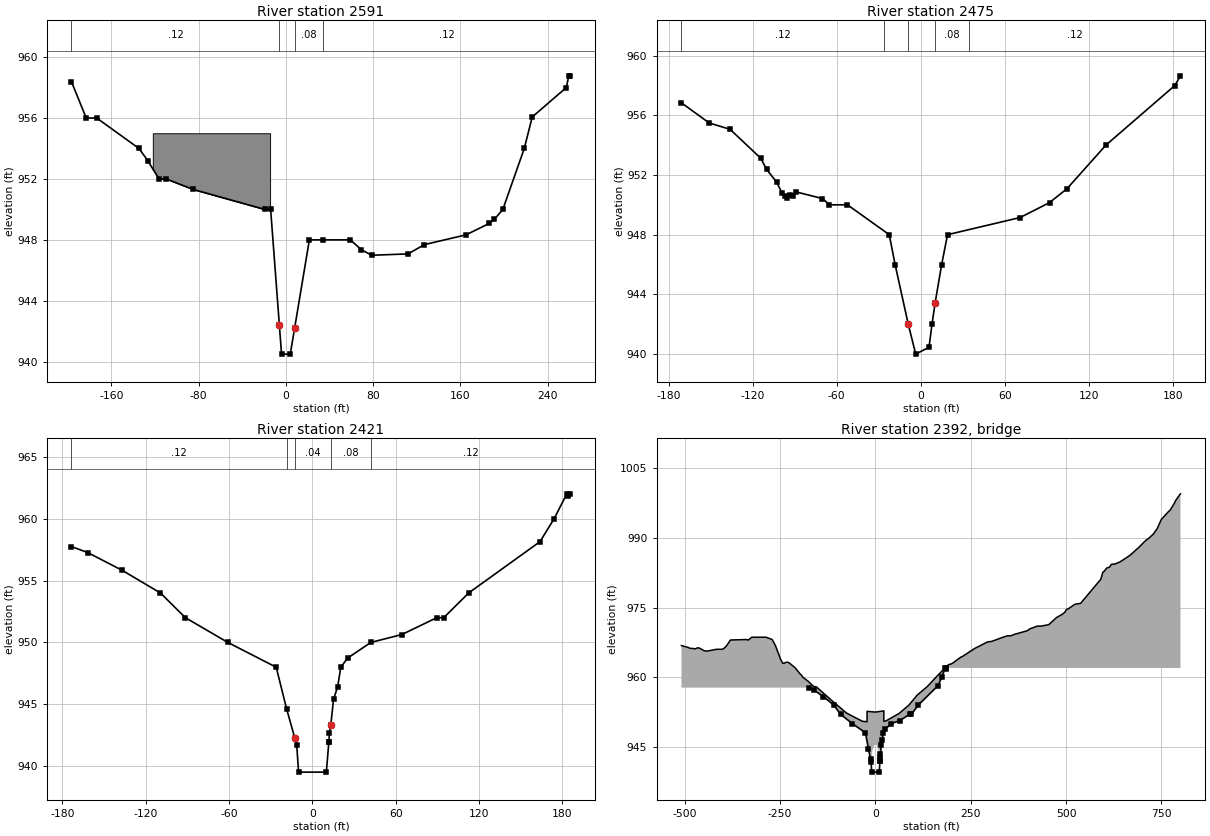
Type RM Length L Ch R = 1 ,2591    ,122.07,116,107.64
BEGIN DESCRIPTION:
Channel from MUB HEC-RAS
END DESCRIPTION:
XS GIS Cut Line= 4
587877.4690495594390792.37299366587914.7247540194390786.23432159
587935.9845542824390793.26300967588008.7037391814390824.75799406
#Sta/Elev= 30
-196.522  958.38-183.005     956-173.392     956-134.613     954-126.411  953.18
-116.371     952-109.711     952 -84.908  951.31 -19.357     950     -14     950
      -6   942.4      -4   940.5       4   940.5       8 942.215   21.49     948
  33.793     948  58.957     948   69.16  947.36  78.543  946.99 111.942  947.08
 126.903  947.69 165.059  948.33 186.385  949.08 190.978  949.34 198.819     950
 218.438     954 225.755  956.07 256.988     958 259.252  958.76 260.827  958.77
#Mann= 4 ,-1 , 0
-196.522     .12       0      -6     .04       0       8     .08       0
  33.793     .12       0
#Block Obstruct= 1 ,-1
    -122   -14.5     955
Bank Sta=-6,8
XS Rating Curve= 0 ,0
Exp/Cntr=0.3,0.1

Type RM Length L Ch R = 1 ,2475    ,42.77,54,65.79
XS GIS Cut Line= 4
587890.593737721 4390811.2126819587917.6874100564390825.60533807
587950.7063944644390828.35768211587990.5010829564390848.88901036
#Sta/Elev= 30
-170.833  956.83-150.984  955.48-136.155  955.06-114.337  953.13-110.072  952.38
-102.756   951.5  -99.18  950.82 -97.047  950.56 -95.308  950.49 -93.241  950.65
 -91.339  950.56 -89.239  950.87 -70.177  950.42 -65.157     950 -52.297     950
 -22.474     948 -18.307     946  -8.957  942.02  -3.576     940   5.906  940.46
   8.038     942  10.302  943.45  14.928     946  19.127     948  70.997  949.15
  91.962  950.15 104.429  951.08 132.218     954 181.398  957.99 185.433  958.64
#Mann= 5 ,-1 , 0
-170.833     .12       0 -26.214     .08       0  -8.957     .04       0
  10.302     .08       0  34.383     .12       0
Bank Sta=-8.957,10.302
XS Rating Curve= 0 ,0
Exp/Cntr=0.5,0.3

Type RM Length L Ch R = 1 ,2421    ,56.784,57,56.723
BEGIN DESCRIPTION:
Channel invert from MUB HEC-RAS
END DESCRIPTION:
XS GIS Cut Line= 2
587889.5909457094390817.75368998587985.4749308944390870.67001863
#Sta/Elev= 30
-173.524  957.74-161.877  957.26-136.975  955.82-109.547     954 -91.503     952
 -60.925     950 -26.115     948 -18.537   944.6 -12.795  942.31  -11.34   941.7
     -10  939.53      10  939.53  11.811     942  11.942     942  12.106  942.67
  13.189  943.33  15.157   945.4   18.11  946.42  20.407     948  25.328  948.74
  41.995     950  64.403  950.64  89.501     952  94.521     952 112.533     954
 163.845  958.14 174.049     960 183.136     962 183.858  961.81 185.794  961.98
#Mann= 5 ,-1 , 0
-173.524     .12       0 -18.537     .08       0 -12.795     .04       0
  13.189     .08       0  41.995     .12       0
Bank Sta=-12.795,13.189
XS Rating Curve= 0 ,0
Exp/Cntr=0.5,0.3

Type RM Length L Ch R = 3 ,2392    ,,,
BEGIN DESCRIPTION:
Martin Street (structure from MUB HEC-RAS model)
END DESCRIPTION:
Bridge Culvert--1,0,-1,-1, 0
Deck Dist Width WeirC Skew NumUp NumDn MinLoCord MaxHiCord MaxSubmerge Is_Ogee
15,34,2.8,0, 112, 112, 950.22, , 0.95, 0, 0,0,,
  -508.8  -491.3  -485.9  -481.7  -472.1  -467.3  -462.7  -449.4  -442.5  -416.7
    -403  -398.8    -391  -380.4  -339.8  -332.8  -324.6  -304.1  -286.9  -270.8
  -262.3  -251.7  -249.7  -243.3  -238.9  -234.8  -228.8  -223.6  -210.4  -198.8
  -193.9  -190.6  -176.4  -162.3  -154.7  -113.9   -75.6   -34.2  -22.01     -22
     -10   -9.95   -9.78   -9.16   -8.23   -3.22       0    3.22    8.23    9.16
    9.78    9.95      10      22   22.01    27.3    62.4      88   109.1   136.4
     159   182.7   191.7   197.3   202.3   223.7   227.2   260.7   294.3     305
   337.6   342.4   345.7   350.9   354.9     364   398.1     405   421.2   424.8
   434.5   454.4   474.3   491.1     497   501.2   505.3   523.1   538.1   591.1
   596.4   599.8   606.6   613.7   618.7   629.3   634.6   640.6   648.4   668.4
   691.2   708.1   717.8   728.6   738.9   749.9   768.9     773   784.9   786.9
   798.8     800
   966.8   966.4   966.2   966.2   966.1   966.3   966.3   965.7   965.6     966
     966   966.1   966.7     968   968.1     968   968.6   968.6   968.6   968.1
   966.8   964.5     964     963     963   963.2   963.2   962.9     962   960.8
   960.4     960   959.1     958  957.89  954.91  952.25  950.48950.3873952.6373
 952.546952.5457952.5444952.5396952.5326952.4945  952.47952.5089952.5695952.5807
952.5882952.5903952.5909 952.736950.4859  950.55   952.2     954   956.1     958
     960     962   962.7   962.8     963   964.3   964.4   966.2   967.6   967.7
   968.7   968.8   968.9   968.9   968.9   969.2     970   970.4   970.9     971
     971   971.3   972.8   973.6     974   974.6   974.7   975.7   975.9   981.1
   982.6   982.8   983.5   983.7   984.3   984.4   984.6   984.8   985.2   986.3
     988   989.4     990   990.8     992     994   995.7     996   997.6     998
   999.4   999.5
                                                                                
                                                                                
                                                                                
                                                                                
  939.53  941.97  942.52  943.48  944.14  945.32  945.53  945.32  944.14  943.48
  942.52  941.97  939.53
                                                                                
                                                                                
                                                                                
                                                                                
                                                                                
                
  -508.8  -491.3  -485.9  -481.7  -472.1  -467.3  -462.7  -449.4  -442.5  -416.7
    -403  -398.8    -391  -380.4  -339.8  -332.8  -324.6  -304.1  -286.9  -270.8
  -262.3  -251.7  -249.7  -243.3  -238.9  -234.8  -228.8  -223.6  -210.4  -198.8
  -193.9  -190.6  -176.4  -162.3  -154.7  -113.9   -75.6   -34.2  -22.01     -22
     -10   -9.95   -9.78   -9.16   -8.23   -3.22       0    3.22    8.23    9.16
    9.78    9.95      10      22   22.01    27.3    62.4      88   109.1   136.4
     159   182.7   191.7   197.3   202.3   223.7   227.2   260.7   294.3     305
   337.6   342.4   345.7   350.9   354.9     364   398.1     405   421.2   424.8
   434.5   454.4   474.3   491.1     497   501.2   505.3   523.1   538.1   591.1
   596.4   599.8   606.6   613.7   618.7   629.3   634.6   640.6   648.4   668.4
   691.2   708.1   717.8   728.6   738.9   749.9   768.9     773   784.9   786.9
   798.8     800
   966.8   966.4   966.2   966.2   966.1   966.3   966.3   965.7   965.6     966
     966   966.1   966.7     968   968.1     968   968.6   968.6   968.6   968.1
   966.8   964.5     964     963     963   963.2   963.2   962.9     962   960.8
   960.4     960   959.1     958  957.89  954.91  952.25  950.48950.3873952.6373
 952.546952.5457952.5444952.5396952.5326952.4945  952.47952.5089952.5695952.5807
952.5882952.5903952.5909 952.736950.4859  950.55   952.2     954   956.1     958
     960     962   962.7   962.8     963   964.3   964.4   966.2   967.6   967.7
   968.7   968.8   968.9   968.9   968.9   969.2     970   970.4   970.9     971
     971   971.3   972.8   973.6     974   974.6   974.7   975.7   975.9   981.1
   982.6   982.8   983.5   983.7   984.3   984.4   984.6   984.8   985.2   986.3
     988   989.4     990   990.8     992     994   995.7     996   997.6     998
   999.4   999.5
                                                                                
                                                                                
                                                                                
                                                                                
  939.53  941.97  942.52  943.48  944.14  945.32  945.53  945.32  944.14  943.48
  942.52  941.97  939.53
                                                                                
                                                                                
                                                                                
                                                                                
                                                                                
                
BR Coef=-1 , 1 , 0 ,, 0 ,,,0.8,0,1.2,0,
WSPro=,,,, 1 ,,,, 0 ,,,, 0 ,,,,-1 ,-1 ,-1 , 0 , 0 , 0 , 0 , 0
BC Design=,, 0 ,, 0 ,,,,,,
BC Use User HTab Curves=0
BC User HTab FreeFlow(D)= 0