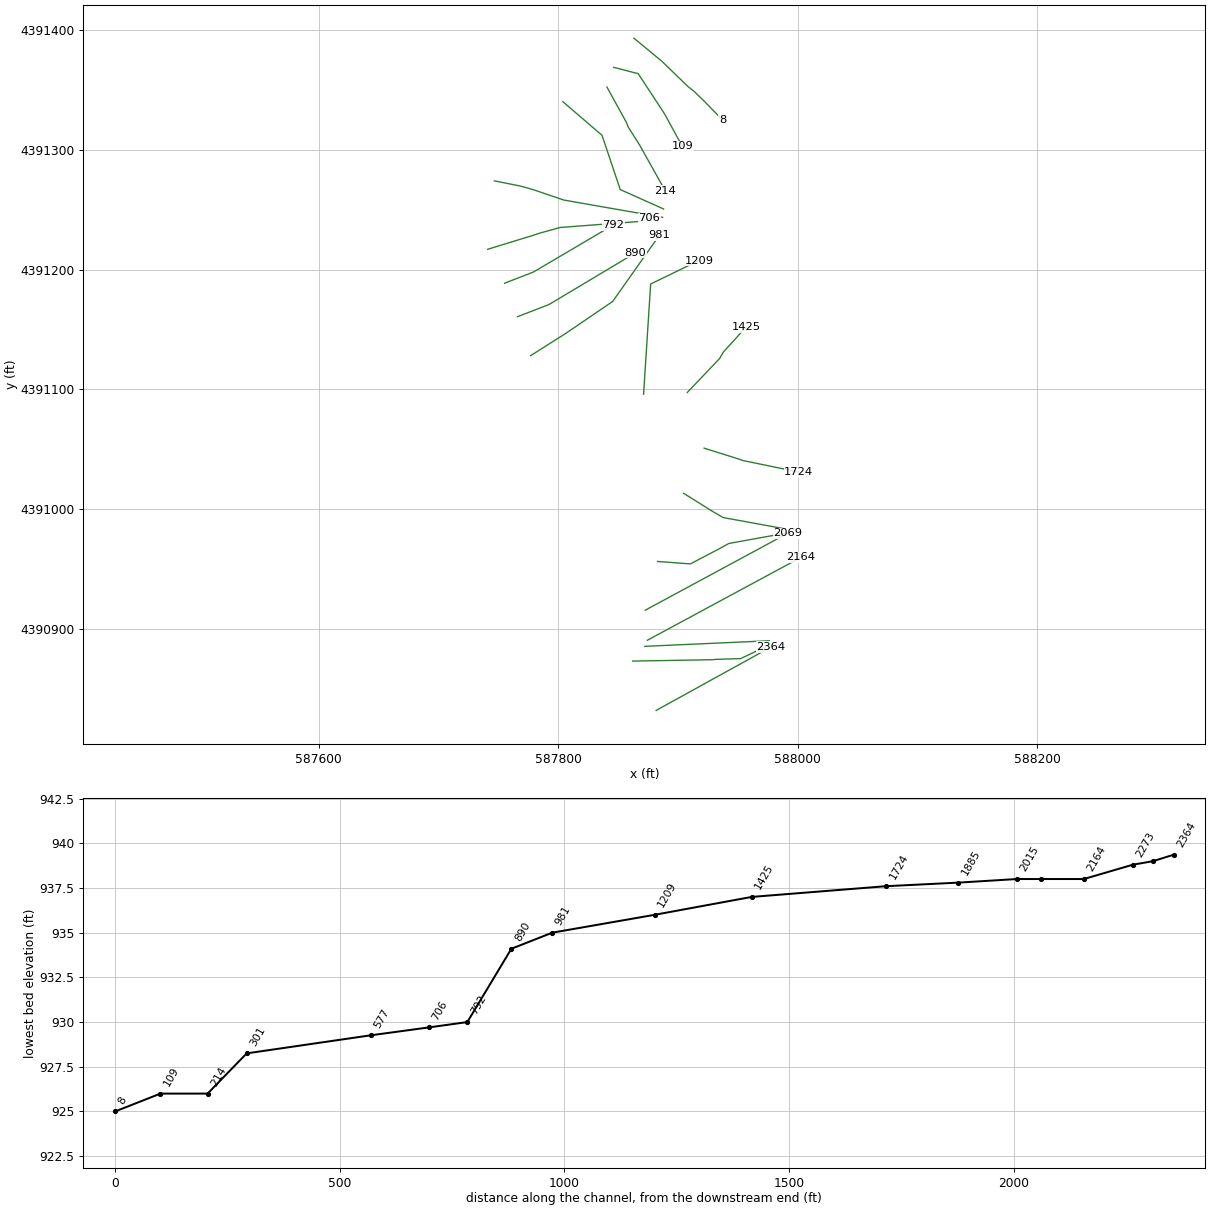
HEC-RAS study BurroughsRun.prj: Burroughs Run

--- BurroughsRun.g01 (geometry) --- (continued)

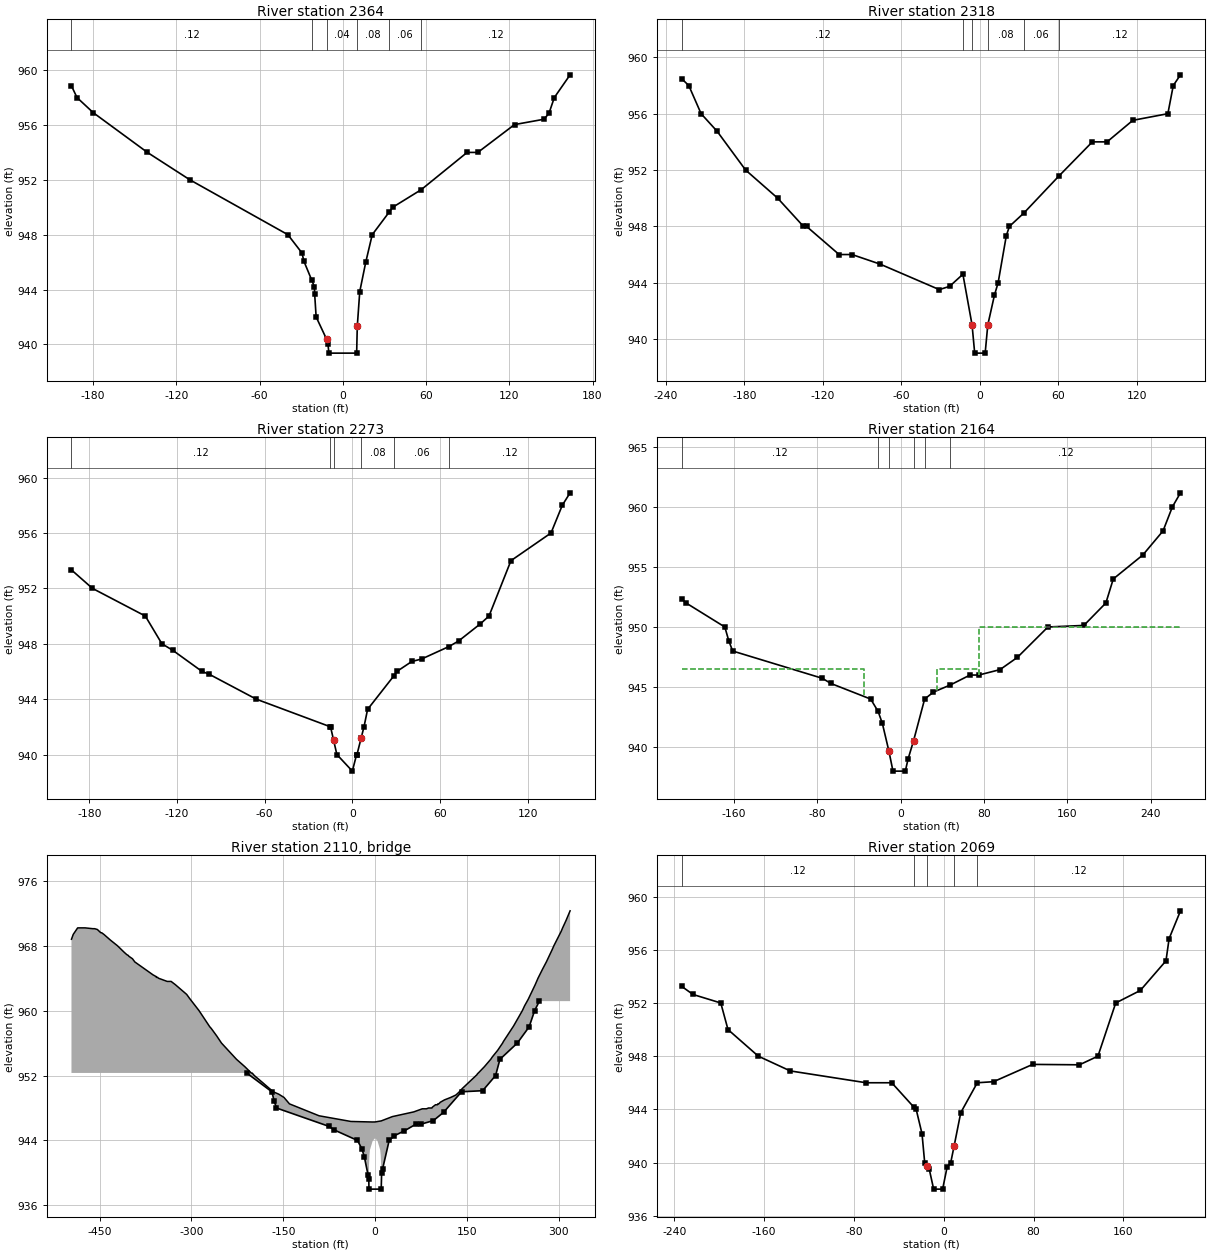
Type RM Length L Ch R = 1 ,2364    ,58.62,46,33.41
BEGIN DESCRIPTION:
Channel invert from MUB HEC-RAS
END DESCRIPTION:
XS GIS Cut Line= 2
587881.8612176134390831.76229815587977.745202798 4390884.6786268
#Sta/Elev= 30
-195.505  958.85-191.503     958-179.823   956.9-140.781     954-110.138     952
 -39.567     948 -29.429  946.67 -27.953  946.05  -22.31  944.67 -20.407  944.19
 -20.276   943.7 -19.193     942 -11.647  940.37  -10.69  940.03     -10  939.36
      10  939.36   10.45  941.31  12.238  943.85  16.568     946  21.227     948
  33.235  949.62  35.991     950  56.496  951.28    89.6     954   97.31     954
 123.753  956.03  144.98  956.42 148.589  956.85 152.428     958 163.812  959.66
#Mann= 6 ,-1 , 0
-195.505     .12       0  -22.31     .08       0 -11.647     .04       0
   10.45     .08       0  33.235     .06       0  56.496     .12       0
Bank Sta=-11.647,10.45
XS Rating Curve= 0 ,0
Exp/Cntr=0.5,0.3

Type RM Length L Ch R = 1 ,2318    ,44.92,45,45.26
XS GIS Cut Line= 6
 587862.152849374390872.97125866587928.6571621924390874.12035467
587930.4981542144390874.27885068587932.3391462374390874.43734668
587952.3980344854390875.02561068587975.6847547734390886.14166682
#Sta/Elev= 30
-227.657  958.47-222.375     958-212.959     956-200.722  954.75 -178.97     952
-154.462     950 -134.81     948-132.448     948-107.546     946 -97.703     946
 -76.247  945.32 -31.037  943.51  -23.19  943.74     -13   944.6      -6     941
      -4     939       4     939       6     941  11.122  943.13  13.911     944
  20.177  947.35  22.539     948  33.596  948.95  60.171  951.56   85.86     954
  97.113     954 116.798  955.53 143.537     956 147.671     958 153.182  958.76
#Mann= 6 ,-1 , 0
-227.657     .12       0     -13     .08       0      -6     .04       0
       6     .08       0  33.596     .06       0  60.171     .12       0
Bank Sta=-6,6
XS Rating Curve= 0 ,0
Exp/Cntr=0.3,0.1

Type RM Length L Ch R = 1 ,2273    ,94.59,109,123.44
XS GIS Cut Line= 2
587872.3910814964390885.29432281587976.3187387814390889.95166687
#Sta/Elev= 30
-192.257  953.33 -177.92     952-141.699     950-130.381     948-122.835  947.52
-102.887     946 -97.835  945.79 -65.814     944 -15.223  942.01 -14.928     942
 -12.795  941.02 -10.597     940       0   938.8    2.92     940   3.182     940
   5.971  941.17   7.972     942  10.433  943.26  28.412  945.68  30.479     946
  40.715  946.72  47.474   946.9  66.175   947.8  72.736   948.2  87.533  949.43
  93.537     950 108.563     954 135.991     956 143.701     958 149.049   958.9
#Mann= 6 ,-1 , 0
-192.257     .12       0 -15.223     .08       0 -12.795     .04       0
   5.971     .08       0  28.412     .06       0  66.175     .12       0
Bank Sta=-12.795,5.971
XS Rating Curve= 0 ,0
Exp/Cntr=0.5,0.3

Type RM Length L Ch R = 1 ,2164    ,94.872,95,92.746
XS GIS Cut Line= 2
587874.5063935224390890.37533887588002.8150031084390959.58017973
#Sta/Elev= 30
-209.843  952.32-205.807     952-168.635     950-164.829  948.85-161.122     948
 -75.164  945.73 -66.929   945.3  -28.74     944 -21.588  942.97  -17.52  941.97
 -11.286  939.68  -7.349     938   4.495     938   7.119     939  12.434  940.54
  23.031     944  31.463  944.58  47.835  945.18  66.568     946  74.967     946
  95.308  946.45 112.008  947.47 141.273     950 175.755  950.13 196.883     952
  203.97     954 232.382     956 251.706     958 260.663     960 268.438  961.17
#Mann= 6 ,-1 , 0
-209.843     .12       0 -21.588     .08       0 -11.286     .04       0
  12.434     .08       0  23.031     .06       0  47.835     .12       0
#XS Ineff= 3 ,-1
-209.843     -35   946.5      35      75   946.5      75 268.438     950
Permanent Ineff=
       F       F       F
Bank Sta=-11.286,12.434
XS Rating Curve= 0 ,0
Exp/Cntr=0.5,0.3

Type RM Length L Ch R = 3 ,2110    ,,,
BEGIN DESCRIPTION:
Valley Road (structure from MUB HEC-RAS model)
END DESCRIPTION:
Bridge Culvert--1,0,-1,-1, 0
Deck Dist Width WeirC Skew NumUp NumDn MinLoCord MaxHiCord MaxSubmerge Is_Ogee
26,57,2.8,0, 135, 135, , , 0.98, 0, 0,0,,
    -496  -493.2  -493.2  -493.1  -485.9  -485.4  -484.9  -481.2  -473.8  -461.3
  -458.2  -453.7  -449.3  -448.1  -446.7  -443.1  -432.5  -420.9    -410  -405.6
  -403.2  -402.2  -400.4  -398.4  -396.4  -392.5  -362.6  -360.1  -358.1  -357.5
  -357.1  -356.8  -356.2    -356  -355.2  -354.1  -339.6  -336.5  -336.3  -335.8
  -335.7  -333.2  -329.7  -326.3  -307.8    -303  -287.6  -278.9    -270  -267.6
  -258.9  -250.9  -232.7  -226.4  -212.9  -202.1  -200.7  -197.3  -184.8  -166.4
  -157.3  -148.8  -139.9   -91.5   -39.5     -10   -9.88   -9.16   -8.48   -8.23
    -7.3   -3.86       0    3.86    8.23    8.48    9.16     9.4    9.88      10
    28.3    63.2    77.1    78.5    81.5    83.1    83.9    87.3    92.1    92.9
    93.6    98.7   100.8   101.9   102.4   103.1   103.7   105.3   106.4   113.4
   123.5     132     135   137.7   142.5   164.8   166.2   166.4   167.1   169.8
   178.7   188.9   191.6   200.2   208.3   209.7   225.4   226.2   240.6   244.3
   250.2     254   261.6   266.2   273.5   279.8   289.2   292.1   301.6   304.2
   305.3   306.4   311.9   316.8   318.6
   968.8   969.4   969.4   969.4   970.2   970.2   970.2   970.2   970.2   970.1
   970.1     970   969.7   969.6   969.6   969.4   968.7     968   967.2   966.9
   966.8   966.7   966.6   966.5   966.4     966   964.4   964.3   964.2   964.2
   964.1   964.1   964.1   964.1   964.1     964   963.6   963.6   963.6   963.6
   963.6   963.6   963.4   963.2     962   961.5     960     959     958   957.8
   956.9     956   954.5     954   953.1   952.3   952.3     952   951.2     950
   949.7   949.3  948.51  947.04  946.34946.2759946.2756 946.274946.2726 946.272
  946.27946.2747  946.28946.3252946.3763946.3792946.3872  946.39 946.404946.4075
  946.94  947.52   947.9   947.9   947.9   947.9   947.9     948     948     948
   948.1   948.4   948.4   948.4   948.5   948.5   948.5   948.6   948.7     949
   949.3   949.6   949.8     950   950.4     952   952.1   952.1   952.2   952.4
   953.1     954   954.3   955.1     956   956.2     958   958.1     960   960.6
   961.4     962   963.2     964   965.1     966   967.5     968   969.4   969.8
     970   970.2   971.1     972   972.3
                                                                                
                                                                                
                                                                                
                                                                                
                                                                                
                                                                                
                                          938.26  940.98  942.21  942.74  942.87
 943.102  943.96  944.26  943.96  942.87  942.74  942.21   941.8  940.98  938.26
                                                                                
                                                                                
                                                                                
                                                                                
                                                                                
                                        
    -496  -493.2  -493.2  -493.1  -485.9  -485.4  -484.9  -481.2  -473.8  -461.3
  -458.2  -453.7  -449.3  -448.1  -446.7  -443.1  -432.5  -420.9    -410  -405.6
  -403.2  -402.2  -400.4  -398.4  -396.4  -392.5  -362.6  -360.1  -358.1  -357.5
  -357.1  -356.8  -356.2    -356  -355.2  -354.1  -339.6  -336.5  -336.3  -335.8
  -335.7  -333.2  -329.7  -326.3  -307.8    -303  -287.6  -278.9    -270  -267.6
  -258.9  -250.9  -232.7  -226.4  -212.9  -202.1  -200.7  -197.3  -184.8  -166.4
  -157.3  -148.8  -139.9   -91.5   -39.5     -10   -9.88   -9.16   -8.48   -8.23
    -7.3   -3.86       0    3.86    8.23    8.48    9.16     9.4    9.88      10
    28.3    63.2    77.1    78.5    81.5    83.1    83.9    87.3    92.1    92.9
    93.6    98.7   100.8   101.9   102.4   103.1   103.7   105.3   106.4   113.4
   123.5     132     135   137.7   142.5   164.8   166.2   166.4   167.1   169.8
   178.7   188.9   191.6   200.2   208.3   209.7   225.4   226.2   240.6   244.3
   250.2     254   261.6   266.2   273.5   279.8   289.2   292.1   301.6   304.2
   305.3   306.4   311.9   316.8   318.6
   968.8   969.4   969.4   969.4   970.2   970.2   970.2   970.2   970.2   970.1
   970.1     970   969.7   969.6   969.6   969.4   968.7     968   967.2   966.9
   966.8   966.7   966.6   966.5   966.4     966   964.4   964.3   964.2   964.2
   964.1   964.1   964.1   964.1   964.1     964   963.6   963.6   963.6   963.6
   963.6   963.6   963.4   963.2     962   961.5     960     959     958   957.8
   956.9     956   954.5     954   953.1   952.3   952.3     952   951.2     950
   949.7   949.3  948.51  947.04  946.34946.2759946.2756 946.274946.2726 946.272
  946.27946.2747  946.28946.3252946.3763946.3792946.3872  946.39 946.404946.4075
  946.94  947.52   947.9   947.9   947.9   947.9   947.9     948     948     948
   948.1   948.4   948.4   948.4   948.5   948.5   948.5   948.6   948.7     949
   949.3   949.6   949.8     950   950.4     952   952.1   952.1   952.2   952.4
   953.1     954   954.3   955.1     956   956.2     958   958.1     960   960.6
   961.4     962   963.2     964   965.1     966   967.5     968   969.4   969.8
     970   970.2   971.1     972   972.3
                                                                                
                                                                                
                                                                                
                                                                                
                                                                                
                                                                                
                                          938.26  940.98  942.21  942.74  942.87
 943.102  943.96  944.26  943.96  942.87  942.74  942.21   941.8  940.98  938.26
                                                                                
                                                                                
                                                                                
                                                                                
                                                                                
                                        
BR Coef=-1 , 1 , 0 ,, 0 ,,,0.8,0,1.2,0,
WSPro=,,,, 1 ,,,, 0 ,,,, 0 ,,,,-1 ,-1 ,-1 , 0 , 0 , 0 , 0 , 0
BR U #Sta/Elev= 30
-209.843  952.32-168.635     950-164.829  948.85-161.122     948 -75.164  945.73
 -66.929   945.3  -28.74     944 -21.588  942.97  -17.52  941.97 -11.286  939.68
 -10.269  939.23     -10     938      10     938  10.696     940  12.434  940.54
  23.031     944  31.463  944.58  47.835  945.18  66.568     946  74.967     946
  95.308  946.45 112.008  947.47 141.273     950 175.755  950.13 196.883     952
  203.97     954 232.382     956 251.706     958 260.663     960 268.438  961.17
BR U #Mann= 6
-209.843     .12 -21.588     .08 -11.286     .04  12.434     .08  23.031     .06
  47.835     .12
BR D #Sta/Elev= 192
-233.366  953.24-232.382   953.2-232.119  953.18-231.824  953.17-231.562  953.16
-231.266  953.16-230.971  953.15-230.709  953.14-230.413  953.13-230.118  953.13
-228.543   953.1-227.461  953.08-223.458  952.64-221.916  952.62-220.341   952.6
-218.734  952.59-216.962  952.57-215.715  952.48-202.329     952-202.001     952
 -201.64     952-201.312     952-200.951     952-198.688     952-194.062  950.57
-192.257     950-186.778  949.55 -186.45  949.52-186.089   949.5-185.892  949.49
-185.663  949.47-185.433  949.45-184.974  949.42-184.744   949.4-184.285  949.36
-184.022  949.35-183.858  949.33-183.432   949.3-183.268  949.29-183.071  949.27
-182.677  949.25-182.251  949.21-181.594  949.17-181.168  949.14-180.741   949.1
-180.249  949.07-179.724  949.03-179.331  948.99 -178.74  948.95-178.117  948.91
-177.756  948.88-177.395  948.85-177.034  948.82-176.115  948.76-175.098  948.69
-173.983  948.61-172.703  948.52-169.423  948.25-165.256     948-150.755  947.47
-139.534  946.98-136.778  946.89-126.017   946.8-125.853   946.8-125.722  946.81
-125.656  946.81-124.672  946.85-124.114  946.86-123.064   946.8-122.474  946.82
-121.916  946.84-116.273   946.9-115.551  946.88-115.354  946.88 -115.19  946.88
-114.993  946.88-114.075  946.88-112.073  946.87-111.352  946.84-110.105  946.84
-102.198  946.64-100.755  946.63 -99.344  946.62 -98.786  946.62  -97.31  946.61
 -96.818   946.6 -83.694  946.49 -83.268  946.47 -80.184  946.45  -69.16     946
 -66.634     946 -64.009     946 -63.615     946 -60.958     946  -59.81     946
  -55.84     946 -47.474     946 -47.408     946 -47.343     946 -47.244     946
 -47.178     946  -47.08     946 -46.982     946 -46.916     946 -46.654     946
 -46.621     946 -46.325     946 -26.378  944.14 -25.623  944.07 -24.869     944
  -24.77     944 -24.738     944 -24.705     944 -24.672     944 -24.639     944
 -24.606     944 -24.573     944 -23.392  943.54 -23.327  943.53 -23.097  943.45
 -23.064  943.42 -22.999   943.4 -22.933  943.38 -22.835  943.35 -22.769  943.32
 -22.605  943.26 -20.407  942.51 -19.357  942.16 -19.094     942 -18.898  941.73
 -18.799  941.63 -17.979  940.88 -16.995     940 -15.945  939.87 -14.797  939.72
 -13.812   939.6 -12.894  939.49     -10     938  -8.858     938  -6.102     938
    .295     938   3.051     938   6.234     938   7.612     938   9.285     938
      10     938   10.55   940.3   11.22  942.07  13.419  942.98  14.928  943.64
  15.059   943.7  15.157  943.75  17.651  944.29  29.888     946  35.302     946
  36.385     946  37.041     946   44.39  946.08  79.232  947.38  85.007  947.44
  99.705  947.21 102.034  947.25 102.559  947.23  105.02  947.26 105.577  947.24
 108.169  947.28 109.318  947.24 111.975  947.27 117.618  947.32 118.701  947.33
 119.783  947.34 120.932  947.35  122.08  947.37 132.316  947.71 137.402     948
  143.11  949.41 144.455  949.75  145.44     950 146.129  950.17 153.248     952
 155.052  952.16 155.085  952.16 155.479  952.19 155.545  952.19 158.924  952.44
 163.255  952.48 175.131  952.94 198.031  955.17 199.114  955.81 199.442     956
  200.82  956.84 210.958  958.93
BR D #Mann= 5
-233.366     .12 -26.378     .06 -12.894     .04   10.55     .06  29.888     .12
BR D Banks=-12.894,10.55
BC Design=,, 0 ,, 0 ,,,,,,
BC Use User HTab Curves=0
BC User HTab FreeFlow(D)= 0

Type RM Length L Ch R = 1 ,2069    ,57.06,54,53.1
BEGIN DESCRIPTION:
Channel invert from MUB HEC-RAS
END DESCRIPTION:
XS GIS Cut Line= 2
  587872.72026554390915.47257118587991.8879229734390979.81889998
#Sta/Elev= 30
-233.366  953.24-223.458  952.64-198.688     952-192.257     950-165.256     948
-136.778  946.89  -69.16     946 -46.325     946 -26.378  944.14 -24.573     944
 -19.357  942.16 -16.995     940 -14.797  939.72 -12.894  939.49      -9     938
      -1     938   3.051  939.68   6.234     940   9.285  941.26  15.157  943.75
  29.888     946   44.39  946.08  79.232  947.38 120.932  947.35 137.402     948
 153.248     952 175.131  952.94 198.031  955.17  200.82  956.84 210.958  958.93
#Mann= 5 ,-1 , 0
-233.366     .12       0 -26.378     .06       0 -14.797     .04       0
   9.285     .06       0  29.888     .12       0
#XS Ineff= 2 ,-1
-233.366     -35   944.7      35 210.958   944.7
Permanent Ineff=
       F       F
Bank Sta=-14.797,9.285
XS Rating Curve= 0 ,0
Exp/Cntr=0.5,0.3

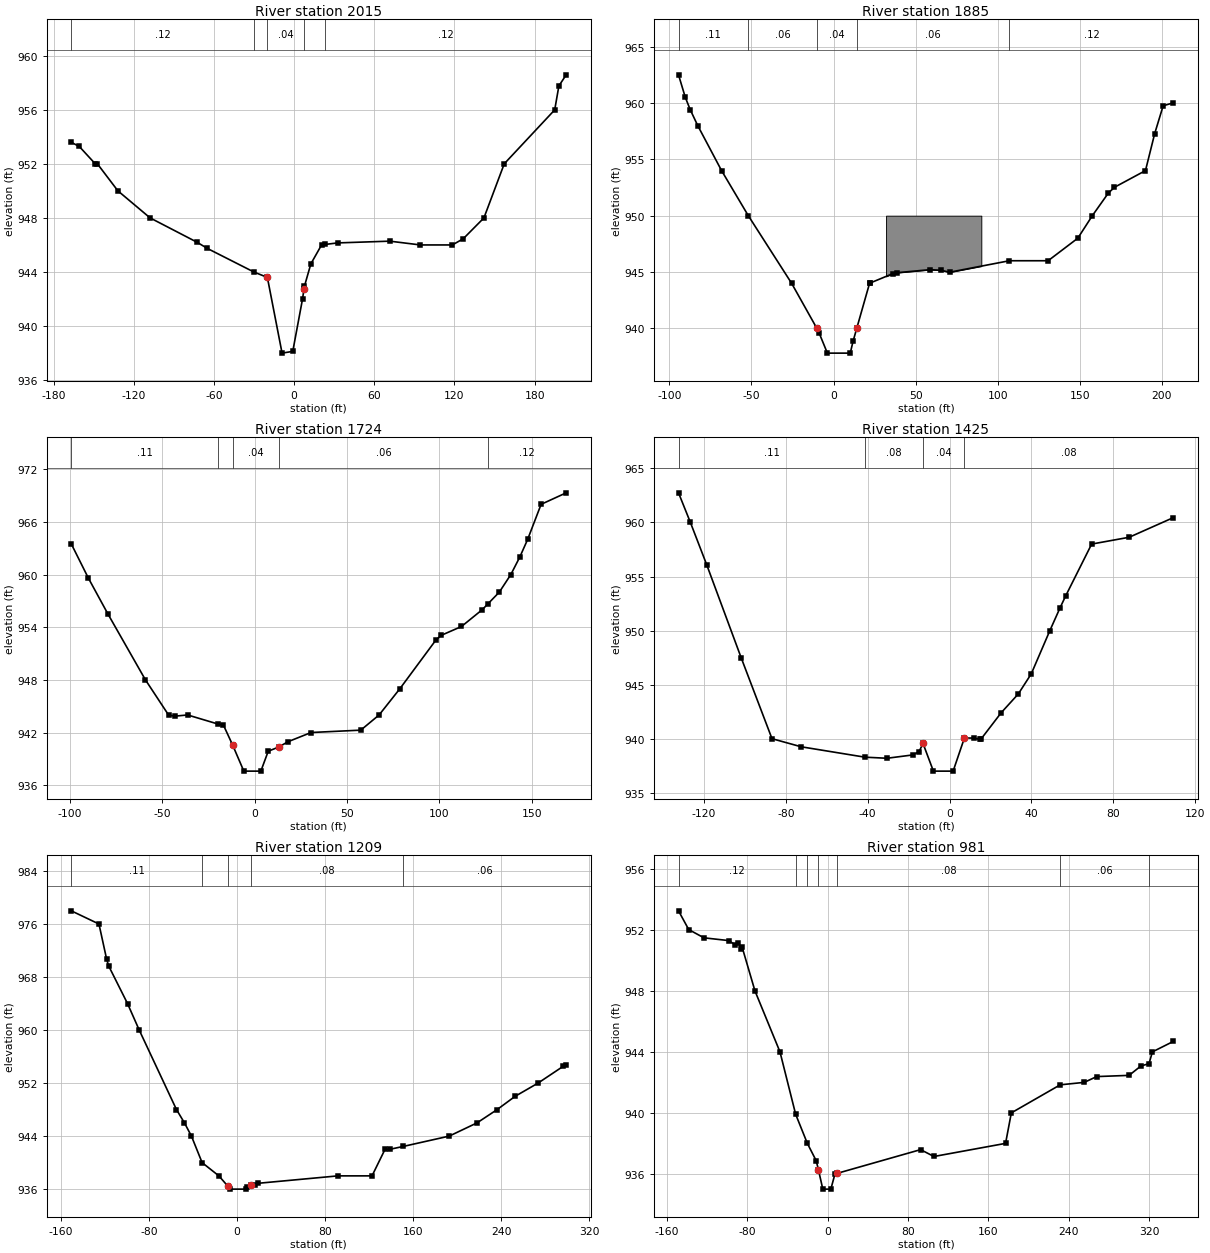
Type RM Length L Ch R = 1 ,2015    ,157.7,130,102.71
XS GIS Cut Line= 6
587882.9737376274390956.20299569587910.4697459674390954.12730766
587926.5906181664390962.62817977587933.8540022564390966.40769981
587942.6627223654390971.23268387587990.7113949594390979.91033998
#Sta/Elev= 28
-166.699  953.59-160.696  953.28-148.786     952-147.178     952-131.824     950
-107.743     948 -72.605   946.2 -64.862  945.74 -30.118     944     -20   943.6
      -9     938      -1  938.13   6.299     942   7.382  942.72   7.743  942.95
  12.533   944.6  20.538     946  23.458  946.04  32.513  946.15  71.588  946.28
  94.488     946 118.406     946 126.575  946.46 142.028     948 157.218     952
  194.98  955.99 198.097  957.76 203.576  958.58
#Mann= 5 ,-1 , 0
-166.699     .12       0 -30.118     .06       0     -20     .04       0
   7.382     .06       0  23.458     .12       0
Bank Sta=-20,7.382
XS Rating Curve= 0 ,0
Exp/Cntr=0.3,0.1

Type RM Length L Ch R = 1 ,1885    ,156.09,161,168.16
XS GIS Cut Line= 5
587904.7760818964391013.14268439 587928.553530194390998.28063621
587933.1377222474390995.58620417587937.7219143044390992.89177214
 587990.037786954390983.33019602
#Sta/Elev= 30
  -94.39   962.5 -90.256   960.5 -87.303  959.42  -82.71     958 -68.176     954
 -51.903     950 -25.525     944 -10.269  940.03  -8.858  939.62   -3.74   937.8
  10.203   937.8  11.877  938.84   14.14     940  21.949     944  22.244  944.02
  36.024  944.85   38.78  944.94  58.989  945.21   65.65  945.15  70.669  944.98
 107.119     946 130.676     946 148.753     948 157.612     950 167.323     952
 171.096  952.52 189.961     954 195.571  957.28 200.722  959.75 206.988  960.02
#Mann= 5 ,-1 , 0
  -94.39     .11       0 -51.903     .06       0 -10.269     .04       0
   14.14     .06       0 107.119     .12       0
#Block Obstruct= 1 ,-1
      32      90     950
Bank Sta=-10.269,14.14
XS Rating Curve= 0 ,0
Exp/Cntr=0.3,0.1

Type RM Length L Ch R = 1 ,1724    ,268.32,299,331.62
XS GIS Cut Line= 5
587921.9210821084391050.81901286587947.4206504244391042.83934876
587950.9167064674391041.67196474 587954.412762514391040.50153273
588000.9679150854391030.86375661
#Sta/Elev= 30
 -99.245  963.49 -89.993  959.59 -79.462  955.52 -59.121     948 -46.621     944
  -43.35  943.86   -36.3     944  -19.76  942.96  -16.99  942.88     -12 940.603
   -5.88   937.6    3.34   937.6    7.33  939.87  12.959  940.34  18.012  940.95
  30.512     942  57.415  942.27  67.323     944  78.642  947.01  97.999  952.52
 100.919  953.07 111.909  954.08 123.163     956 126.312  956.68 132.382     958
 138.615     960 143.471     962 147.703     964 154.987     968  168.57  969.31
#Mann= 5 ,-1 , 0
 -99.245     .11       0  -19.76     .06       0     -12     .04       0
  12.959     .06       0 126.312     .12       0
Bank Sta=-12,12.959
XS Rating Curve= 0 ,0
Exp/Cntr=0.3,0.1

Type RM Length L Ch R = 1 ,1425    ,198.22,216,230.49
XS GIS Cut Line= 5
587907.8698019354391097.34368543587934.9299462694391125.80895778
587936.4691862884391128.45766982587938.0084263074391131.10638185
587957.0309945424391152.06443011
#Sta/Elev= 26
-132.415  962.74-126.608     960-118.668   956.1-101.772  947.47 -86.745     940
 -72.441  939.25 -41.339  938.29 -30.545  938.19  -17.88   938.5  -14.89  938.81
  -12.96  939.56   -7.89     937    1.75     937    7.25  940.06   11.89  940.06
   14.65  939.94  15.518     940   25.23   942.4  33.596  944.14  39.928     946
  49.016     950  54.003  952.11  56.693  953.19  69.423     958  87.762  958.63
 109.383  960.45
#Mann= 4 ,-1 , 0
-132.415     .11       0 -41.339     .08       0  -12.96     .04       0
    7.25     .08       0
Bank Sta=-12.96,7.25
XS Rating Curve= 0 ,0
Exp/Cntr=0.3,0.1

Type RM Length L Ch R = 1 ,1209    ,252.06,228,203.94
XS GIS Cut Line= 3
587871.3334254834391095.90502941587877.2587375564391187.97901455
587917.4740500534391207.45268679
#Sta/Elev= 30
-150.426  977.99-125.295     976-118.373  970.72-116.568   969.7 -99.377     964
 -88.747     960 -54.921     948 -47.703     946 -41.339     944  -31.66     940
 -16.437     938  -8.432  936.47  -5.938     936   8.563     936   9.186  936.35
  12.828  936.68  16.043  936.69   19.16  936.88  91.699     938 122.605     938
 134.383     942 138.615     942 151.148  942.45 192.684     944 217.979     946
 236.155     948 252.493     950 273.327     952 295.965  954.51 298.885  954.66
#Mann= 5 ,-1 , 0
-150.426     .11       0  -31.66     .08       0  -8.432     .04       0
  12.828     .08       0 151.148     .06       0
Bank Sta=-8.432,12.828
XS Rating Curve= 0 ,0
Exp/Cntr=0.3,0.1

Type RM Length L Ch R = 1 ,981     ,92.51,91,89.49
XS GIS Cut Line= 4
587776.9277203164391128.07666981 587806.350064684391146.70299804
587845.5077211644391173.37299837587884.6684256484391228.83135906
#Sta/Elev= 30
-148.327  953.25-138.156  952.02-123.031  951.48 -98.589   951.3  -92.29  951.04
 -89.108  951.17 -86.483  950.77 -85.039  950.87 -72.277     948 -47.375     944
 -31.791  939.91 -20.144     938 -11.319  936.86  -9.121  936.27   -4.77     935
    3.23     935   7.349     936   9.285  936.03   92.52  937.59  105.84  937.14
 177.067     938 182.808     940  231.43  941.84 255.315     942 267.749  942.38
 299.967  942.46 311.614  943.07 319.816  943.23 323.163     944 344.094  944.69
#Mann= 7 ,-1 , 0
-148.327     .12       0 -31.791     .11       0 -20.144     .08       0
  -9.121     .04       0   9.285     .08       0  231.43     .06       0
 319.816     .12       0
#XS Ineff= 2 , 0
       0                     150       0
Permanent Ineff=
       F       F
Bank Sta=-9.121,9.285
XS Rating Curve= 0 ,0
Exp/Cntr=0.5,0.3

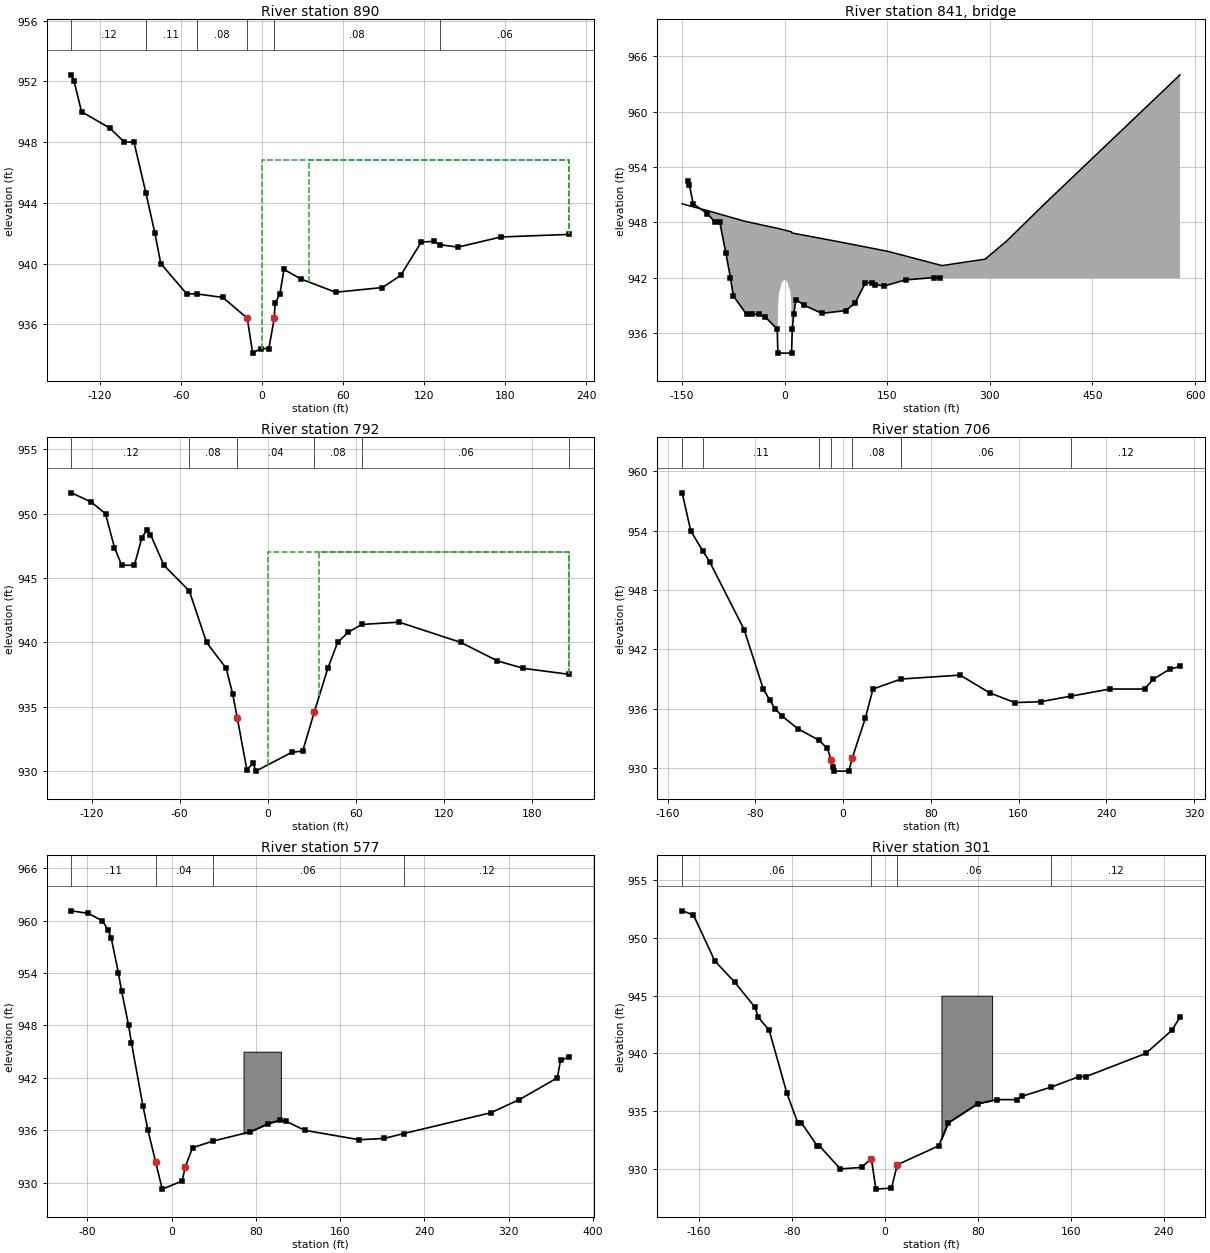
Type RM Length L Ch R = 1 ,890     ,98.846,98,98.387
BEGIN DESCRIPTION:
Channel from MUB HEC-RAS
END DESCRIPTION:
XS GIS Cut Line= 3
587766.0372161824391160.65369422587792.4207045084391170.85230234
  587864.64001744391214.05465487
#Sta/Elev= 30
-141.273  952.43-139.304     952 -133.76     950-112.959  948.93-102.034     948
 -94.948     948 -86.024  944.62 -79.429     942 -75.098     940 -55.807     938
 -48.491     938 -29.101  937.77     -11   936.4      -7   934.1      -1   934.4
       5   934.4       9   936.4   9.613  937.37  13.156     938   16.24  939.61
  28.839  938.98  54.528  938.11  89.173  938.42  102.69  939.22 117.979  941.42
 127.198  941.46 131.988  941.24 145.079  941.08 176.903  941.75 227.625  941.92
#Mann= 6 ,-1 , 0
-141.273     .12       0 -86.024     .11       0 -48.491     .08       0
     -11     .04       0       9     .08       0 131.988     .06       0
#XS Ineff= 2 , 0
       0     -35  946.85      35       0  946.85
Permanent Ineff=
       F       F
Bank Sta=-11,9
XS Rating Curve= 0 ,0
Exp/Cntr=0.5,0.3

Type RM Length L Ch R = 3 ,841     ,,,
BEGIN DESCRIPTION:
Woodland Drive (structure & internal XS from MUB HEC-RAS model)
END DESCRIPTION:
Bridge Culvert--1,0,-1,-1, 0
Deck Dist Width WeirC Skew NumUp NumDn MinLoCord MaxHiCord MaxSubmerge Is_Ogee
20.6,43,2.6,0, 21, 21, 943.3, , 0.95, 0, 0,0,,
    -150    -110   -58.3     -10   -9.99   -9.52   -8.23   -4.17       0    4.17
    8.23    9.52    9.99    10.4    75.9   150.5     230     293     325     380
     578
     950   949.2  948.11  947.33  947.33  947.32   947.3  947.23  947.15  947.07
     947  946.98  946.97  946.84  945.93  944.85   943.3     944     946     950
     964
                           933.8  937.92   939.3  940.41  941.45   941.8  941.45
  940.41   939.3  937.92
        
    -150    -110   -58.3     -10   -9.99   -9.52   -8.23   -4.17       0    4.17
    8.23    9.52    9.99    10.4    75.9   150.5     230     293     325     380
     578
     950   949.2  948.11  947.33  947.33  947.32   947.3  947.23  947.15  947.07
     947  946.98  946.97  946.84  945.93  944.85   943.3     944     946     950
     964
                           933.8  937.92   939.3  940.41  941.45   941.8  941.45
  940.41   939.3  937.92
        
BR Coef=-1 , 1 , 0 ,, 0 ,,,0.8,-1,1.2,0,
WSPro=,,,, 1 ,,,, 0 ,,,, 0 ,,,,-1 ,-1 ,-1 , 0 , 0 , 0 , 0 , 0
BR U #Sta/Elev= 30
-141.273  952.43-139.304     952 -133.76     950-112.959  948.93-102.034     948
 -94.948     948 -86.024  944.62 -79.429     942 -75.098     940 -55.807     938
 -48.491     938 -38.091     938 -29.101  937.77     -11   936.4     -10   933.8
      10   933.8      11   936.4  13.156     938   16.24  939.61  28.839  938.98
  54.528  938.11  89.173  938.42  102.69  939.22 117.979  941.42 127.198  941.46
 131.988  941.24 145.079  941.08 176.903  941.75 218.274     942 227.625  941.92
BR U #Mann= 6
-141.273     .12 -86.024     .11 -48.491     .08     -11     .04      11     .08
 131.988     .06
BR U Banks=,11
BR D #Sta/Elev= 189
-133.793  951.63 -120.21  950.91-118.602  950.78 -113.78   950.3-111.877  950.08
-110.564     950-109.121  949.33-106.037     948-105.413  947.73-104.495  947.38
-103.773  947.17 -99.541     946 -99.442     946 -97.507     946 -90.912     946
 -88.747  946.97 -88.189  947.18 -86.188     948  -85.86  948.12 -85.827  948.14
 -85.794  948.14 -85.794  948.15 -85.696  948.18 -84.908  948.42 -84.908  948.43
 -84.875  948.42 -84.285  948.59 -84.252  948.59 -84.252  948.58 -83.694  948.68
 -83.661  948.67 -83.629  948.67 -83.136  948.73 -83.104  948.72 -83.071  948.71
 -82.579  948.76 -82.316  948.76 -80.971  948.61 -80.512  948.51 -79.954  948.39
 -79.265  948.22 -78.412     948 -78.281  947.97 -78.215  947.96 -77.329  947.75
 -76.608  947.57  -76.05  947.42 -70.768     946 -67.913  945.69 -67.848  945.68
 -67.782  945.68 -67.717  945.67 -67.651  945.66 -67.585  945.65  -67.52  945.65
 -67.421  945.63 -53.478     944  -50.82  943.09 -50.098  942.86 -49.409  942.63
 -48.786  942.42 -47.539     942 -46.621  941.68 -41.732     940 -34.186     939
 -28.543  938.02 -28.412     938 -27.723  937.69 -27.133  937.42 -26.706  937.23
 -26.411  937.08 -26.148  936.97  -23.95     936 -20.833  934.15 -20.571     934
 -20.144  933.74 -17.323   933.2 -15.846   933.2 -15.289   933.2 -14.304   933.2
  -10.63   933.2     -10   933.2      10   933.2  13.451   933.2  16.142   933.2
  23.786   933.2  24.639   933.2  31.562  934.56  40.879     938  45.243  939.33
  47.441  939.97  47.539     940  49.245  940.22  50.656   940.4  51.411  940.42
  52.756  940.57  53.871   940.7  54.823   940.8  56.168  940.82  57.546  940.83
  64.009   941.4  65.814   941.4   71.85  941.61  72.244  941.62  75.689  941.62
  76.115  941.62  78.707  941.62  82.185  941.61  82.382  941.61  82.579  941.61
  85.991   941.6   89.37  941.58  99.377  941.27 100.098  941.22 100.886  941.18
 101.804  941.12 102.854  941.06 109.646  940.98 110.696  940.88 111.024  940.85
 111.385  940.82 111.778  940.79 112.172  940.76 112.894   940.7 113.419  940.69
 113.517  940.68 114.042  940.67 114.108  940.67 114.633  940.65 115.125  940.64
 115.223  940.63 115.322  940.63 115.781  940.61  116.24  940.59 116.404  940.59
 116.831  940.57 117.224  940.56 118.668   940.5 120.735  940.43 131.529     940
 145.144  939.08 145.341  939.05 145.571  939.03 145.833  939.02 146.325  938.99
 146.818  938.97 147.343  938.94   147.9  938.92 148.491   938.9  148.72  938.89
 149.213  938.88 150.197  938.82 150.689   938.8 151.181  938.79 152.034  938.74
 152.592  938.72 153.675  938.69 154.429  938.65 155.118  938.62 155.774   938.6
 156.365  938.57 156.923  938.56 171.588  938.07 171.686  938.07  173.72     938
 174.016  937.99 176.148  937.95 178.182  937.91 178.314  937.91 180.348  937.87
 182.283  937.84 182.546  937.83 184.449   937.8 186.286  937.77 187.041  937.76
 188.944  937.72 192.848  937.65 193.996  937.63 195.144  937.61  196.26  937.59
  197.31  937.56 198.327  937.54 199.311  937.51  200.23  937.48 201.115  937.45
 201.837  937.49 203.215  937.55 203.576  937.56 205.381  937.52
BR D #Mann= 6
-133.793     .12 -53.478     .08 -20.833     .04  31.562     .08  64.009     .06
 205.381     .12
BC Design=,, 0 ,, 0 ,,,,,,
BC Use User HTab Curves=0
BC User HTab FreeFlow(D)= 0

Type RM Length L Ch R = 1 ,792     ,91.67,86,79.12
XS GIS Cut Line= 3
587755.2229120484391188.63433456587779.2167683454391197.90939868
587846.1447531724391237.29870316
#Sta/Elev= 30
-133.793  951.63 -120.21  950.91-110.564     950-104.495  947.38 -99.541     946
 -90.912     946 -85.827  948.14 -82.316  948.76 -79.954  948.39 -70.768     946
 -53.478     944 -41.732     940 -28.412     938  -23.95     936 -20.833  934.15
 -14.304  930.12  -9.974  930.62  -8.136     930  16.142  931.45  23.786  931.57
  31.562  934.56  40.879     938  47.539     940  54.823   940.8  64.009   941.4
   89.37  941.58 131.529     940 156.365  938.57 174.016  937.99 205.381  937.52
#Mann= 6 ,-1 , 0
-133.793     .12       0 -53.478     .08       0 -20.833     .04       0
  31.562     .08       0  64.009     .06       0 205.381     .12       0
#XS Ineff= 2 , 0
       0     -35     947      35       0     947
Permanent Ineff=
       F       F
Bank Sta=-20.833,31.562
XS Rating Curve= 0 ,0
Exp/Cntr=0.5,0.3

Type RM Length L Ch R = 1 ,706     ,144.21,129,113.91
XS GIS Cut Line= 6
587741.1563918744391216.97768691587778.6925123384391228.50217505
587783.8649684024391230.24258307587801.6927206224391235.18034314
587867.624009437 4391240.1699192587876.2010815434391243.01370323
#Sta/Elev= 30
-146.719  957.84-138.911     954-128.084     952-121.555  950.85 -90.157     944
 -72.736     938 -67.028  936.92 -61.942     936 -55.381  935.25  -41.47     934
 -22.211  932.84 -14.272     932 -10.696  930.78  -8.793  930.12  -8.465   929.7
   5.217   929.7   8.432  931.05  20.276  935.04  27.264     938  52.789  939.01
 106.759  939.41 133.596  937.62 156.594  936.63 180.151  936.72 208.169  937.29
 243.077     938 274.934     938 282.644  938.98 297.703     940 307.251  940.29
#Mann= 7 ,-1 , 0
-146.719     .12       0-128.084     .11       0 -22.211     .08       0
 -10.696     .04       0   8.432     .08       0  52.789     .06       0
 208.169     .12       0
#XS Ineff= 2 , 0
       0                  106.75       0
Permanent Ineff=
       F       F
Bank Sta=-10.696,8.432
XS Rating Curve= 0 ,0
Exp/Cntr=0.3,0.1

Type RM Length L Ch R = 1 ,577     ,304.9,276,248.19
BEGIN DESCRIPTION:
Channel from MUB HEC-RAS
END DESCRIPTION:
XS GIS Cut Line= 6
587746.6610799424391274.12768762587768.4786642124391269.76904756
587773.6480722764391268.32124755 587778.814432344391266.87649553
587804.6767126594391258.09520742587887.2074096794391243.64768724
#Sta/Elev= 30
 -95.079  961.13 -79.199  960.84 -65.715     960 -60.302  958.94 -57.349  958.05
 -50.459     954 -47.539     952 -40.781     948 -38.091     946 -27.165  938.78
 -22.408     936     -15 932.315    -8.9  929.26      10  930.19  13.123  931.85
  19.882     934  38.944  934.75  74.213   935.8  91.995  936.77 102.723  937.14
 108.202  937.05 126.608  935.99 178.117  934.92 201.608  935.06 220.571  935.63
 302.953     938 330.151  939.51  366.24     942 369.259     944 377.625  944.41
#Mann= 4 ,-1 , 0
 -95.079     .11       0     -15     .04       0  38.944     .06       0
 220.571     .12       0
#XS Ineff= 2 , 0
       0                  103.74       0
Permanent Ineff=
       F       F
#Block Obstruct= 1 ,-1
   68.34  103.74     945
Bank Sta=-15,13.123
XS Rating Curve= 0 ,0
Exp/Cntr=0.3,0.1

Type RM Length L Ch R = 1 ,301     ,82.56,87,92.74
BEGIN DESCRIPTION:
Channel from MUB HEC-RAS
END DESCRIPTION:
XS GIS Cut Line= 4
 587803.887280654391340.27538443587836.6288970544391312.16368009
587851.8445132424391266.85211153 587888.054753694391250.63370333
#Sta/Elev= 30
-174.573  952.35-164.895     952-146.391     948-129.495  946.19-111.877     944
-109.088  943.14 -99.639     942 -84.383  936.55 -75.131     934 -71.949     934
 -58.333     932 -56.496     932 -38.386     930  -20.15  930.13   -11.7   930.9
    -7.8  928.25     5.6  928.34    10.6  930.36  46.293     932  54.528     934
  79.757  935.65  96.358     936 113.747     936 117.651  936.28 142.881  937.08
 167.224     938 173.163     938 224.508     940 246.949     942 254.003  943.15
#Mann= 4 ,-1 , 0
-174.573     .06       0   -11.7     .04       0    10.6     .06       0
 142.881     .12       0
#Block Obstruct= 1 ,-1
  48.622  92.257     945
Bank Sta=-11.7,10.6
XS Rating Curve= 0 ,0
Exp/Cntr=0.3,0.1

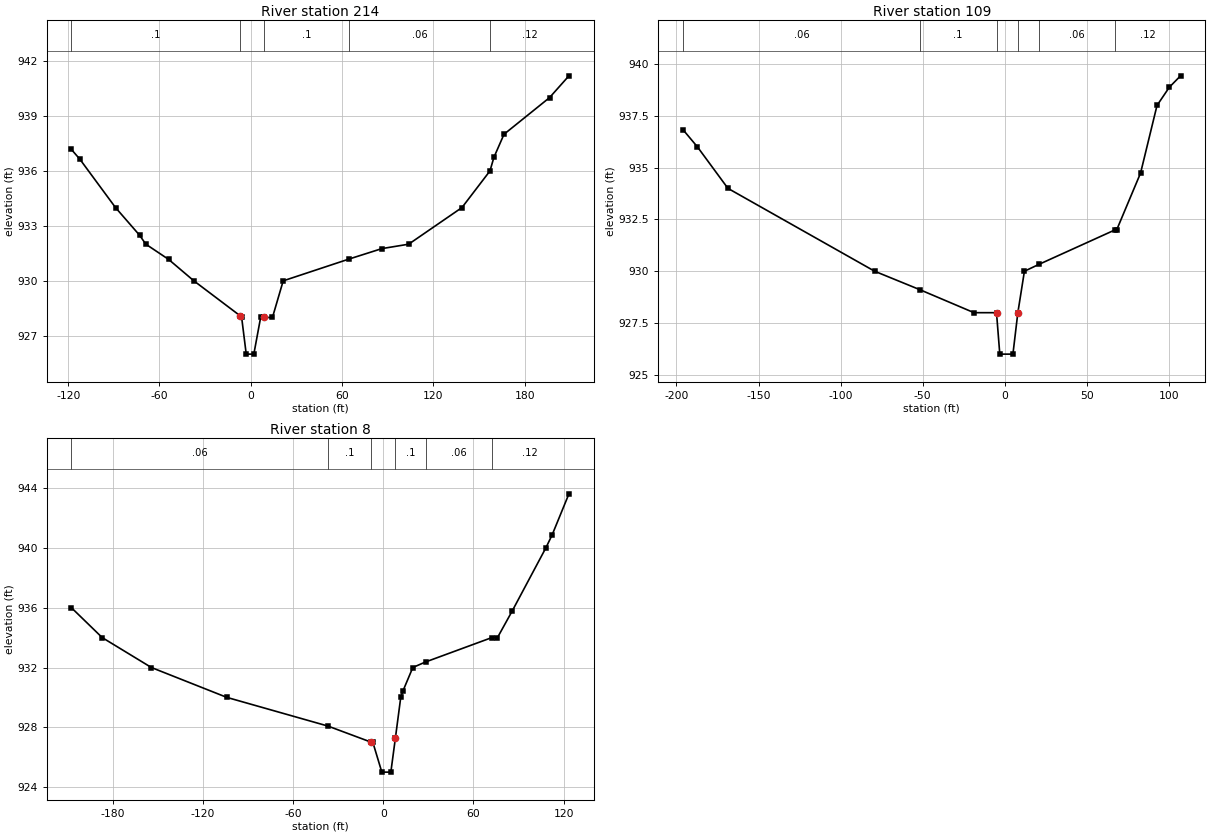
Type RM Length L Ch R = 1 ,214     ,102.16,105,104.88
BEGIN DESCRIPTION:
Channel from MUB HEC-RAS
END DESCRIPTION:
XS GIS Cut Line= 6
587840.7406491054391352.47348059587857.1084093074391322.72195222
587857.818593316 4391320.8840082587858.5287773254391319.04606417
587867.9958654424391304.08038399587889.5360817084391265.66034351
#Sta/Elev= 24
-117.881  937.17-112.336  936.64 -88.911     934 -73.097  932.49 -68.963     932
 -54.003  931.17 -37.402     930  -6.955  928.09      -6     928      -3     926
       2     926   6.463     928       9     928  14.239     928  21.293     930
  64.567  931.19  86.155  931.76  103.74     932  138.78     934 157.185     936
 159.777  936.74 166.404     938 196.325     940 209.088  941.19
#Mann= 5 ,-1 , 0
-117.881      .1       0  -6.955     .04       0       9      .1       0
  64.567     .06       0 157.185     .12       0
Bank Sta=-6.955,9
XS Rating Curve= 0 ,0
Exp/Cntr=0.3,0.1

Type RM Length L Ch R = 1 ,109     ,94.12,101,109.72
BEGIN DESCRIPTION:
Channel from MUB HEC-RAS
END DESCRIPTION:
XS GIS Cut Line= 6
587846.3550651744391368.95401679587866.8650574284391363.64744872
587886.9269936764391333.06076835587889.060593702 4391329.7475923
587899.1586178274391311.22184808587903.9287378864391302.91299997
#Sta/Elev= 18
-195.997  936.83-187.205     936-168.635     934 -79.232     930 -51.706  929.11
 -18.701     928      -5     928      -3     926       5     926       8     928
      12     930  20.801  930.33  67.323     932  68.241     932  82.776  934.74
  92.782     938 100.295  938.88 107.119  939.43
#Mann= 6 ,-1 , 0
-195.997     .06       0 -51.706      .1       0      -5     .04       0
       8      .1       0  20.801     .06       0  67.323     .12       0
Bank Sta=-5,8
XS Rating Curve= 0 ,0
Exp/Cntr=0.3,0.1

Type RM Length L Ch R = 1 ,8       ,5.72,8,16.45
BEGIN DESCRIPTION:
Channel from MUB HEC-RAS
END DESCRIPTION:
XS GIS Cut Line= 6
587863.2897533844391393.29534509587886.5947616724391374.05027285
587908.6165619444391352.72646459587913.4141140034391349.01704854
587922.2045461124391340.45216844587937.3713942994391324.92870425
#Sta/Elev= 20
-207.579     936-187.073     934-154.364     932-104.134     930 -36.811  928.08
      -8     927      -7     927      -1     925       5     925       8 927.262
  11.581     930  13.091  930.44  19.619     932  28.084  932.37  72.178     934
  75.951     934  85.761  935.78 108.136     940 112.369  940.88 123.524  943.62
#Mann= 6 ,-1 , 0
-207.579     .06       0 -36.811      .1       0      -8     .04       0
       8      .1       0  28.084     .06       0  72.178     .12       0
Bank Sta=-8,8
XS Rating Curve= 0 ,0
Exp/Cntr=0.3,0.1
Stream Node=Burroughs Run   ,Reach 1         , 0 , 0 ,Upstream end
Stream Node=Burroughs Run   ,Reach 1         , 0 , 1 ,Downstream end

Chan Stop Cuts=-1
Use User Specified Reach Order=0
Composite Channel Slope=5

--- BurroughsRun.g02 (geometry) ---

Geom Title=Burroughs Run - MUB Geometry
Program Version=4.10

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
River Reach=RIVER-1         ,Reach-1
Reach XY= 30
 1837997.1170814  422082.3195012 1837759.9735549  422092.4937815
 1837523.8767903  422403.3031499 1837270.8279085  422483.6870086
 1837186.4371827  422556.8585126 1836706.2310004  422516.9743104
 1836571.0185356  422551.4966419 1836534.3385584  422581.7036819
 1836485.5377626  422782.6602596 1836247.0432803  422863.1678665
  1836053.049412  423215.5869785 1835872.3637863  423424.8997064
 1835744.3434738  423502.5749522 1835559.5886813  423426.6562534
 1835348.5745111  423446.8948422 1834947.1518909  423417.7237796
 1834818.2571631  423731.8560112 1834822.5106033  424277.2210442
 1834779.1034162  424360.9288039 1834889.7026355   424594.934545
  1834857.894299  424818.3942771 1834700.7404636  424895.1620995
 1834590.4900505   424897.735691 1834553.7512851  424863.1522708
 1834434.8288426  424914.4857291 1834310.9955035  425312.6294725
 1834400.5745818  425358.2077333 1834422.4721331  425417.0574026
 1834542.2746922  425425.2392509 1834759.3496108  425565.6729709

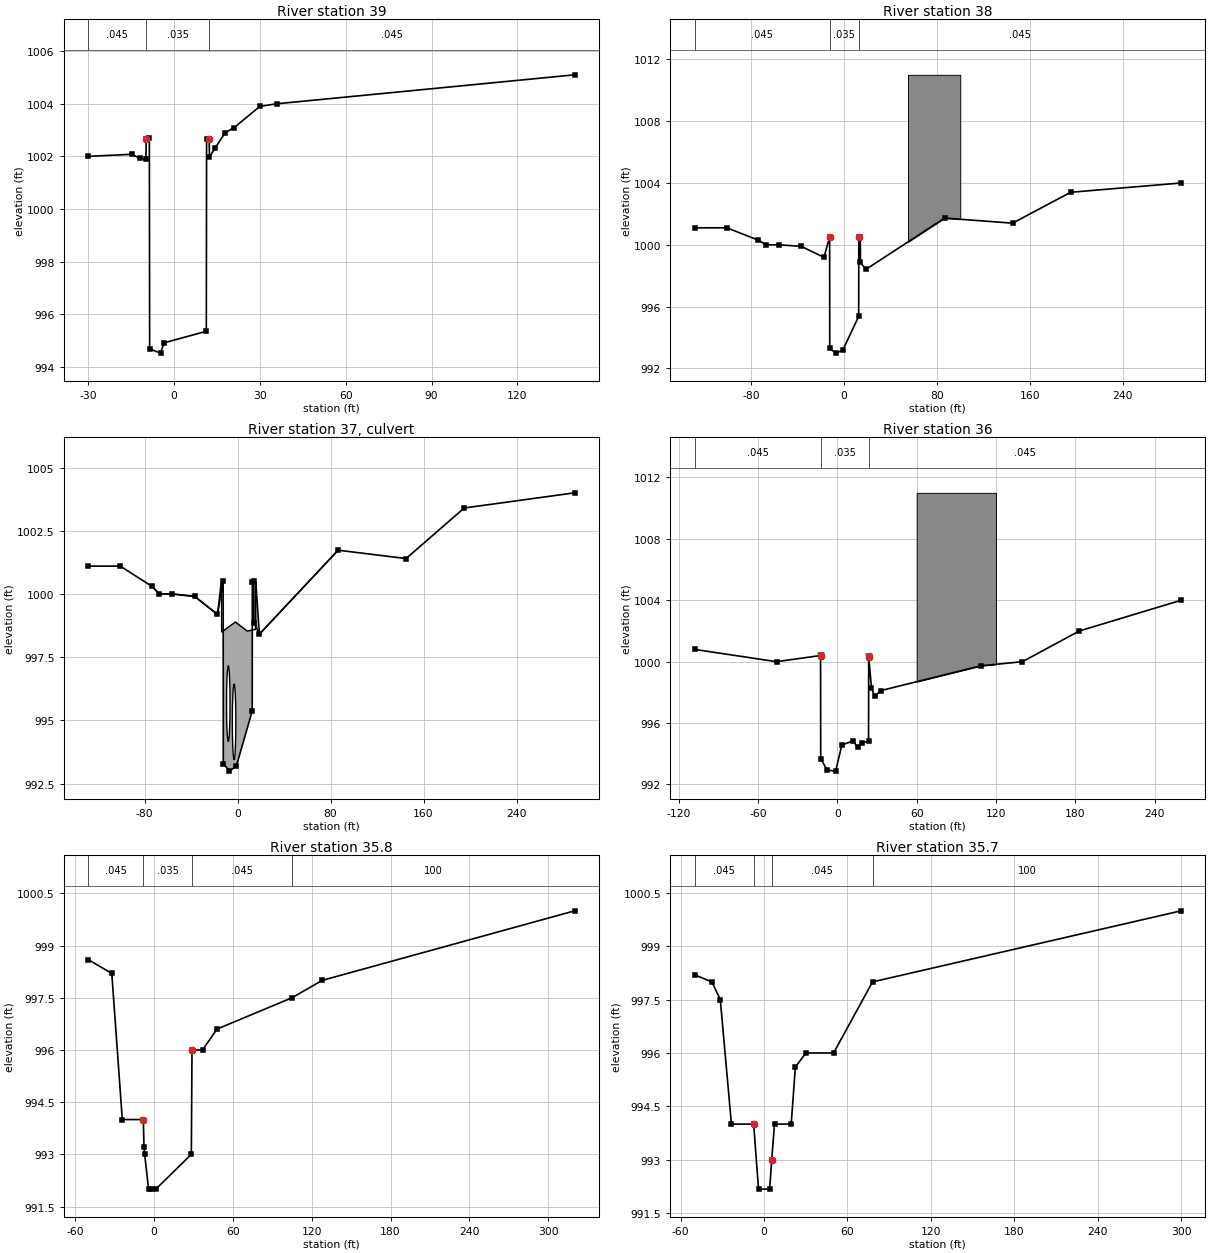
Type RM Length L Ch R = 1 ,39      ,130,130,130
#Sta/Elev= 19
     -30    1002   -14.6 1002.08     -12 1001.92    -9.8 1001.89    -9.7 1002.67
    -8.6  1002.7    -8.5  994.68    -4.7  994.52    -3.5  994.91    11.3  995.35
    11.4 1002.67    12.3 1002.67    12.4 1001.98    14.4 1002.32    17.9  1002.9
      21 1003.09      30  1003.9      36    1004     140  1005.1
#Mann= 3 , 0 , 0
     -30    .045       0    -9.7    .035       0    12.3    .045       0
Bank Sta=-9.7,12.3
XS Rating Curve= 0 ,0
Exp/Cntr=0.3,0.1

Type RM Length L Ch R = 1 ,38      ,68.4,68.4,68.4
#Sta/Elev= 20
  -128.6  1001.1  -100.9  1001.1   -73.7  1000.3   -67.2    1000   -56.3    1000
   -36.9   999.9   -17.3  999.19   -12.4  1000.5   -12.3  993.29    -7.1  992.99
    -1.1  993.18    12.6  995.37    12.7 1000.48      14  1000.5    14.1  998.86
    18.8  998.41    86.5 1001.73     145  1001.4     195  1003.4     290    1004
#Mann= 3 , 0 , 0
  -128.6    .045       0   -12.4    .035       0    12.7    .045       0
#Block Obstruct= 1 ,-1
      55     100    1011
Bank Sta=-12.4,12.7
XS Rating Curve= 0 ,0
Exp/Cntr=0.5,0.3

Type RM Length L Ch R = 2 ,37      ,,,
BEGIN DESCRIPTION:
Berm DS From Van Voorhis
END DESCRIPTION:
Bridge Culvert--1,0,-1,-1, 0
Deck Dist Width WeirC Skew NumUp NumDn MinLoCord MaxHiCord MaxSubmerge Is_Ogee
12,40,2.6,0, 16, 17, , , 0.95, 0, 0,0,,
   -73.7   -67.2   -56.3   -36.9   -17.3   -14.2   -13.7   -13.7   -11.9    -1.9
     8.3    15.5    15.5    15.8    18.8    86.5
  1000.3    1000    1000   999.9  999.19 1000.41 1000.43   998.5  998.55  998.89
  998.53   998.6 1000.45 1000.45  998.41 1001.73
                                                                                
                                                
   -73.7   -67.2   -56.3   -36.9   -17.3   -14.2   -13.7   -13.7   -11.9    -1.9
     8.3    23.7    23.7      24    28.1   108.4     140
  1000.3    1000    1000   999.9  999.19 1000.41 1000.43   998.5  998.55  998.89
  998.53   998.6 1000.45 1000.45  997.75  999.74    1000
                                                                                
                                                        
BR Coef=-1 , 0 , 0 ,, 0 ,,,0.8,-1,,0,
WSPro=,,,, 1 ,,,, 0 ,,,, 0 ,,,,-1 ,-1 ,-1 , 0 , 0 , 0 , 0 , 0
Culvert=1,3,,40,0.024,0.5,1,2,3,994.16,-8,993.82,-8,Culvert #1  , 0 ,5
Culvert Bottom n=0.024
Culvert=1,3,,40,0.024,0.5,1,2,3,993.44,-3,994.12,-3,Culvert #2  , 0 ,14
Culvert Bottom n=0.024
BC Design=,, 0 ,, 0 ,,,,,,
BC Use User HTab Curves=0
BC User HTab FreeFlow(D)= 0

Type RM Length L Ch R = 1 ,36      ,100,100,60
BEGIN DESCRIPTION:
70+00
END DESCRIPTION:
#Sta/Elev= 19
    -108  1000.8     -46    1000   -12.7  1000.4   -12.6  993.69    -7.8  992.94
    -1.3  992.87     3.4  994.57    11.9  994.84    15.3  994.42    18.6  994.72
    23.6  994.81    23.7  1000.3    25.8   998.3    28.1  997.75    33.1  998.12
   108.4  999.73     140    1000     183    1002     260    1004
#Mann= 3 , 0 , 0
    -108    .045       0   -12.7    .035       0    23.7    .045       0
Levee=-1,-12.7,1000.4,-1,23.7,1000.3,,
#Block Obstruct= 1 ,-1
      60     120    1011
Bank Sta=-12.7,23.7
XS Rating Curve= 0 ,0
Exp/Cntr=0.5,0.3

Type RM Length L Ch R = 1 ,35.8    ,75,75,72
BEGIN DESCRIPTION:
69+00
END DESCRIPTION:
#Sta/Elev= 16
     -50   998.6     -32   998.2     -24     994      -8     994    -7.5   993.2
      -7     993      -4     992    -2.5     992     1.5     992    28.5     993
      29     996      37     996      48   996.6     105   997.5     128     998
     320    1000
#Mann= 4 ,-1 , 0
     -50    .045       0      -8    .035       0      29    .045       0
     105     100       0
Bank Sta=-8,29
XS Rating Curve= 0 ,0
Exp/Cntr=0.3,0.1

Type RM Length L Ch R = 1 ,35.7    ,75,75,60
BEGIN DESCRIPTION:
68+25
END DESCRIPTION:
#Sta/Elev= 15
     -50   998.2   -37.5     998   -31.5   997.5   -23.5     994    -7.5     994
      -4  992.17       4  992.17     5.5     993     7.5     994    19.5     994
    22.5   995.6      30     996      50     996      78     998     300    1000
#Mann= 4 ,-1 , 0
     -50    .045       0    -7.5    .035       0     5.5    .045       0
      78     100       0
Bank Sta=-7.5,5.5
XS Rating Curve= 0 ,0
Exp/Cntr=0.3,0.1