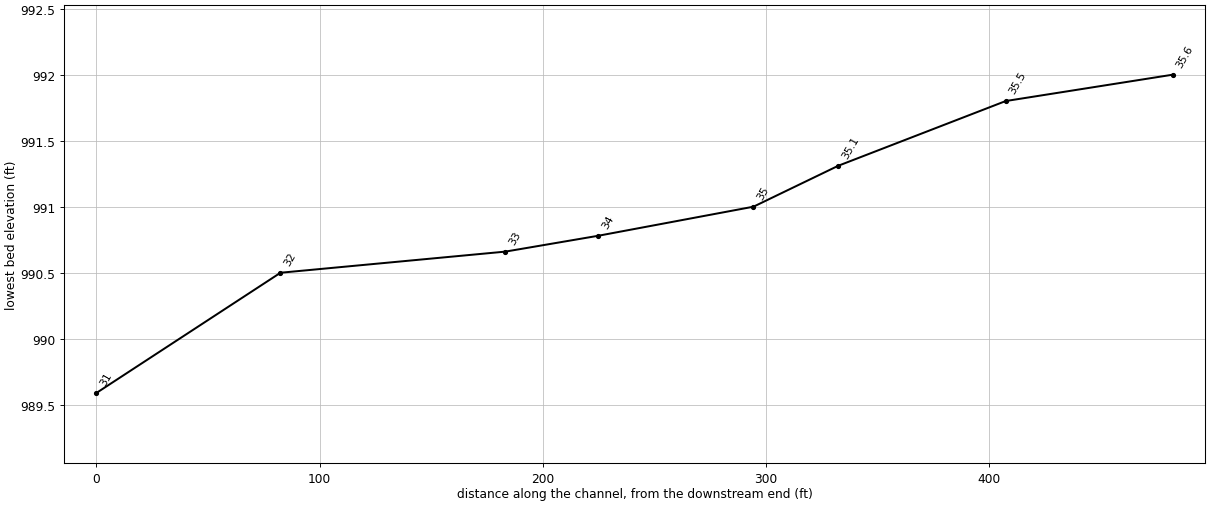
HEC-RAS study BurroughsRun.prj: Burroughs Run

--- BurroughsRun.g02 (geometry) --- (continued)

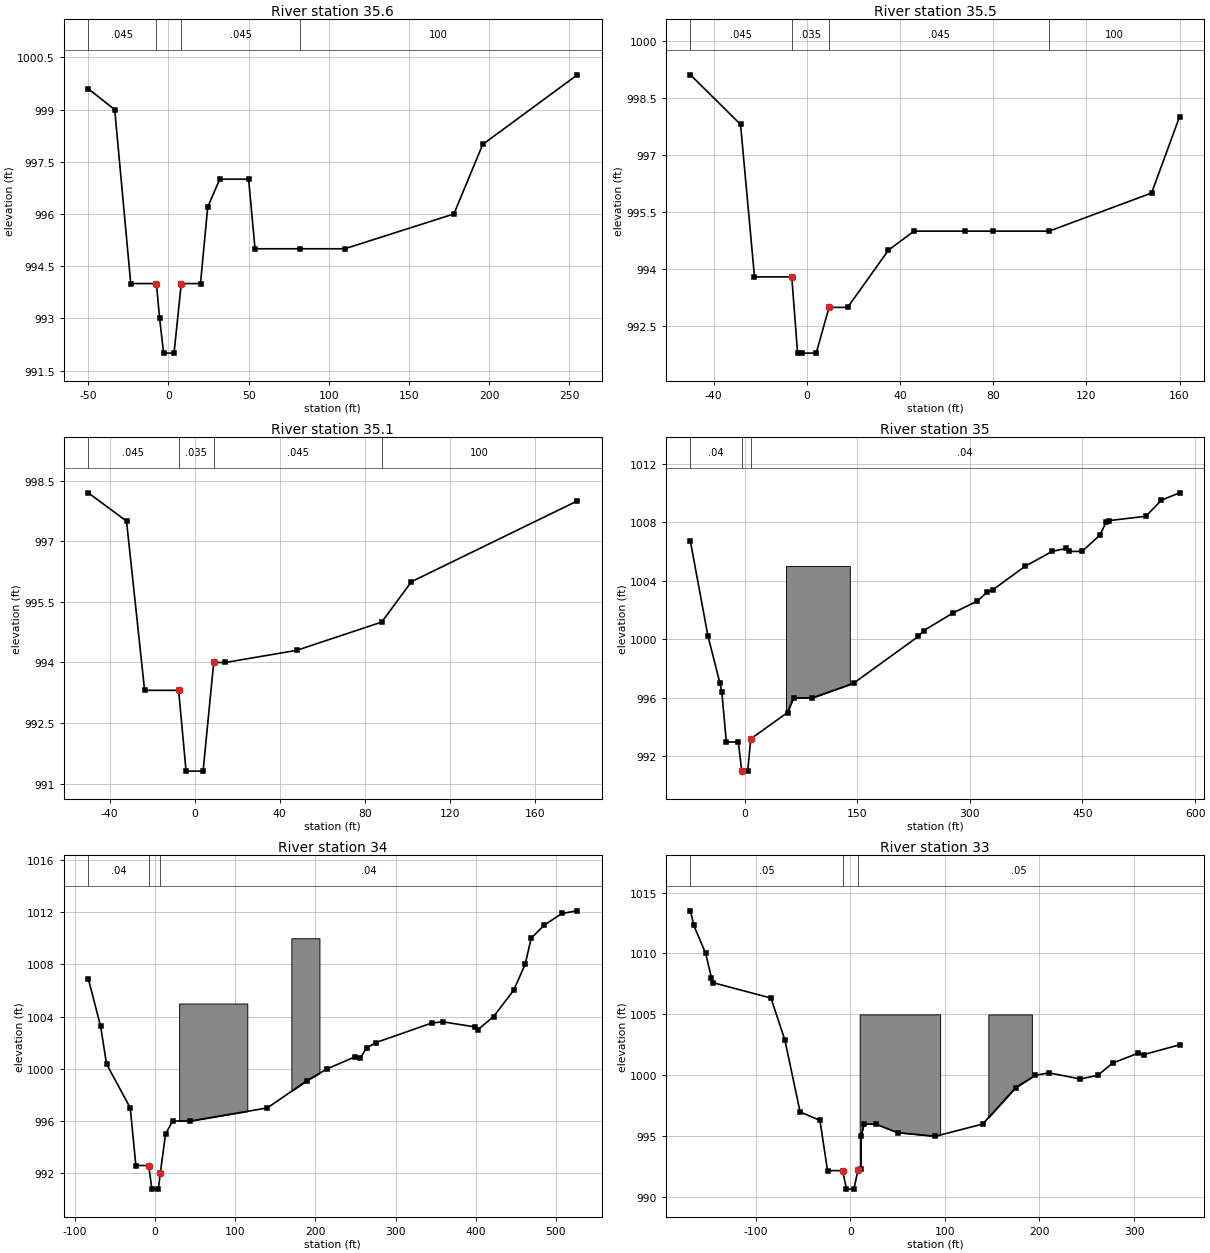
Type RM Length L Ch R = 1 ,35.6    ,75,75,51
BEGIN DESCRIPTION:
67+50
END DESCRIPTION:
#Sta/Elev= 18
     -50   999.6   -33.5     999   -23.5     994    -7.5     994    -5.5     993
      -3     992     3.5     992       8     994      20     994    24.5   996.2
      32     997      50     997      54     995      82     995     110     995
     178     996     196     998     255    1000
#Mann= 4 ,-1 , 0
     -50    .045       0    -7.5    .035       0       8    .045       0
      82     100       0
Bank Sta=-7.5,8
XS Rating Curve= 0 ,0
Exp/Cntr=0.3,0.1

Type RM Length L Ch R = 1 ,35.5    ,75,75,78
BEGIN DESCRIPTION:
Sta. 66+75
END DESCRIPTION:
#Sta/Elev= 16
     -50   999.1   -28.5   997.8   -22.5   993.8    -6.5   993.8      -4   991.8
      -2   991.8       4   991.8     9.5     993    17.5     993      35   994.5
      46     995      68     995      80     995     104     995     148     996
     160     998
#Mann= 4 ,-1 , 0
     -50    .045       0    -6.5    .035       0     9.5    .045       0
     104     100       0
Bank Sta=-6.5,9.5
XS Rating Curve= 0 ,0
Exp/Cntr=0.3,0.1

Type RM Length L Ch R = 1 ,35.1    ,38,38,32
BEGIN DESCRIPTION:
66+00
END DESCRIPTION:
#Sta/Elev= 12
     -50   998.2     -32   997.5   -23.5  993.31    -7.5  993.31      -4  991.31
       4  991.31       9     994    14.5     994      48   994.3      88     995
     102     996     180     998
#Mann= 4 ,-1 , 0
     -50    .045       0    -7.5    .035       0       9    .045       0
      88     100       0
Bank Sta=-7.5,9
XS Rating Curve= 0 ,0
Exp/Cntr=0.3,0.1

Type RM Length L Ch R = 1 ,35      ,69.51,69.51,69.51
BEGIN DESCRIPTION:
65+62
END DESCRIPTION:
#Sta/Elev= 30
   -72.3 1006.68   -49.1 1000.25     -33     997   -30.5   996.4   -24.5  992.99
    -8.5  992.99      -4     991       4     991       8   993.2      57     995
      65     996      90     996     145     997   231.4  1000.2   238.6  1000.6
   277.6  1001.8   309.5  1002.6   322.8  1003.2   331.1  1003.4     374    1005
   409.6    1006   427.9  1006.2   431.8    1006   449.4    1006   472.9  1007.1
   481.7    1008   484.9  1008.1   534.4  1008.4   555.2  1009.5   579.3    1010
#Mann= 3 , 0 , 0
   -72.3     .04       0      -4    .035       0       8     .04       0
#Block Obstruct= 1 ,-1
      55     140    1005
Bank Sta=-4,8
XS Rating Curve= 0 ,0
Exp/Cntr=0.3,0.1

Type RM Length L Ch R = 1 ,34      ,38,41.6,50
BEGIN DESCRIPTION:
64+92
END DESCRIPTION:
#Sta/Elev= 30
   -83.4 1006.91     -68 1003.26   -60.6 1000.37     -31     997     -24  992.59
      -8  992.59      -4  990.78       4  990.78     6.5     992      13     995
      22     996      44     996     140     997   189.6   999.1   214.8    1000
   248.8  1000.9   255.6  1000.8     264  1001.6   275.2    1002   344.8  1003.5
   358.8  1003.6   399.4  1003.2   402.7    1003   422.2    1004   447.1    1006
   461.6    1008   469.1    1010   485.3    1011   507.4  1011.9   526.7  1012.1
#Mann= 3 , 0 , 0
   -83.4     .04       0      -8    .035       0     6.5     .04       0
#Block Obstruct= 2 ,-1
      30     115    1005     170     205    1010
Bank Sta=-8,6.5
XS Rating Curve= 0 ,0
Exp/Cntr=0.3,0.1

Type RM Length L Ch R = 1 ,33      ,98,100.75,110
BEGIN DESCRIPTION:
64+50
END DESCRIPTION:
#Sta/Elev= 30
  -168.9  1013.5  -165.3  1012.3  -152.8    1010  -146.7    1008  -144.9  1007.6
   -83.8 1006.34     -69 1002.87     -53     997     -32   996.3     -24  992.18
      -8  992.18      -4  990.66       4  990.66       8   992.2    11.3   992.3
    11.4     995    14.5     996      27     996      50   995.3      90     995
     140     996     175     999   195.5    1000   210.2  1000.2   243.1   999.7
   261.7    1000   277.3    1001   303.8  1001.8   310.1  1001.7   348.1  1002.5
#Mann= 3 , 0 , 0
  -168.9     .05       0      -8    .035       0       8     .05       0
#Block Obstruct= 2 ,-1
      10      95    1005     146     192    1005
Bank Sta=-8,8
XS Rating Curve= 0 ,0
Exp/Cntr=0.3,0.1

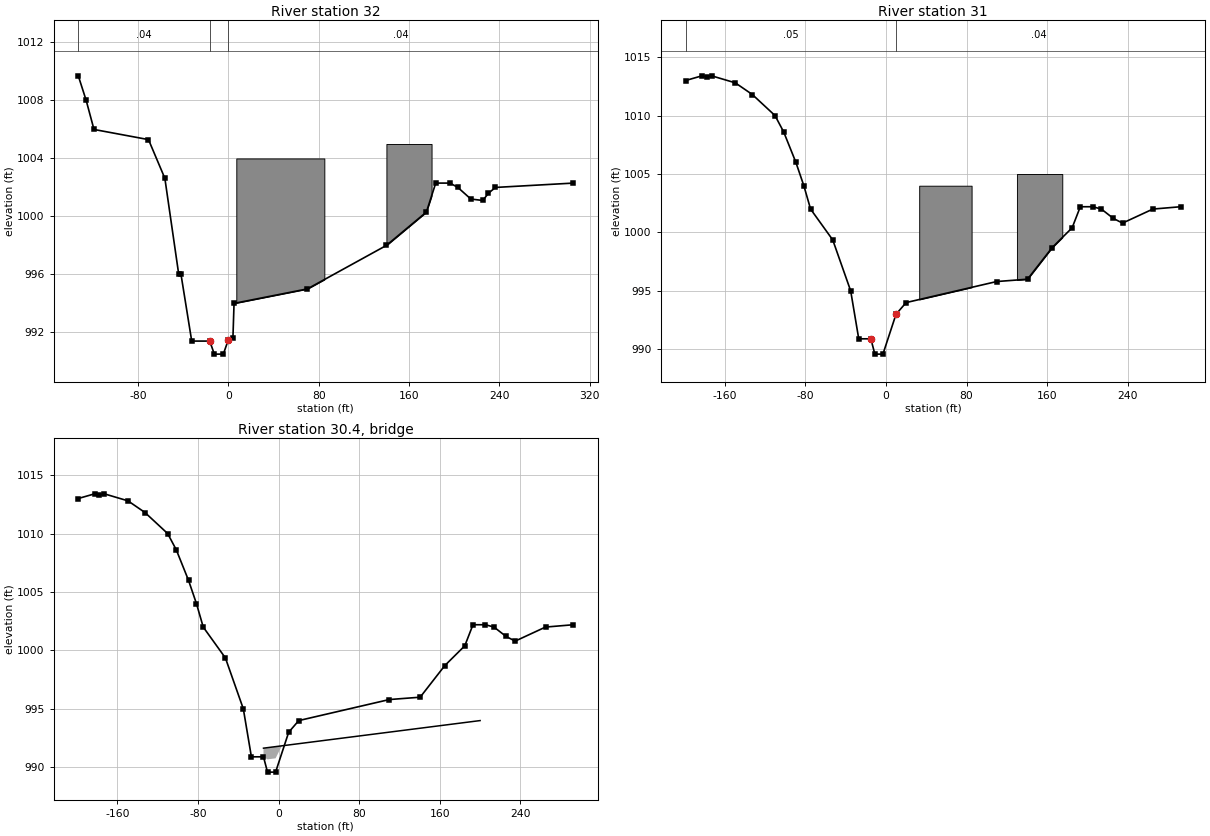
Type RM Length L Ch R = 1 ,32      ,84.96,82.44,60.04
BEGIN DESCRIPTION:
63+50
END DESCRIPTION:
#Sta/Elev= 25
    -133  1009.7    -126    1008  -119.1    1006   -70.8  1005.3   -56.3 1002.63
     -44     996     -42     996   -32.5   991.4   -16.5   991.4   -12.5   990.5
    -4.5   990.5       0   991.5       4   991.6       5     994      70     995
     140     998   175.4  1000.3   183.7  1002.3   196.4  1002.3   203.3    1002
   214.8  1001.2   225.4  1001.1   230.4  1001.6   236.6    1002   305.6  1002.3
#Mann= 3 , 0 , 0
    -133     .04       0   -16.5    .035       0       0     .04       0
#Block Obstruct= 2 ,-1
       7      85    1004     140     180    1005
Bank Sta=-16.5,0
XS Rating Curve= 0 ,0
Exp/Cntr=0.3,0.1

Type RM Length L Ch R = 1 ,31      ,354.8,364.08,375.2
BEGIN DESCRIPTION:
62+67
END DESCRIPTION:
#Sta/Elev= 30
  -198.8    1013  -182.6  1013.4  -177.8  1013.3    -173  1013.4  -149.5  1012.8
  -132.6  1011.8  -110.1    1010  -101.5  1008.6   -89.4    1006   -81.5    1004
   -74.8    1002   -52.8  999.36     -35     995     -27   990.9     -15   990.9
     -11  989.59      -3  989.59      10     993      20     994   109.9   995.8
   140.5     996   164.9   998.7   184.8  1000.4   192.9  1002.2   205.3  1002.2
   213.8    1002   225.7  1001.2   234.8  1000.8   264.9    1002   292.5  1002.2
#Mann= 2 ,-1 , 0
  -198.8     .05       0      10     .04       0
#Block Obstruct= 2 ,-1
      33      85    1004     130     175    1005
Bank Sta=-15,10
XS Rating Curve= 0 ,0
Exp/Cntr=0.3,0.1

Type RM Length L Ch R = 3 ,30.4    ,,,
BEGIN DESCRIPTION:
pedestrian bridge
END DESCRIPTION:
Bridge Culvert--1,0,-1,-1, 0
Deck Dist Width WeirC Skew NumUp NumDn MinLoCord MaxHiCord MaxSubmerge Is_Ogee
10,4,2.6,0, 2, 2, 994, , 0.98, 0, 0,0,,
     -15     200
  991.64     994
  990.64     993
     -15     200
  991.64     994
  990.64     993
BR Coef=-1 , 0 , 0 ,, 0 ,,,0.8,-1,,0,
WSPro=,,,, 1 ,,,, 0 ,,,, 0 ,,,,-1 ,-1 ,-1 , 0 , 0 , 0 , 0 , 0
BC Design=,, 0 ,, 0 ,,,,,,
BC Use User HTab Curves=0
BC User HTab FreeFlow(D)= 0