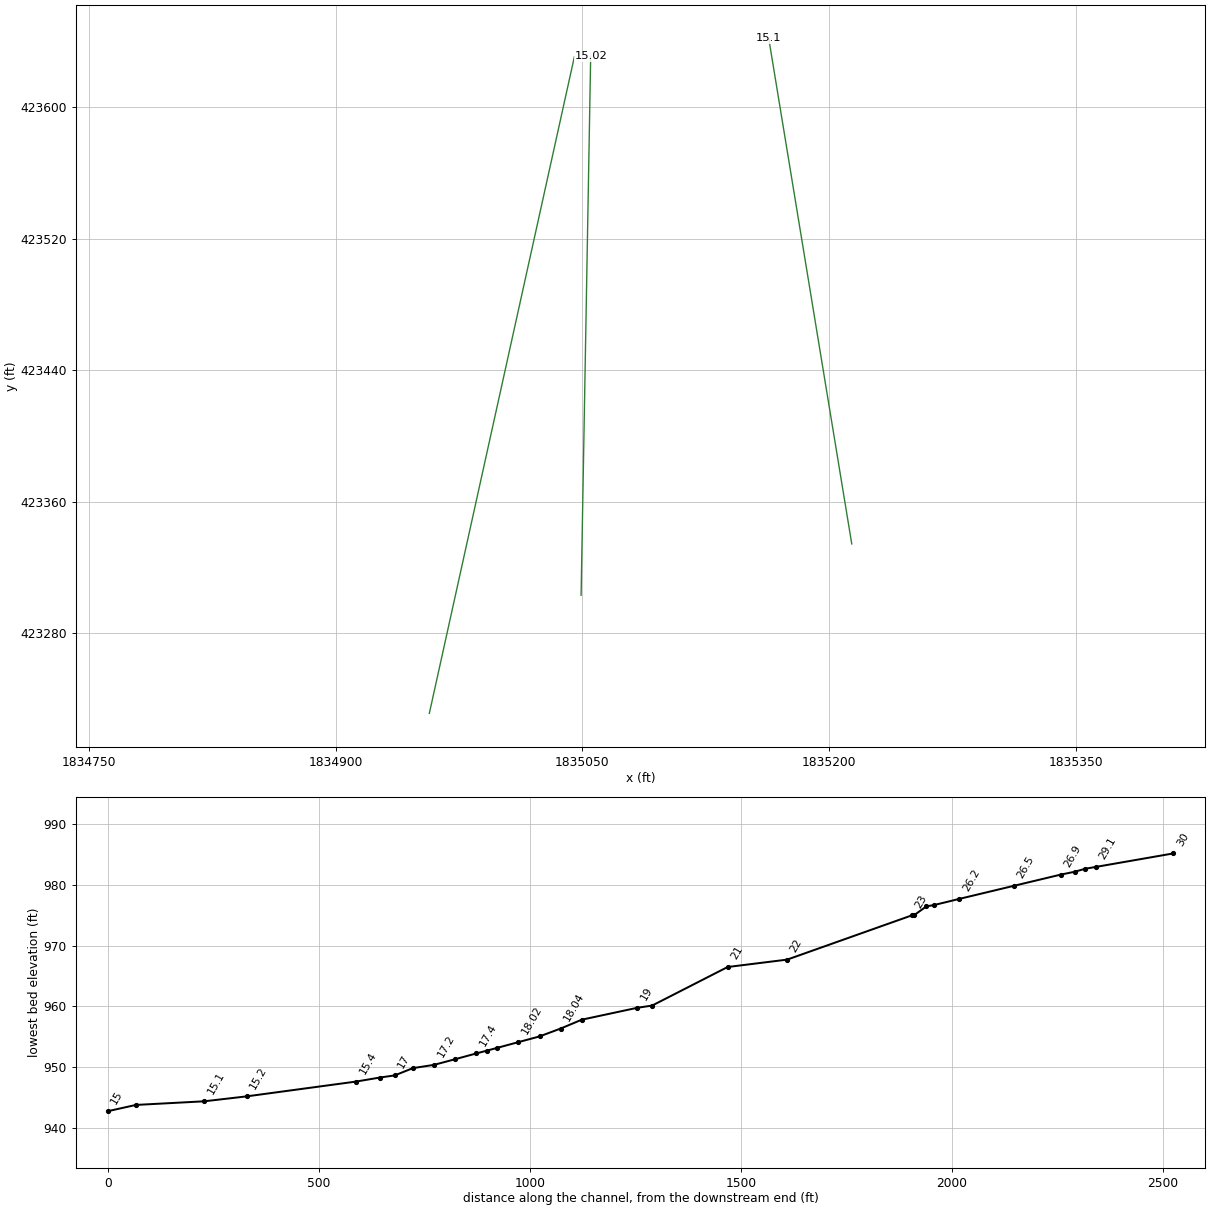
HEC-RAS study BurroughsRun.prj: Burroughs Run

--- BurroughsRun.g02 (geometry) --- (continued)

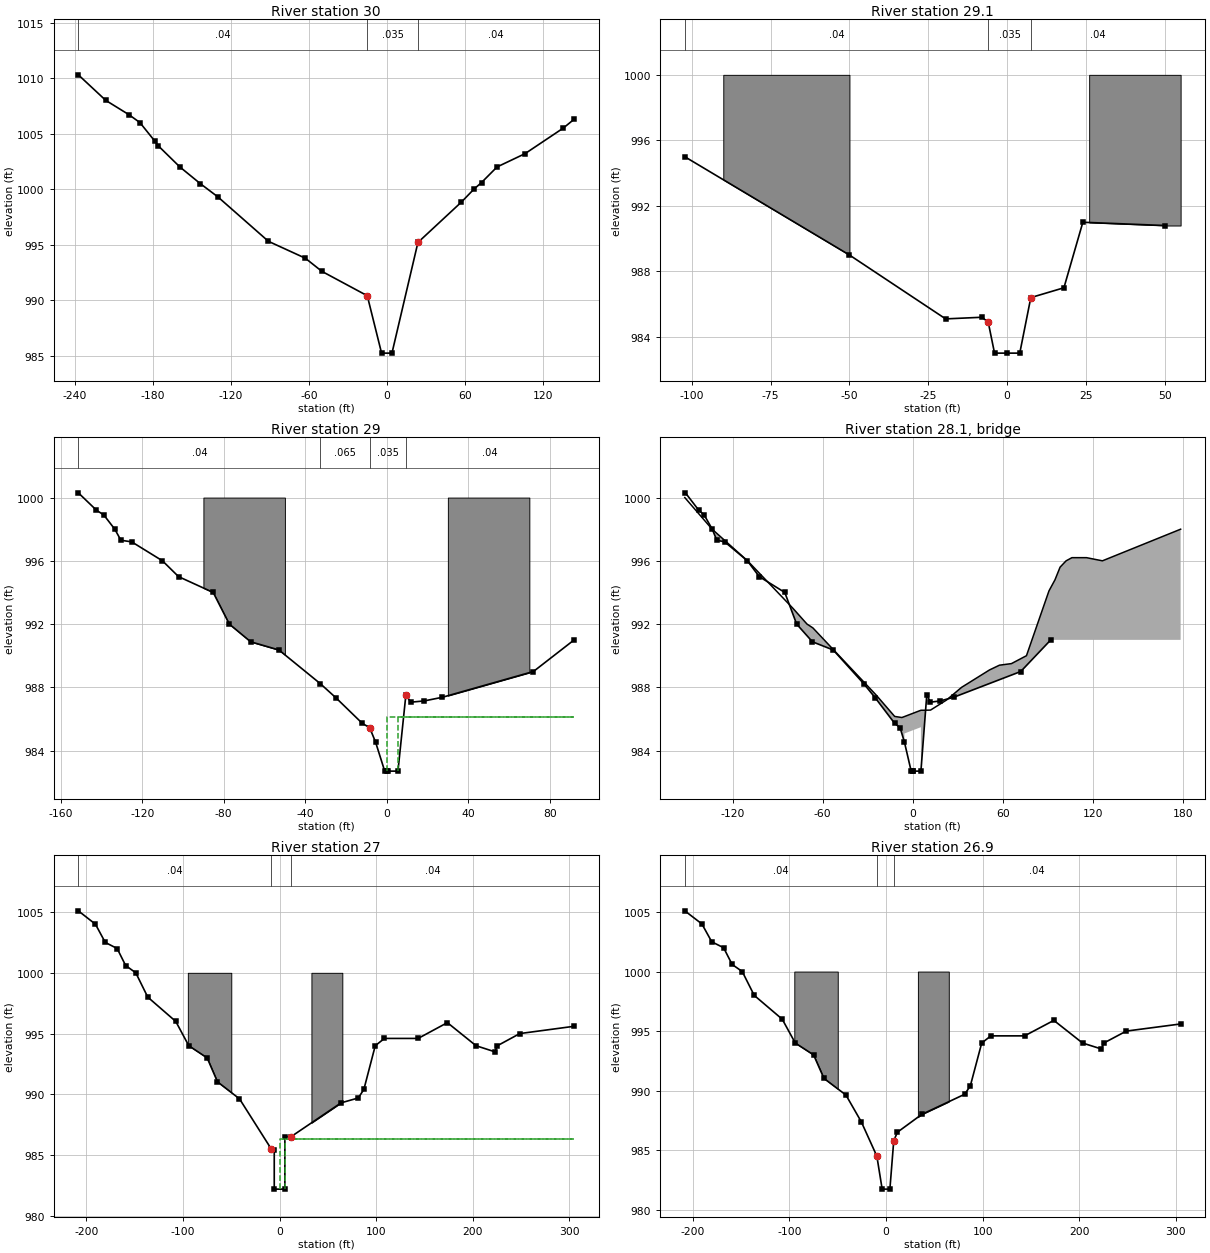
Type RM Length L Ch R = 1 ,30      ,170,183,185
BEGIN DESCRIPTION:
59+09
END DESCRIPTION:
#Sta/Elev= 23
  -237.5  1010.3  -216.4    1008  -198.4  1006.7  -190.1    1006  -178.4  1004.3
  -175.9  1003.9  -159.3    1002  -143.6  1000.5    -130   999.3   -91.1   995.3
   -62.7  993.78     -50   992.6     -15   990.4      -4  985.23       4  985.23
      24   995.2    57.5  998.84    67.1    1000      73  1000.6    84.9    1002
   106.5  1003.2   135.9  1005.5   144.3  1006.3
#Mann= 3 , 0 , 0
  -237.5     .04       0     -15    .035       0      24     .04       0
Bank Sta=-15,24
XS Rating Curve= 0 ,0
Exp/Cntr=0.3,0.1

Type RM Length L Ch R = 1 ,29.1    ,25.98,25.98,25.98
BEGIN DESCRIPTION:
Sta. 57+25
END DESCRIPTION:
#Sta/Elev= 12
  -102.2     995     -50     989   -19.5   985.1      -8   985.2      -6   984.9
      -4  983.01       0  983.01       4  983.01     7.5   986.4      18     987
      24     991      50   990.8
#Mann= 3 ,-1 , 0
  -102.2     .04       0      -6    .035       0     7.5     .04       0
#Block Obstruct= 2 ,-1
     -90     -50    1000      26      55    1000
Bank Sta=-6,7.5
XS Rating Curve= 0 ,0
Exp/Cntr=0.5,0.3

Type RM Length L Ch R = 1 ,29      ,25.1,25.1,25.1
BEGIN DESCRIPTION:
US Face Corvet
END DESCRIPTION:
#Sta/Elev= 27
  -151.4  1000.3  -142.5   999.2  -138.9   998.9  -133.5     998  -130.5   997.3
  -125.2   997.2  -110.1     996  -102.2     995   -85.2     994   -77.3     992
   -66.8  990.88   -52.9  990.36   -32.6  988.23   -24.8  987.32     -12  985.72
    -8.4  985.45    -5.5  984.54      -1   982.7       0   982.7      .5   982.7
     5.5   982.7     9.4  987.53    11.8  987.06    18.4  987.14    27.3  987.37
      72     989      92     991
#Mann= 4 ,-1 , 0
  -151.4     .04       0   -32.6    .065       0    -8.4    .035       0
     9.4     .04       0
#XS Ineff= 2 , 0
       0    -5.5   986.1     5.5       0   986.1
Permanent Ineff=
       T       T
#Block Obstruct= 2 ,-1
     -90     -50    1000      30      70    1000
Bank Sta=-8.4,9.4
XS Rating Curve= 0 ,0
Exp/Cntr=0.5,0.3

Type RM Length L Ch R = 3 ,28.1    ,,,
BEGIN DESCRIPTION:
Corvet Avenue
END DESCRIPTION:
Bridge Culvert--1,0,-1,-1, 0
Deck Dist Width WeirC Skew NumUp NumDn MinLoCord MaxHiCord MaxSubmerge Is_Ogee
0.5,22,2.6,0, 28, 28, , , 0.95, 0, 0,0,,
  -151.8  -133.6    -110   -79.8   -70.4   -66.5   -24.5     -12    -7.2    -5.5
    -5.5     5.5    7.45    11.9    22.6    32.6    51.2    57.8    65.8    75.8
    90.8    94.8    98.2   102.2   106.1   115.8   126.4   178.5
    1000     998     996     993     992  991.76  987.53  986.16  986.09  986.15
  986.15  986.55  986.55  986.56   987.2     988   989.1   989.4   989.5     990
   994.1   994.8   995.6     996   996.2   996.2     996     998
                                                                                
  985.08  985.48
                                                                
  -151.8  -133.6    -110   -79.8   -70.4   -66.5   -24.5     -12    -7.2    -5.5
    -5.5     5.5     5.5    11.9    22.6    32.6    51.2    57.8    65.8    75.8
    90.8    94.8    98.2   102.2   106.1   115.8   126.4   178.5
    1000     998     996     993     992  991.76  987.53  986.16  986.09  986.15
  986.15  986.55  986.55  986.56   987.2     988   989.1   989.4   989.5     990
   994.1   994.8   995.6     996   996.2   996.2     996     998
                                                                                
  985.08  985.48
                                                                
BR Coef=-1 , 0 , 0 ,, 0 ,,,0.8,0,,0,985.46
WSPro=,,,, 1 ,,,, 0 ,,,, 0 ,,,,-1 ,-1 ,-1 , 0 , 0 , 0 , 0 , 0
BC Design=,, 0 ,, 0 ,,,,,,
BC Use User HTab Curves=0
BC User HTab FreeFlow(D)= 0

Type RM Length L Ch R = 1 ,27      ,39.97,32.97,27.02
BEGIN DESCRIPTION:
DS Face Corvet
END DESCRIPTION:
#Sta/Elev= 30
  -208.4  1005.1  -190.7    1004  -180.5  1002.5  -168.2    1002  -159.4  1000.6
  -148.9    1000  -136.5     998  -107.5     996     -94     994     -75     993
   -64.3  991.03   -41.5  989.63    -8.8  985.53    -5.5  985.39    -5.5   982.2
     5.5   982.2     5.5   986.5    11.8  986.51    63.7   989.3    81.5   989.7
    87.3   990.4    99.1     994   108.6   994.6   143.5   994.6   173.8   995.9
   203.5     994     223   993.5   225.6     994   248.8     995   305.1   995.6
#Mann= 3 , 0 , 0
  -208.4     .04       0    -8.8    .035       0    11.8     .04       0
#XS Ineff= 2 , 0
       0    -5.5   986.3     5.5       0   986.3
Permanent Ineff=
       F       F
#Block Obstruct= 2 ,-1
     -95     -50    1000      33      65    1000
Bank Sta=-8.8,11.8
XS Rating Curve= 0 ,0
Exp/Cntr=0.5,0.3

Type RM Length L Ch R = 1 ,26.9    ,120,110,73
BEGIN DESCRIPTION:
Sta. 56+50
END DESCRIPTION:
#Sta/Elev= 30
  -208.4  1005.1  -190.7    1004  -180.5  1002.5  -168.2    1002  -159.4  1000.6
  -148.9    1000  -136.5     998  -107.5     996     -94     994     -75     993
   -64.3  991.03   -41.5  989.63   -25.6  987.38    -9.5   984.5      -4  981.73
       4  981.73       8   985.8    11.8  986.51    36.9     988    81.5   989.7
    87.3   990.4    99.1     994   108.6   994.6   143.5   994.6   173.8   995.9
   203.5     994     223   993.5   225.6     994   248.8     995   305.1   995.6
#Mann= 3 , 0 , 0
  -208.4     .04       0    -9.5    .035       0       8     .04       0
#Block Obstruct= 2 ,-1
     -95     -50    1000      33      65    1000
Bank Sta=-9.5,8
XS Rating Curve= 0 ,0
Exp/Cntr=0.5,0.3

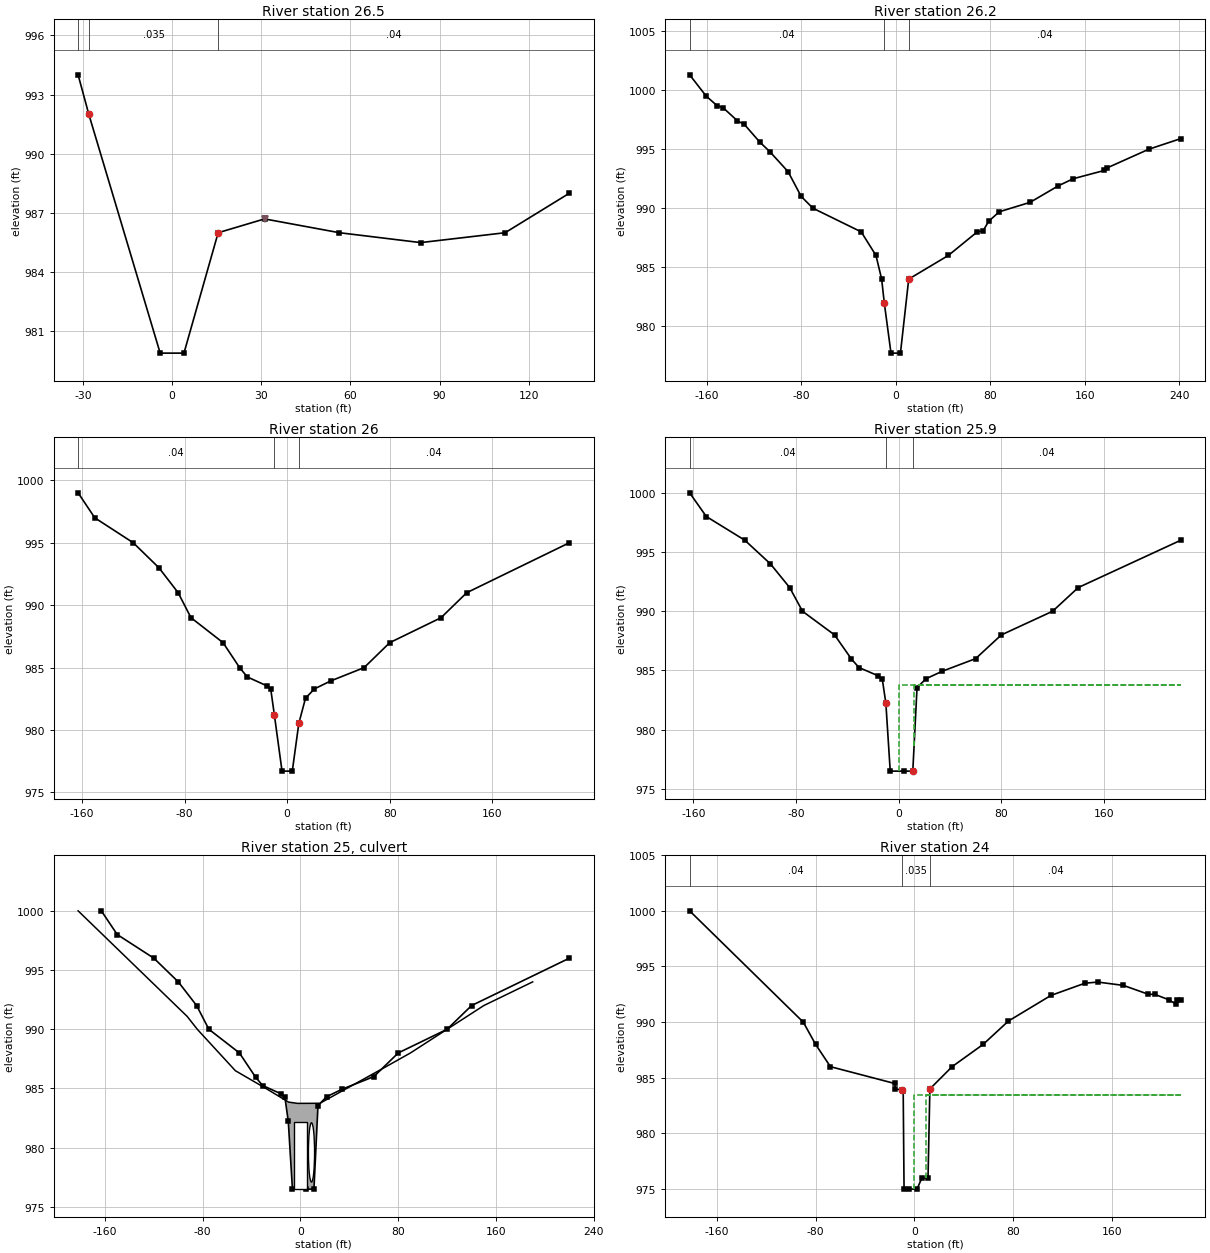
Type RM Length L Ch R = 1 ,26.5    ,140,130,90
BEGIN DESCRIPTION:
55+41
END DESCRIPTION:
#Sta/Elev= 10
   -31.6     994     -28     992      -4   979.9       4   979.9    15.5     986
    31.1   986.7    56.3     986    83.6   985.5     112     986   133.6     988
#Mann= 3 , 0 , 0
   -31.6     .04       0     -28    .035       0    15.5     .04       0
Levee=0,,,-1,31.1,986.7,,
Bank Sta=-28,15.5
XS Rating Curve= 0 ,0
Exp/Cntr=0.3,0.1

Type RM Length L Ch R = 1 ,26.2    ,60,60,60
BEGIN DESCRIPTION:
54+11
END DESCRIPTION:
#Sta/Elev= 30
  -174.4  1001.3  -160.4   999.5  -151.3   998.7  -145.9   998.5  -133.9   997.4
  -128.1   997.1    -115   995.6  -106.6   994.8   -91.1   993.1     -80     991
     -70     990   -29.2     988   -16.7     986   -11.9     984    -9.7     982
      -4  977.73       4  977.73      11     984    44.5     986      69     988
      74   988.1    78.7   988.9    87.6   989.7   113.7   990.5   137.6   991.9
   150.2   992.5   176.5   993.2   178.5   993.4   214.2     995   241.3   995.9
#Mann= 3 , 0 , 0
  -174.4     .04       0    -9.7    .035       0      11     .04       0
Bank Sta=-9.7,11
XS Rating Curve= 0 ,0
Exp/Cntr=0.3,0.1

Type RM Length L Ch R = 1 ,26      ,18,18,18
BEGIN DESCRIPTION:
53+51
END DESCRIPTION:
#Sta/Elev= 23
    -163     999    -150     997    -120     995    -100     993     -85     991
     -75     989     -50     987   -36.8  984.96     -31  984.25   -15.8  983.54
   -12.8  983.28     -10  981.23      -4  976.71       4  976.71     9.1  980.54
    14.3  982.55    21.3   983.3    34.1  983.94      60     985      80     987
     120     989     140     991     220     995
#Mann= 3 , 0 , 0
    -163     .04       0     -10    .035       0     9.1     .04       0
Bank Sta=-10,9.1
XS Rating Curve= 0 ,0
Exp/Cntr=0.5,0.3

Type RM Length L Ch R = 1 ,25.9    ,30,30,30
BEGIN DESCRIPTION:
US Face Killarney
END DESCRIPTION:
#Sta/Elev= 23
    -163    1000    -150     998    -120     996    -100     994     -85     992
     -75     990     -50     988   -36.8  985.96     -31  985.25   -15.8  984.54
   -12.8  984.28     -10  982.23    -6.6   976.5     4.3   976.5      11   976.5
    14.3  983.55    21.3   984.3    34.1  984.94      60     986      80     988
     120     990     140     992     220     996
#Mann= 3 , 0 , 0
    -163     .04       0     -10    .035       0      11     .04       0
#XS Ineff= 2 , 0
       0      -5  983.75      12       0  983.75
Permanent Ineff=
       T       T
Bank Sta=-10,11
XS Rating Curve= 0 ,0
Exp/Cntr=0.5,0.3

Type RM Length L Ch R = 2 ,25      ,,,
BEGIN DESCRIPTION:
Killarney Drive
END DESCRIPTION:
Bridge Culvert--1,0,-1,-1, 0
Deck Dist Width WeirC Skew NumUp NumDn MinLoCord MaxHiCord MaxSubmerge Is_Ogee
1,28,2.6,0, 13, 13, 983.75, , 0.95, 0, 0,0,,
    -182   -92.7   -84.4   -53.3   -27.6    -9.8    -2.4    15.9      66      90
     120     150     190
    1000  991.08  989.99   986.5  984.96  983.85  983.74  983.75  986.61     988
     990     992     994
                                                                                
                        
    -182   -92.7   -84.4   -53.3   -27.6    -9.8    -2.4    15.9      66      90
     120     150     190
    1000  991.08  989.99   986.5  984.96  983.85  983.74  983.75  986.61     988
     990     992     994
                                                                                
                        
BR Coef=-1 , 0 , 0 ,, 0 ,,,0.8,-1,,0,
WSPro=,,,, 1 ,,,, 0 ,,,, 0 ,,,,-1 ,-1 ,-1 , 0 , 0 , 0 , 0 , 0
Culvert=2,5.7,10,28,0.013,0.5,1,8,1,976.5,0,975,-3,Culvert #1  , 0 ,1
Culvert Bottom n=0.013
Culvert=1,5,,28,0.013,0.5,1,1,1,977.1,9,975.5,6,Culvert #2  , 0 ,1
Culvert Bottom n=0.013
BC Design=,, 0 ,, 0 ,,,,,,
BC Use User HTab Curves=0
BC User HTab FreeFlow(D)= 0

Type RM Length L Ch R = 1 ,24      ,5,5,80
BEGIN DESCRIPTION:
DS Face Killarney Dr.
END DESCRIPTION:
#Sta/Elev= 27
    -182    1000     -90     990     -80     988     -68     986     -16  984.49
   -15.4  984.01    -9.7  983.89    -9.1  983.82    -8.4     975      -4     975
     2.1     975       6     976      11     976    12.5     984    30.5     986
    55.6     988    76.1   990.1   110.5   992.4   138.1   993.5   148.5   993.6
   169.2   993.3   189.5   992.5   194.5   992.5   206.2     992   211.8   991.6
   212.2     992   215.7     992
#Mann= 3 , 0 , 0
    -182     .04       0    -9.7    .035       0    12.5     .04       0
#XS Ineff= 2 , 0
       0      -8   983.5       9       0   983.5
Permanent Ineff=
       F       F
Bank Sta=-9.7,12.5
XS Rating Curve= 0 ,0
Exp/Cntr=0.5,0.3

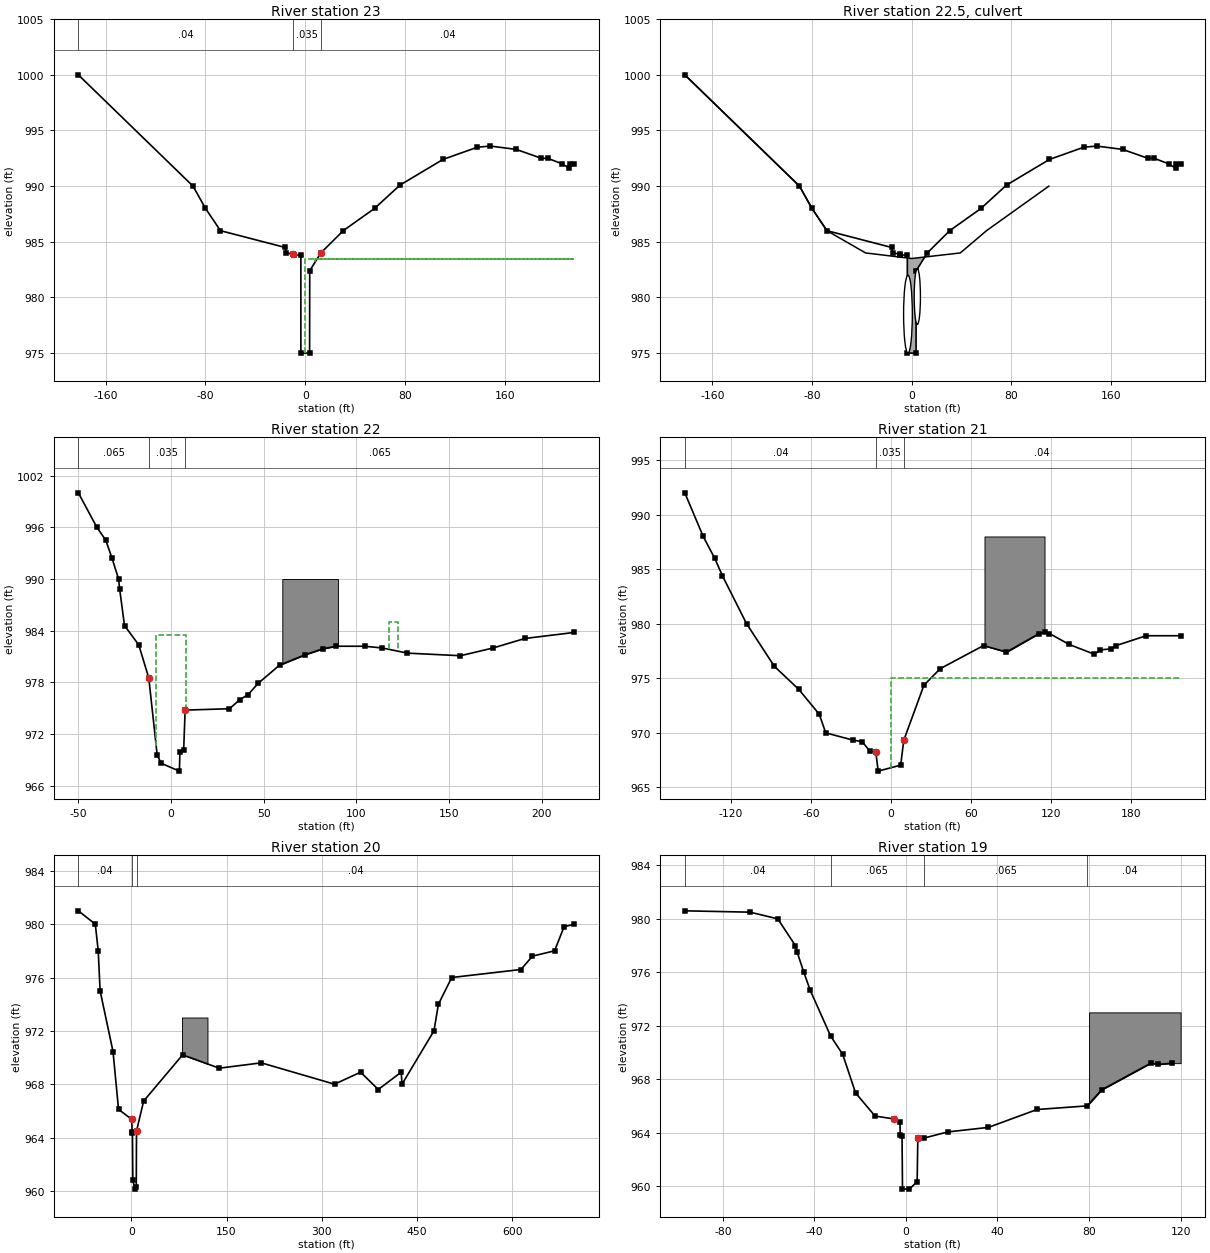
Type RM Length L Ch R = 1 ,23      ,295,295,295
BEGIN DESCRIPTION:
US Face- Killarney Dr. 84" CMP
END DESCRIPTION:
#Sta/Elev= 26
    -182    1000     -90     990     -80     988     -68     986     -16  984.49
   -15.4  984.01    -9.7  983.89    -9.1  983.82    -3.5   983.8    -3.5     975
     3.5     975     3.6   982.4    12.5     984    30.5     986    55.6     988
    76.1   990.1   110.5   992.4   138.1   993.5   148.5   993.6   169.2   993.3
   189.5   992.5   194.5   992.5   206.2     992   211.8   991.6   212.2     992
   215.7     992
#Mann= 3 , 0 , 0
    -182     .04       0    -9.7    .035       0    12.5     .04       0
#XS Ineff= 2 , 0
       0      -8   983.5       8       0   983.5
Permanent Ineff=
       T       T
Bank Sta=-9.7,12.5
XS Rating Curve= 0 ,0
Exp/Cntr=0.5,0.3

Type RM Length L Ch R = 2 ,22.5    ,,,
BEGIN DESCRIPTION:
Dogwood Avenue
END DESCRIPTION:
Bridge Culvert--1,0,-1,-1, 0
Deck Dist Width WeirC Skew NumUp NumDn MinLoCord MaxHiCord MaxSubmerge Is_Ogee
2,290,2.6,0, 10, 11, , , 0.95, 0, 0,0,,
    -182     -90     -80     -68     -37       0      39      60      85     110
    1000     990     988     986     984   983.5     984     986     988     990
                                                                                
    -182     -90     -80     -68     -37       0      39      60      85     110
     300
    1000     990     988     986     984   983.5     984     986     988     990
     990
                                                                                
        
BR Coef=-1 , 0 , 0 ,, 0 ,,,0.8,-1,,0,
WSPro=,,,, 1 ,,,, 0 ,,,, 0 ,,,,-1 ,-1 ,-1 , 0 , 0 , 0 , 0 , 0
Culvert=1,7,,290,0.024,0.5,1,2,1,975,-3,969.25,0,Culvert #1  , 0 ,2
Culvert Bottom n=0.024
Culvert=1,5,,250,0.013,0.5,1,1,1,977.58,4.5,972.58,120,Culvert #2  , 0 ,2
Culvert Bottom n=0.013
BC Design=,, 0 ,, 0 ,,,,,,
BC Use User HTab Curves=0
BC User HTab FreeFlow(D)= 0

Type RM Length L Ch R = 1 ,22      ,141,141,141
BEGIN DESCRIPTION:
DS Face 84" Under Killarney Dr.
END DESCRIPTION:
#Sta/Elev= 30
     -50    1000     -40     996   -35.2   994.5   -31.8   992.4   -28.3     990
   -27.7   988.8   -25.1   984.6   -17.4  982.35     -12  978.51    -7.5  969.61
    -5.4  968.63     4.5  967.71     4.8  969.94     6.8  970.11     7.6  974.79
    31.5  974.95    37.1     976    41.6   976.6      47   977.9    58.5     980
    72.1   981.2    81.8   981.9    88.9   982.2   104.4   982.2   113.9     982
   127.5   981.4   156.1   981.1   173.7     982   190.8   983.1   217.4   983.8
#Mann= 3 , 0 , 0
     -50    .065       0     -12    .035       0     7.6    .065       0
#XS Ineff= 2 ,-1
      -8       8   983.5   117.5   122.5     985
Permanent Ineff=
       F       F
#Block Obstruct= 1 ,-1
      60      90     990
Bank Sta=-12,7.6
XS Rating Curve= 0 ,0
Exp/Cntr=0.5,0.3

Type RM Length L Ch R = 1 ,21      ,178.8,178.8,178.8
#Sta/Elev= 30
  -154.6     992  -140.8     988  -132.2     986  -126.4   984.4  -108.3     980
   -87.5   976.1   -69.3     974   -53.8   971.7     -49     970   -28.5  969.33
   -21.7   969.2   -15.9  968.32   -11.4  968.21    -9.7  966.49     7.2  967.04
     9.5  969.31    24.6  974.36    36.8  975.88    69.3     978    86.5   977.4
   110.9   979.1   115.2   979.2   118.7   979.1   133.5   978.1   152.4   977.2
   156.7   977.6   164.9   977.7   168.7     978   191.2   978.9     217   978.9
#Mann= 3 , 0 , 0
  -154.6     .04       0   -11.4    .035       0     9.5     .04       0
#XS Ineff= 2 , 0
       0     -20     975               0
Permanent Ineff=
       F       F
#Block Obstruct= 1 ,-1
      70     115     988
Bank Sta=-11.4,9.5
XS Rating Curve= 0 ,0
Exp/Cntr=0.3,0.1

Type RM Length L Ch R = 1 ,20      ,34.72,34.72,34.72
#Sta/Elev= 30
   -83.3     981   -56.6     980     -52     978     -49     975   -28.7  970.45
     -20  966.11      .9  965.36     1.3  964.39     1.9  964.34     2.5   960.8
     5.7  960.13     7.9  960.31     8.3   964.5    19.6  966.74    80.9   970.2
   138.5   969.2   204.8   969.6     320     968   361.1   968.9   388.9   967.6
     425   968.9   426.3     968   476.6     972   483.6     974   504.6     976
   613.5   976.6   631.6   977.6   666.4     978   681.4   979.8   697.3     980
#Mann= 3 , 0 , 0
   -83.3     .04       0      .9    .035       0     8.3     .04       0
#Block Obstruct= 1 ,-1
      80     120     973
Bank Sta=0.9,8.3
XS Rating Curve= 0 ,0
Exp/Cntr=0.3,0.1

Type RM Length L Ch R = 1 ,19      ,132,132,132
#Sta/Elev= 28
   -96.6   980.6   -68.1   980.5     -56     980   -48.3     978   -47.5   977.5
   -44.6     976   -41.8  974.65   -32.9  971.23   -27.6  969.85     -22  966.97
   -13.5  965.24    -5.1  965.02    -2.6  964.78    -2.5  963.79    -1.7  963.74
    -1.5  959.78     1.5  959.77     4.9  960.33     5.2  963.61     7.9  963.59
    18.2  964.05      36  964.39    57.3  965.73    79.2     966    85.5   967.2
     107   969.2   110.2   969.1   116.4   969.2
#Mann= 4 ,-1 , 0
   -96.6     .04       0   -32.9    .065       0     7.9    .065       0
    79.2     .04       0
#Block Obstruct= 1 ,-1
      80     120     973
Bank Sta=-5.1,5.2
XS Rating Curve= 0 ,0
Exp/Cntr=0.3,0.1

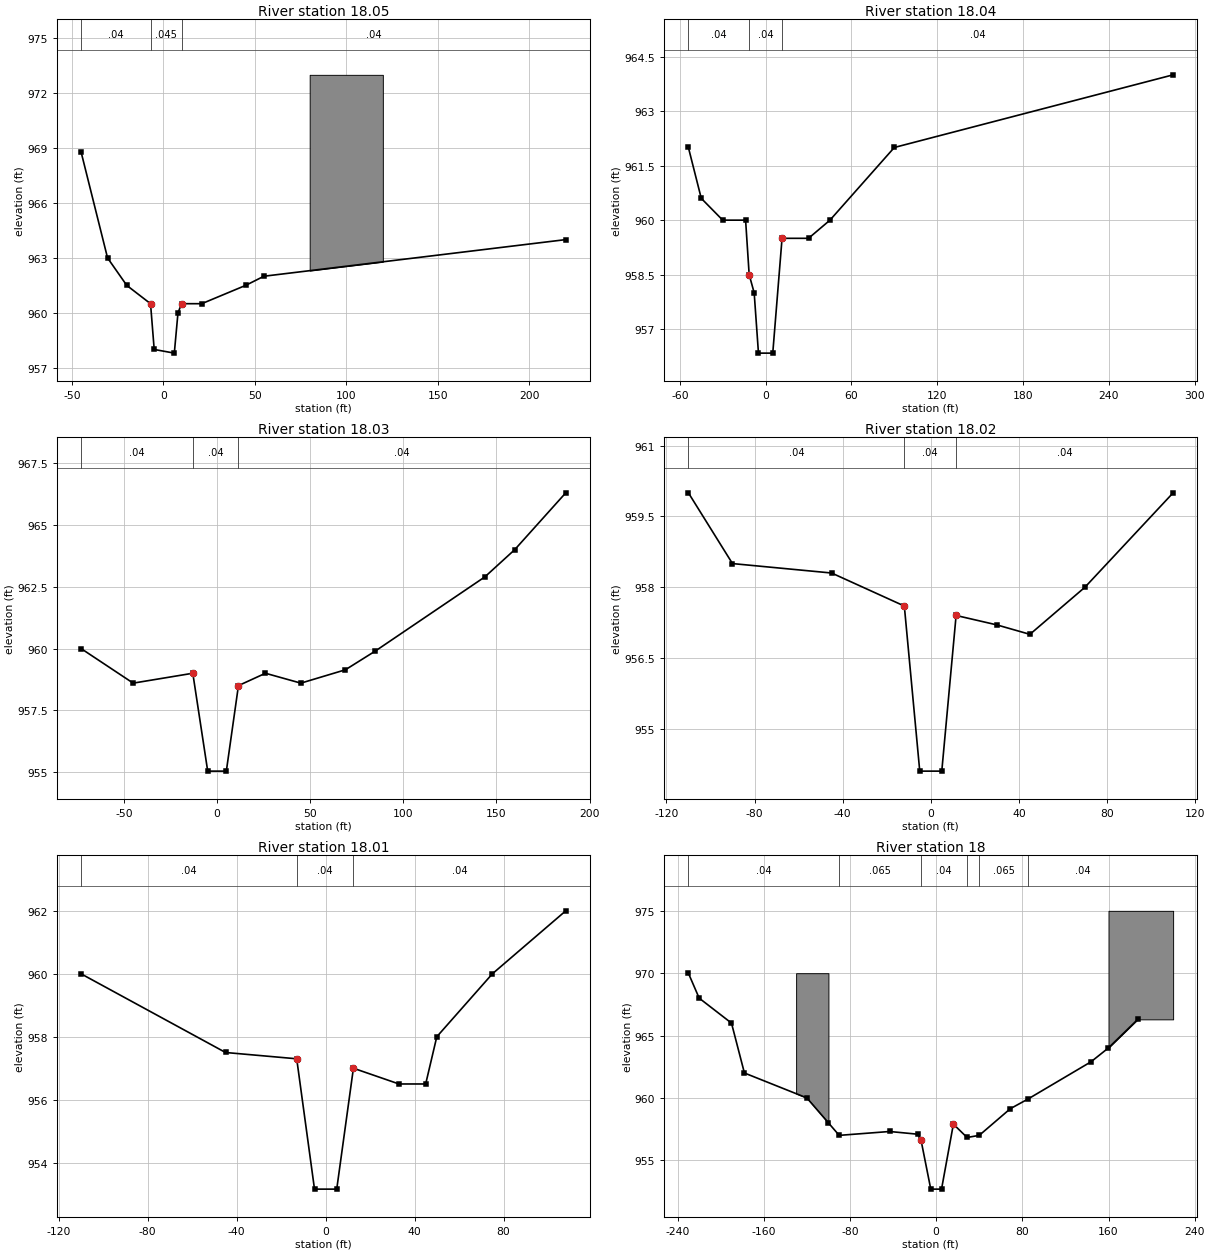
Type RM Length L Ch R = 1 ,18.05   ,50,50,50
BEGIN DESCRIPTION:
Sta. 6+00 (SB Restoration Section)
END DESCRIPTION:
#Sta/Elev= 12
     -45   968.8   -30.5     963     -20   961.5      -7   960.5      -5     958
       6   957.8       8     960      10   960.5      21   960.5      45   961.5
      55     962     220     964
#Mann= 3 , 0 , 0
     -45     .04       0      -7    .045       0      10     .04       0
#Block Obstruct= 1 ,-1
      80     120     973
Bank Sta=-7,10
XS Rating Curve= 0 ,0
Exp/Cntr=0.3,0.1

Type RM Length L Ch R = 1 ,18.04   ,50,50,50
BEGIN DESCRIPTION:
Sta. 5+50 BR (SB Restoration Section)
END DESCRIPTION:
#Sta/Elev= 13
     -54     962     -45   960.6     -30     960     -14     960   -11.5   958.5
      -8     958      -5  956.34       5  956.34    11.5   959.5      30   959.5
      45     960      90     962     285     964
#Mann= 3 , 0 , 0
     -54     .04       0   -11.5     .04       0    11.5     .04       0
Bank Sta=-11.5,11.5
XS Rating Curve= 0 ,0
Exp/Cntr=0.3,0.1

Type RM Length L Ch R = 1 ,18.03   ,50,50,50
BEGIN DESCRIPTION:
Sta. 5+00 BR (SB Restoration Section)
END DESCRIPTION:
#Sta/Elev= 13
     -73     960     -45   958.6     -13     959      -5  955.04       5  955.04
    11.5   958.5      26     959      45   958.6    68.9  959.14      85   959.9
   143.8   962.9   159.8     964   187.2   966.3
#Mann= 3 , 0 , 0
     -73     .04       0     -13     .04       0    11.5     .04       0
Bank Sta=-13,11.5
XS Rating Curve= 0 ,0
Exp/Cntr=0.3,0.1

Type RM Length L Ch R = 1 ,18.02   ,50,50,50
BEGIN DESCRIPTION:
Sta. 4+50 BR (SB Restoration Section)
END DESCRIPTION:
#Sta/Elev= 11
    -110     960     -90   958.5     -45   958.3     -12   957.6      -5   954.1
       5   954.1    11.5   957.4      30   957.2      45     957      70     958
     110     960
#Mann= 3 , 0 , 0
    -110     .04       0     -12     .04       0    11.5     .04       0
Bank Sta=-12,11.5
XS Rating Curve= 0 ,0
Exp/Cntr=0.3,0.1

Type RM Length L Ch R = 1 ,18.01   ,25,25,25
BEGIN DESCRIPTION:
Sta. 4+00 BR (SB Restoration Section)
END DESCRIPTION:
#Sta/Elev= 11
    -110     960     -45   957.5     -13   957.3      -5  953.16       5  953.16
    12.5     957      33   956.5      45   956.5      50     958      75     960
     108     962
#Mann= 3 , 0 , 0
    -110     .04       0     -13     .04       0    12.5     .04       0
Bank Sta=-13,12.5
XS Rating Curve= 0 ,0
Exp/Cntr=0.3,0.1

Type RM Length L Ch R = 1 ,18      ,25,25,25
BEGIN DESCRIPTION:
=Sta. 3+75 (SB Restoration Section)
END DESCRIPTION:
#Sta/Elev= 20
    -230     970    -220     968    -190     966    -178     962    -120     960
    -100     958     -90     957   -43.2  957.31   -16.8  957.09     -14   956.6
      -5  952.69       5  952.69      16   957.9    28.7  956.83      40     957
    68.9  959.14      85   959.9   143.8   962.9   159.8     964   187.2   966.3
#Mann= 6 ,-1 , 0
    -230     .04       0     -90    .065       0     -14     .04       0
    28.7     .04       0      40    .065       0      85     .04       0
#Block Obstruct= 2 ,-1
    -130    -100     970     160     220     975
Bank Sta=-14,16
XS Rating Curve= 0 ,0
Exp/Cntr=0.3,0.1

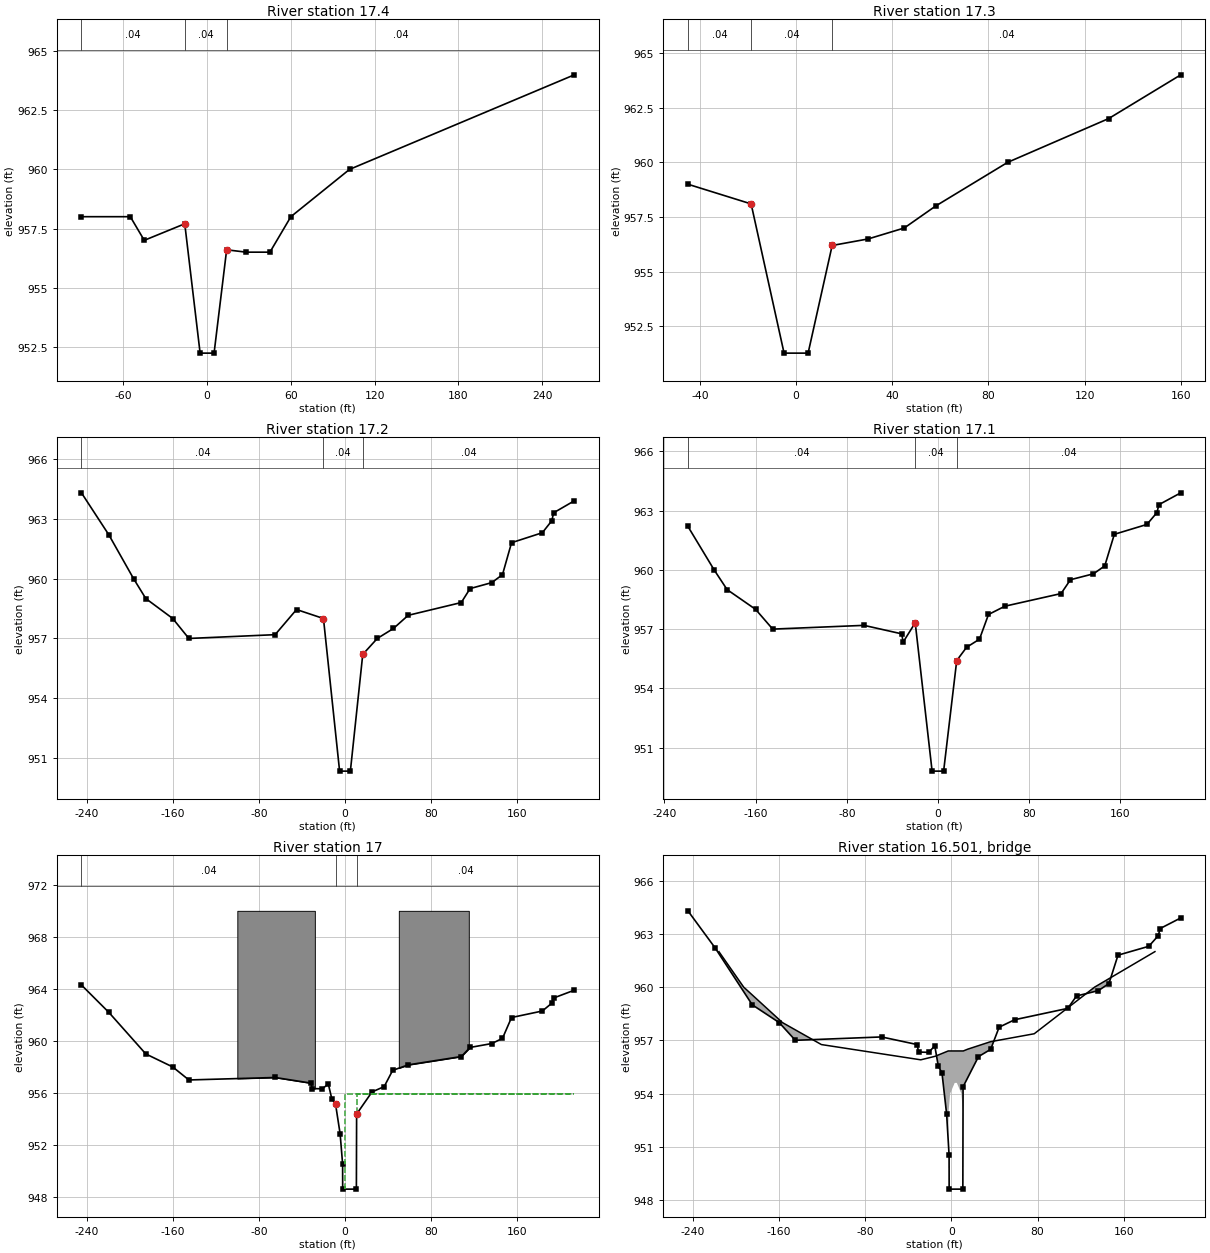
Type RM Length L Ch R = 1 ,17.4    ,50,50,50
BEGIN DESCRIPTION:
Sta. 3+50 BR (SB Restoration Section)
END DESCRIPTION:
#Sta/Elev= 12
     -90     958     -55     958     -45     957     -16   957.7      -5  952.23
       5  952.23      14   956.6      28   956.5      45   956.5      60     958
     102     960     263     964
#Mann= 3 , 0 , 0
     -90     .04       0     -16     .04       0      14     .04       0
Bank Sta=-16,14
XS Rating Curve= 0 ,0
Exp/Cntr=0.3,0.1

Type RM Length L Ch R = 1 ,17.3    ,45,50,55
BEGIN DESCRIPTION:
Sta. 3+00 BR (SB Restoration Section)
END DESCRIPTION:
#Sta/Elev= 11
     -45     959   -18.7   958.1      -5  951.28       5  951.28      15   956.2
      30   956.5      45     957      58     958      88     960     130     962
     160     964
#Mann= 3 , 0 , 0
     -45     .04       0   -18.7     .04       0      15     .04       0
Bank Sta=-18.7,15
XS Rating Curve= 0 ,0
Exp/Cntr=0.3,0.1

Type RM Length L Ch R = 1 ,17.2    ,20,50,70
BEGIN DESCRIPTION:
Sta. 2+50 BR (SB Restoration Section)
END DESCRIPTION:
#Sta/Elev= 24
  -244.8   964.3  -219.4   962.2  -196.4     960    -185     959    -160     958
    -145     957   -64.9  957.19     -45  958.45     -20     958      -5  950.35
       5  950.35    16.5   956.2      30     957      45   957.5    58.7  958.16
     108   958.8   116.2   959.5   136.4   959.8   146.3   960.2   154.7   961.8
   183.3   962.3   192.1   962.9   193.8   963.3     213   963.9
#Mann= 3 , 0 , 0
  -244.8     .04       0     -20     .04       0    16.5     .04       0
Bank Sta=-20,16.5
XS Rating Curve= 0 ,0
Exp/Cntr=0.3,0.1

Type RM Length L Ch R = 1 ,17.1    ,43,43,43
BEGIN DESCRIPTION:
Sta. 2+00 BR (SB Restoration Section)
END DESCRIPTION:
#Sta/Elev= 25
  -219.4   962.2  -196.4     960    -185     959    -160     958    -145     957
   -64.9  957.19   -31.8  956.76   -30.6  956.34  -19.97  957.32   -5.16  949.81
    4.95  949.81   16.45  955.41    25.1  956.08    36.4  956.49    44.3  957.74
    58.7  958.16     108   958.8   116.2   959.5   136.4   959.8   146.3   960.2
   154.7   961.8   183.3   962.3   192.1   962.9   193.8   963.3     213   963.9
#Mann= 3 , 0 , 0
  -219.4     .04       0  -19.97     .04       0   16.45     .04       0
Bank Sta=-19.97,16.45
XS Rating Curve= 0 ,0
Exp/Cntr=0.3,0.1

Type RM Length L Ch R = 1 ,17      ,36,36,36
BEGIN DESCRIPTION:
US Face Eastern Ave.
END DESCRIPTION:
#Sta/Elev= 30
  -244.8   964.3  -219.4   962.2    -185     959    -160     958    -145     957
   -64.9  957.19   -31.8  956.76   -30.6  956.34   -21.1  956.32   -15.5  956.69
   -12.2  955.54    -8.8  955.16    -4.5  952.85    -2.2  950.53   -2.15  948.61
   10.58  948.61    10.8  954.38    25.1  956.08    36.4  956.49    44.3  957.74
    58.7  958.16     108   958.8   116.2   959.5   136.4   959.8   146.3   960.2
   154.7   961.8   183.3   962.3   192.1   962.9   193.8   963.3     213   963.9
#Mann= 3 , 0 , 0
  -244.8     .04       0    -8.8     .04       0    10.8     .04       0
#XS Ineff= 2 , 0
       0    -3.5   955.9    11.5       0   955.9
Permanent Ineff=
       T       T
#Block Obstruct= 2 ,-1
    -100     -28     970      50     115     970
Bank Sta=-8.8,10.8
XS Rating Curve= 0 ,0
Exp/Cntr=0.5,0.3

Type RM Length L Ch R = 3 ,16.501  ,,,
BEGIN DESCRIPTION:
Eastern Avenue
END DESCRIPTION:
Bridge Culvert--1,0,-1,-1, 0
Deck Dist Width WeirC Skew NumUp NumDn MinLoCord MaxHiCord MaxSubmerge Is_Ogee
6,24,2.6,0, 22, 22, 956.1, , 0.95, 0, 0,0,,
    -216    -193    -157  -120.8   -28.5   -15.1      -3   -2.99    -2.5    -1.2
       3       4       5     9.2    10.5   10.99      11    15.1    36.2    76.9
     133     189
     962     960     958  956.76   955.9   956.1   956.4   956.4   956.4   956.4
   956.4   956.4   956.4   956.4   956.4   956.4   956.4   956.5  956.92  957.37
     960     962
                                                   948.6  951.82   953.1     954
   954.6   954.6   954.6     954   953.1  951.82   948.6
                
    -216    -193    -157  -120.8   -28.5   -15.1      -7   -6.99    -6.5    -5.2
      -1       0       1     5.2     6.5    6.99       7    15.1    36.2    76.9
     133     189
     962     960     958  956.76   955.9   956.1   956.4   956.4   956.4   956.4
   956.4   956.4   956.4   956.4   956.4   956.4   956.4   956.5  956.92  957.37
     960     962
                                                   948.6  951.82   953.1     954
   954.6   954.6   954.6     954   953.1  951.82   948.6
                
BR Coef=-1 , 0 , 0 ,, 0 ,,0.6,0.8,0,,0,954.6
WSPro=,,,, 1 ,,,, 0 ,,,, 0 ,,,,-1 ,-1 ,-1 , 0 , 0 , 0 , 0 , 0
BC Design=,, 0 ,, 0 ,,,,,,
BC Use User HTab Curves=0
BC User HTab FreeFlow(D)= 0

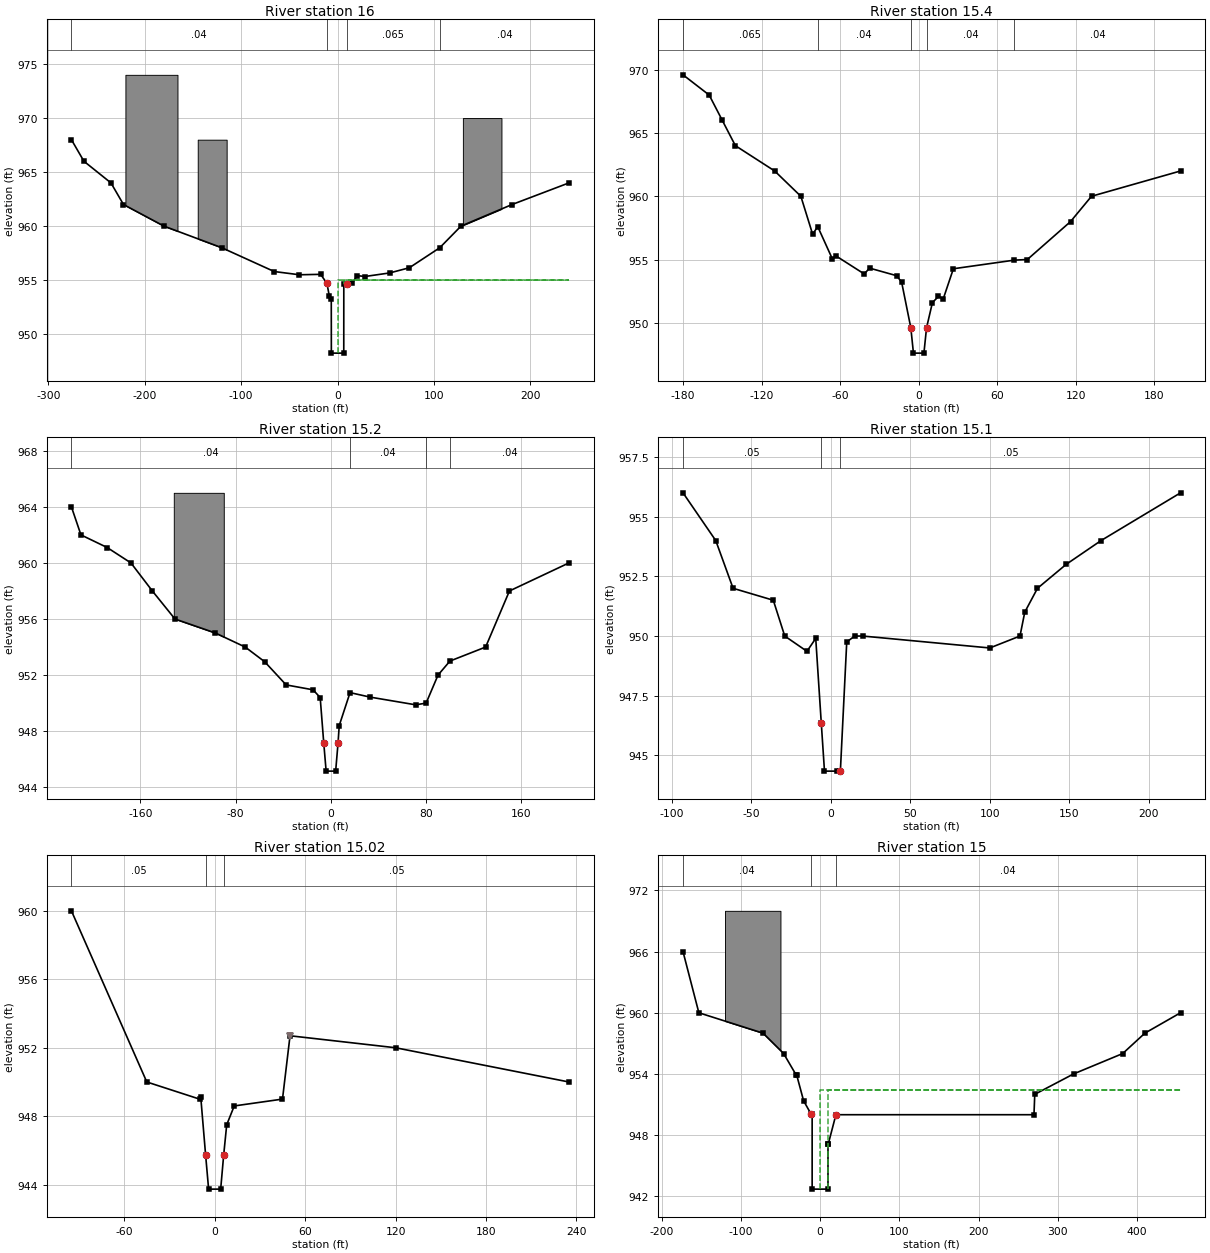
Type RM Length L Ch R = 1 ,16      ,80.01,54.99,36.99
BEGIN DESCRIPTION:
DS Face Eastern Ave
END DESCRIPTION:
#Sta/Elev= 25
    -276     968    -263     966    -235     964    -222     962    -180     960
    -120     958   -65.7   955.8   -39.5   955.5   -17.5  955.54     -11   954.7
    -8.5  953.52    -6.5  953.28   -6.42  948.25    6.46  948.25     6.5   954.6
     9.8  954.69    15.4  954.76    20.5  955.42    28.4  955.34    54.1  955.67
    74.5  956.15     106     958     128     960     181     962     240     964
#Mann= 4 ,-1 , 0
    -276     .04       0     -11    .035       0     9.8    .065       0
     106     .04       0
#XS Ineff= 2 , 0
       0      -7     955       7       0     955
Permanent Ineff=
       F       F
#Block Obstruct= 3 ,-1
    -220    -166     974    -145    -115     968     130     170     970
Bank Sta=-11,9.8
XS Rating Curve= 0 ,0
Exp/Cntr=0.5,0.3

Type RM Length L Ch R = 1 ,15.4    ,260.04,260.04,254.98
BEGIN DESCRIPTION:
39+85
END DESCRIPTION:
#Sta/Elev= 27
    -180   969.6    -160     968    -150     966    -140     964    -110     962
     -90     960     -81     957   -77.1   957.6   -65.9  955.04   -63.1  955.28
   -41.6  953.86   -37.5  954.32   -16.8  953.72     -13   953.2      -6   949.6
      -4   947.6       4   947.6       6   949.6    10.5   951.6   15.13  952.08
    18.8   951.9    26.5  954.27      73  954.95      83     955     116     958
     132     960     200     962
#Mann= 5 ,-1 , 0
    -180    .065       0   -77.1     .04       0      -6    .035       0
       6     .04       0      73     .04       0
Bank Sta=-6,6
XS Rating Curve= 0 ,0
Exp/Cntr=0.3,0.1

Type RM Length L Ch R = 1 ,15.2    ,100,100,50
#Sta/Elev= 26
    -218     964    -210     962    -188   961.1    -168     960    -150     958
    -131     956     -97     955     -72     954   -55.6  952.95   -37.6   951.3
     -15  950.95      -9   950.4      -6  947.15      -4  945.15       4  945.15
       6  947.15       7   948.4   16.08  950.75    32.9  950.43    71.2  949.88
      80     950      90     952     100     953     130     954     150     958
     200     960
#Mann= 4 ,-1 , 0
    -218     .04       0   16.08     .04       0      80    .065       0
     100     .04       0
#Block Obstruct= 1 ,-1
    -132     -90     965
Bank Sta=-6,6
XS Rating Curve= 0 ,0
Exp/Cntr=0.3,0.1

Type RM Length L Ch R = 1 ,15.1    ,200,162,150
BEGIN DESCRIPTION:
36+25
END DESCRIPTION:
XS GIS Cut Line= 2
 1835213.8956452  423334.3689688 1835163.4007836  423641.7814806
#Sta/Elev= 21
     -93     956   -72.4     954   -61.5     952   -36.2   951.5     -29     950
  -15.03  949.36    -9.5   949.9      -6  946.34      -4  944.34       4  944.34
       6  944.34      10  949.75   15.01     950      20     950     100   949.5
     119     950     122     951     130     952     148     953     170     954
     220     956
#Mann= 3 , 0 , 0
     -93     .05       0      -6    .035       0       6     .05       0
Bank Sta=-6,6
XS Rating Curve= 0 ,0
Exp/Cntr=0.3,0.1

Type RM Length L Ch R = 1 ,15.02   ,67,67,67
BEGIN DESCRIPTION:
34+63
END DESCRIPTION:
XS GIS Cut Line= 3
 1835049.3119321  423303.1496484 1835052.5378086  423484.7204182
 1835055.1358285  423630.9518283
#Sta/Elev= 14
     -95     960     -45     950     -10     949    -9.2   949.1      -6  945.74
      -4  943.74       4  943.74       6  945.74       8   947.5      13   948.6
      45     949      50   952.7     120     952     235     950
#Mann= 3 , 0 , 0
     -95     .05       0      -6    .035       0       6     .05       0
Levee=0,,,-1,50,952.7,,
Bank Sta=-6,6
XS Rating Curve= 0 ,0
Exp/Cntr=0.3,0.1

Type RM Length L Ch R = 1 ,15      ,197,197,197
BEGIN DESCRIPTION:
US Face Aspen St.
END DESCRIPTION:
XS GIS Cut Line= 2
 1834957.0171402    423231.29574 1835045.2278107  423630.6065226
#Sta/Elev= 20
    -173     966    -153     960     -72     958     -46     956   -30.5  953.94
   -29.4  953.86   -20.8  951.37   -11.3  950.05     -10  950.05     -10   942.7
      10   942.7      10  947.17    10.5  947.17      20     950     270     950
     271     952     320     954     382     956     410     958     455     960
#Mann= 3 , 0 , 0
    -173     .04       0   -11.3    .035       0      20     .04       0
#XS Ineff= 2 , 0
       0     -10   952.4      10       0   952.4
Permanent Ineff=
       T       T
#Block Obstruct= 1 ,-1
    -120     -50     970
Bank Sta=-11.3,20
XS Rating Curve= 0 ,0
Exp/Cntr=0.5,0.3