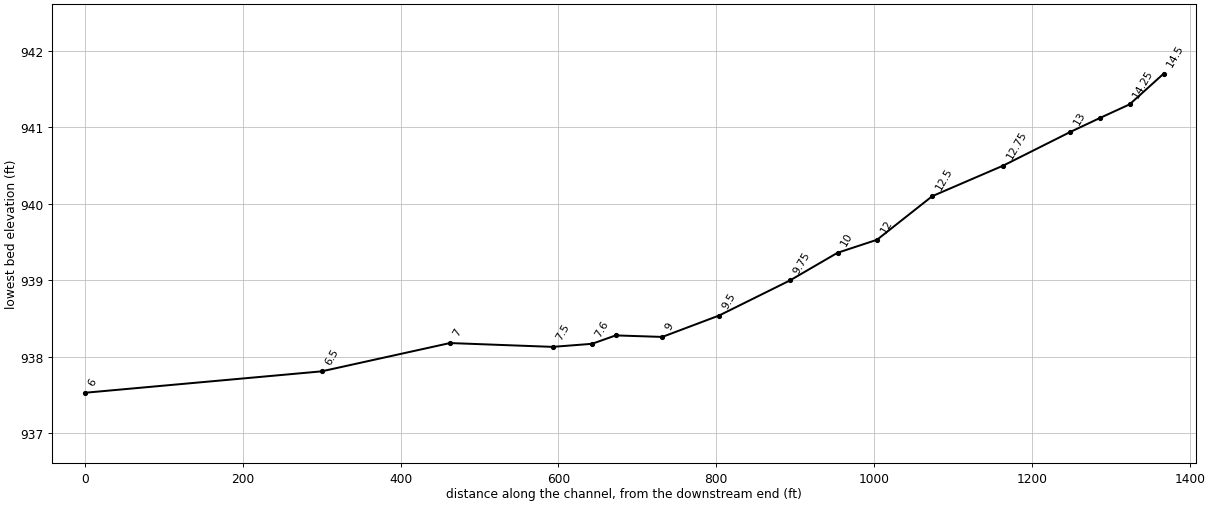
HEC-RAS study BurroughsRun.prj: Burroughs Run

--- BurroughsRun.g02 (geometry) --- (continued)

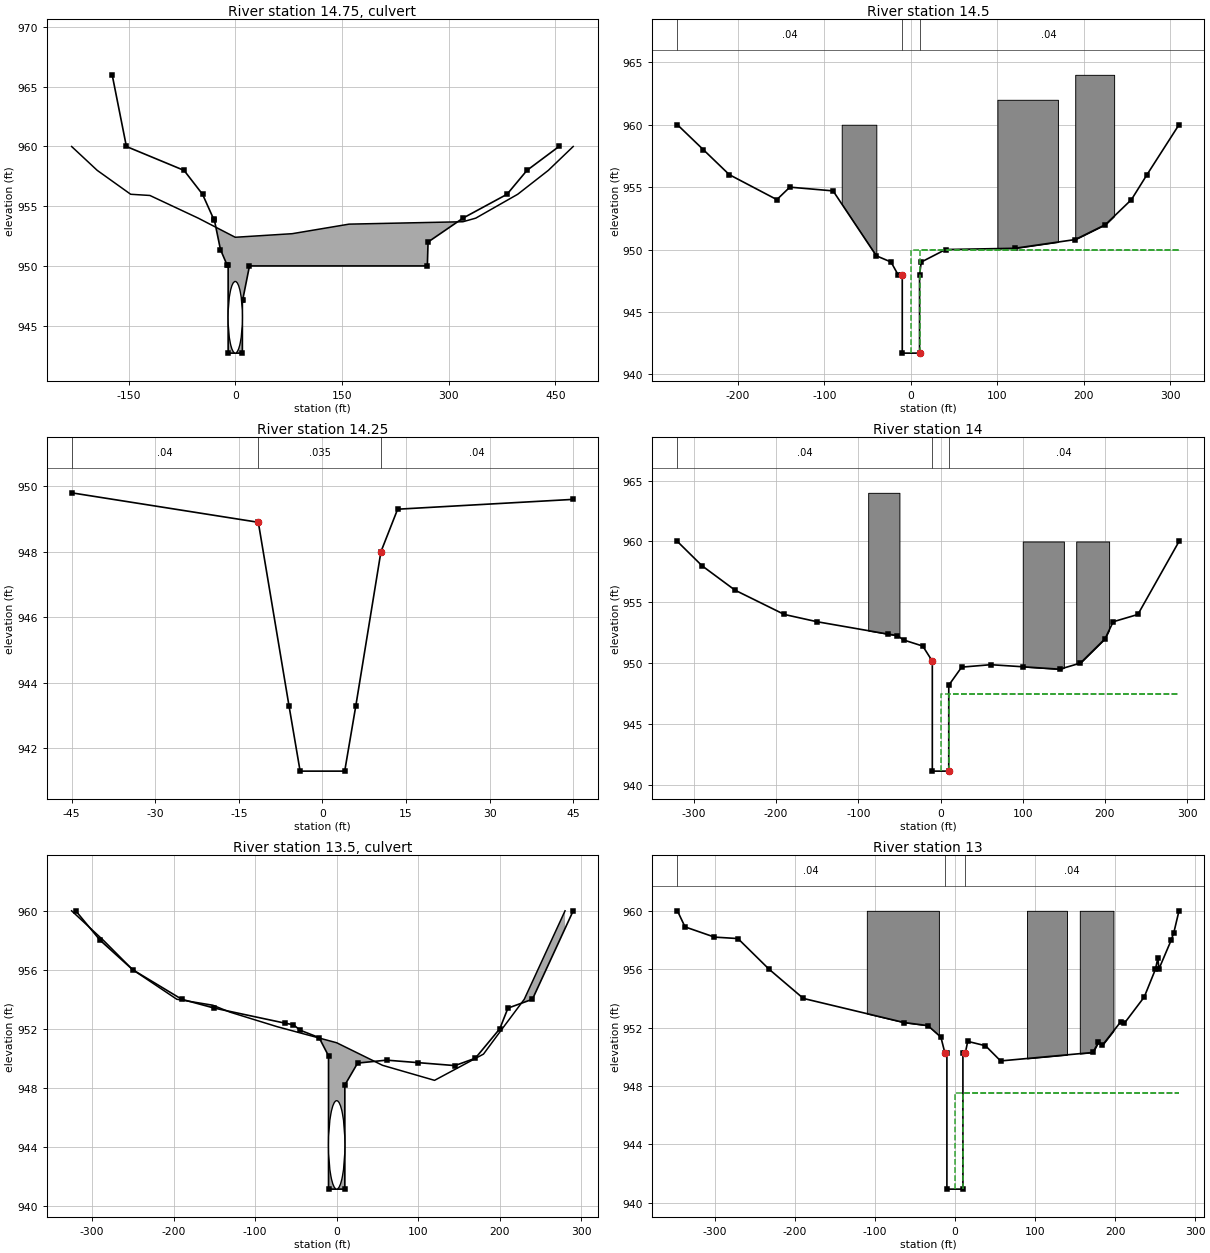
Type RM Length L Ch R = 2 ,14.75   ,,,
BEGIN DESCRIPTION:
Aspen Street
END DESCRIPTION:
Bridge Culvert--1,0,-1,-1, 0
Deck Dist Width WeirC Skew NumUp NumDn MinLoCord MaxHiCord MaxSubmerge Is_Ogee
1,195,2.6,0, 14, 14, 952.4, , 0.95, 0, 0,0,,
    -230    -194    -147    -120     -52       0      80     160     240     320
     338     397     440     475
     960     958     956   955.9     954   952.4   952.7   953.5   953.6   953.7
     954     956     958     960
                                                                                
                                
    -230    -194    -147    -120     -52       0      80     160     240     320
     338     397     440     475
     960     958     956   955.9     954   952.4   952.7   953.5   953.6   953.7
     954     956     958     960
                                                                                
                                
BR Coef=-1 , 0 , 0 ,, 0 ,,,0.8,-1,,0,
WSPro=,,,, 1 ,,,, 0 ,,,, 0 ,,,,-1 ,-1 ,-1 , 0 , 0 , 0 , 0 , 0
Culvert=9,6,20,195,0.013,0.5,0.5,60,2,942.7,0,941.7,0,Culvert #1  , 0 ,1
Culvert Bottom n=0.035
BC Design=,, 0 ,, 0 ,,,,,,
BC Use User HTab Curves=0
BC User HTab FreeFlow(D)= 0

Type RM Length L Ch R = 1 ,14.5    ,43,43,43
BEGIN DESCRIPTION:
DS Face Aspen St.
END DESCRIPTION:
#Sta/Elev= 21
    -270     960    -240     958    -210     956    -155     954    -140     955
     -90   954.7     -40   949.5     -23     949     -15     948     -10     948
     -10   941.7      10   941.7      10     948      12     949      40     950
     120   950.1     190   950.8     225     952     255     954     273     956
     310     960
#Mann= 3 , 0 , 0
    -270     .04       0     -10    .035       0      10     .04       0
#XS Ineff= 2 , 0
       0     -10     950      10       0     950
Permanent Ineff=
       F       F
#Block Obstruct= 3 ,-1
     -80     -40     960     100     170     962     190     235     964
Bank Sta=-10,10
XS Rating Curve= 0 ,0
Exp/Cntr=0.5,0.3

Type RM Length L Ch R = 1 ,14.25   ,38,38,38
BEGIN DESCRIPTION:
31+50
END DESCRIPTION:
#Sta/Elev= 9
     -45   949.8   -11.5   948.9      -6   943.3      -4   941.3       4   941.3
       6   943.3    10.5     948    13.5   949.3      45   949.6
#Mann= 3 , 0 , 0
     -45     .04       0   -11.5    .035       0    10.5     .04       0
Bank Sta=-11.5,10.5
XS Rating Curve= 0 ,0
Exp/Cntr=0.3,0.1

Type RM Length L Ch R = 1 ,14      ,37,37,37
BEGIN DESCRIPTION:
US Face Meridan St. - 31+12
END DESCRIPTION:
#Sta/Elev= 22
    -320     960    -290     958    -250     956    -190     954    -150   953.4
   -63.4  952.38     -53  952.27   -44.8   951.9   -21.6   951.4     -10  950.16
     -10  941.12      10  941.12      10  948.18    25.7  949.67    61.1  949.87
     100   949.7     145   949.5     170     950     200     952     210   953.4
     240     954     290     960
#Mann= 3 , 0 , 0
    -320     .04       0     -10    .035       0      10     .04       0
#XS Ineff= 2 , 0
       0     -10   947.5      10       0   947.5
Permanent Ineff=
       T       T
#Block Obstruct= 3 ,-1
     -88     -50     964     100     150     960     165     205     960
Bank Sta=-10,10
XS Rating Curve= 0 ,0
Exp/Cntr=0.5,0.3

Type RM Length L Ch R = 2 ,13.5    ,,,
BEGIN DESCRIPTION:
Meridan Street
END DESCRIPTION:
Bridge Culvert--1,0,-1,-1, 0
Deck Dist Width WeirC Skew NumUp NumDn MinLoCord MaxHiCord MaxSubmerge Is_Ogee
1,35,2.6,0, 14, 14, 948.5, , 0.95, 0, 0,0,,
    -325    -286    -250    -196    -152    -131     -73       0    56.2     120
     180     203     230     280
     960     958     956     954   953.6  953.13  952.14  951.05  949.52   948.5
  950.28     952     954     960
                                                                                
                                
    -325    -286    -250    -196    -152    -131     -73       0    56.2     120
     180     203     230     280
     960     958     956     954   953.6  953.13  952.14  951.05  949.52   948.5
  950.28     952     954     960
                                                                                
                                
BR Coef=-1 , 0 , 0 ,, 0 ,,,0.8,-1,,0,
WSPro=,,,, 1 ,,,, 0 ,,,, 0 ,,,,-1 ,-1 ,-1 , 0 , 0 , 0 , 0 , 0
Culvert=9,6,20,35,0.013,0.2,1,60,2,941.12,0,940.94,0,Culvert #1  , 0 ,1
Culvert Bottom n=0.035
BC Design=,, 0 ,, 0 ,,,,,,
BC Use User HTab Curves=0
BC User HTab FreeFlow(D)= 0

Type RM Length L Ch R = 1 ,13      ,99,85,45
BEGIN DESCRIPTION:
DS Face Meridan St. - 30+75
END DESCRIPTION:
#Sta/Elev= 30
  -346.6     960  -337.1   958.9  -300.3   958.2    -271   958.1  -232.1     956
  -189.3     954   -63.5  952.35   -33.8  952.14   -17.5  951.35   -12.4  950.24
     -10  950.24     -10  940.94      10  940.94      10  950.29    13.1  950.29
      16  951.06    38.2  950.76    57.1  949.72   172.4   950.3   179.3     951
   184.3   950.8   207.1   952.4   211.7   952.3   236.5   954.1   250.5     956
   253.6   956.8   254.7     956   270.2     958   273.4   958.5   279.9     960
#Mann= 3 , 0 , 0
  -346.6     .04       0   -12.4    .035       0    13.1     .04       0
#XS Ineff= 2 , 0
       0     -10   947.5      10       0   947.5
Permanent Ineff=
       F       F
#Block Obstruct= 3 ,-1
    -110     -20     960      90     140     960     156     198     960
Bank Sta=-12.4,13.1
XS Rating Curve= 0 ,0
Exp/Cntr=0.5,0.3

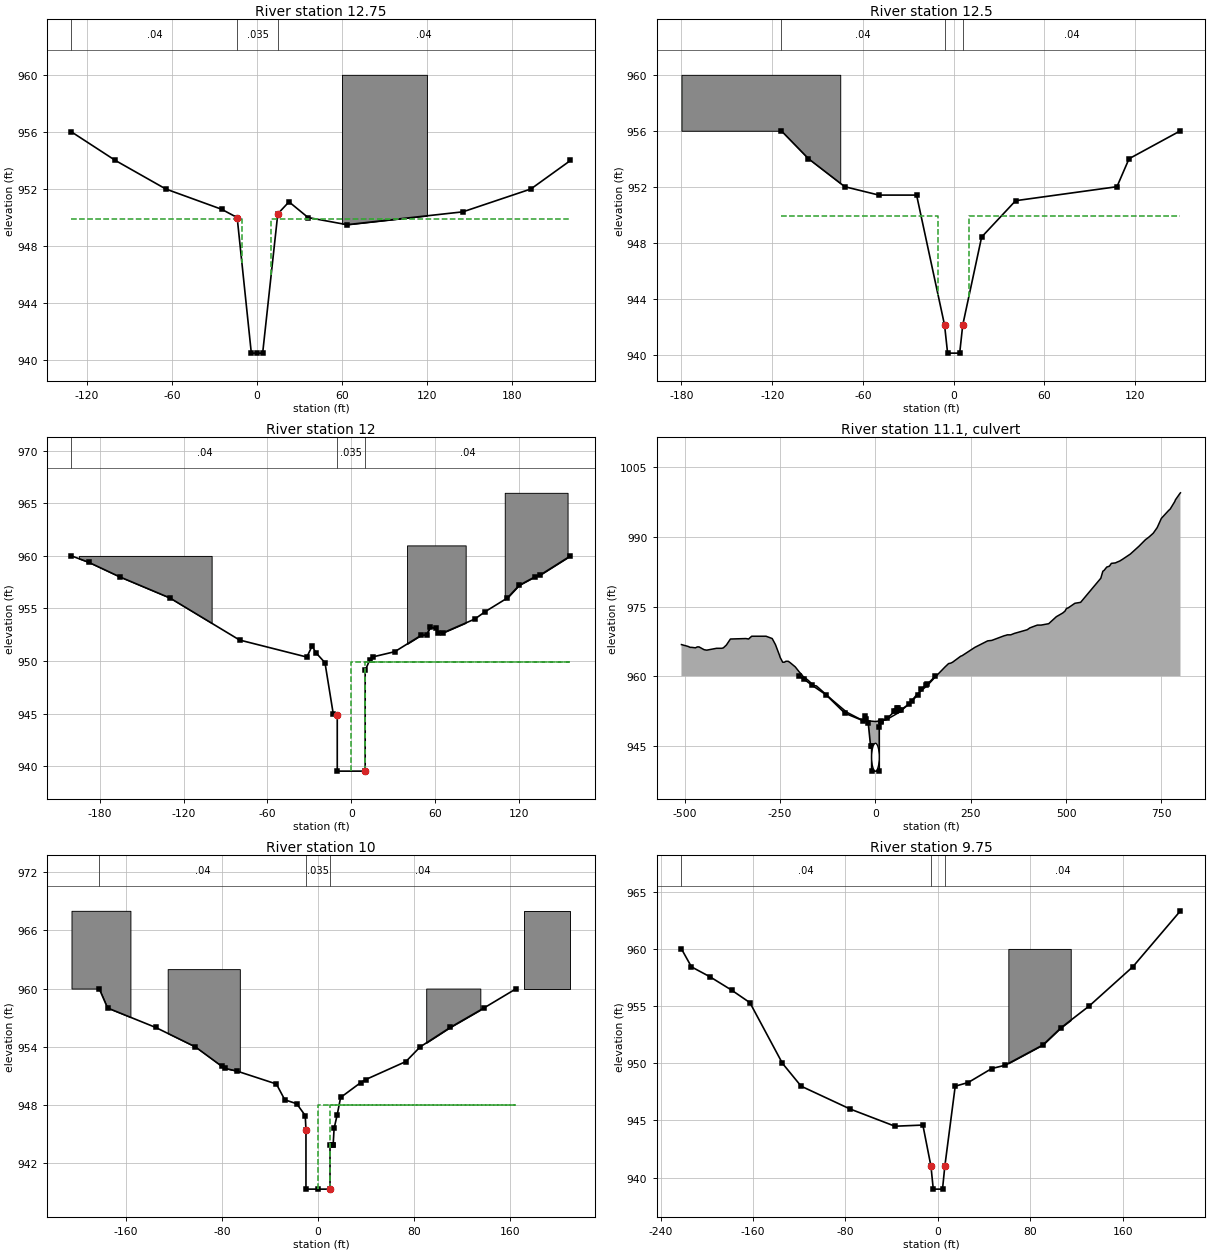
Type RM Length L Ch R = 1 ,12.75   ,100,90,80
BEGIN DESCRIPTION:
29+90
END DESCRIPTION:
#Sta/Elev= 15
    -131     956    -100     954   -64.4     952  -24.98  950.58     -14     950
      -4   940.5       0   940.5       4   940.5   14.69  950.26    22.6   951.1
    36.1     950    63.5   949.5   145.4   950.4   193.4     952   221.4     954
#Mann= 3 , 0 , 0
    -131     .04       0     -14    .035       0   14.69     .04       0
#XS Ineff= 2 , 0
        -10.6666   949.9      10           949.9
Permanent Ineff=
       F       F
#Block Obstruct= 1 ,-1
      60     120     960
Bank Sta=-14,14.69
XS Rating Curve= 0 ,0
Exp/Cntr=0.3,0.1

Type RM Length L Ch R = 1 ,12.5    ,45,70,100
BEGIN DESCRIPTION:
29+00
END DESCRIPTION:
#Sta/Elev= 14
    -114     956     -96     954     -72     952   -49.4   951.4   -24.5   951.4
      -6   942.1      -4   940.1       4   940.1       6   942.1    18.5   948.4
      41     951     108     952     116     954     150     956
#Mann= 3 , 0 , 0
    -114     .04       0      -6    .035       0       6     .04       0
#XS Ineff= 2 , 0
        -10.3333   949.9      10           949.9
Permanent Ineff=
       F       F
#Block Obstruct= 1 ,-1
    -180     -75     960
Bank Sta=-6,6
XS Rating Curve= 0 ,0
Exp/Cntr=0.3,0.1

Type RM Length L Ch R = 1 ,12      ,50,50,50
BEGIN DESCRIPTION:
US Face Martin St.
END DESCRIPTION:
#Sta/Elev= 30
  -200.4     960  -188.2   959.4  -165.7     958  -129.9     956     -80     952
   -31.8  950.38     -28  951.43   -25.4  950.81   -18.8  949.84   -12.8  944.92
     -10 944.901     -10  939.53      10  939.53      10  949.11    13.4  950.14
    15.7   950.4    31.2  950.89    49.9  952.43      54   952.5    56.7  953.23
    60.4  953.11   62.27  952.71    66.1   952.7    88.6     954      96   954.7
   111.9     956   120.3   957.2   131.5     958   135.6   958.2   157.1     960
#Mann= 3 , 0 , 0
  -200.4     .04       0     -10    .035       0      10     .04       0
#XS Ineff= 2 , 0
       0     -10   949.9      10       0   949.9
Permanent Ineff=
       T       T
#Block Obstruct= 3 ,-1
    -195    -100     960      40      82     961     110     155     966
Bank Sta=-10,10
XS Rating Curve= 0 ,0
Exp/Cntr=0.5,0.3

Type RM Length L Ch R = 2 ,11.1    ,,,
BEGIN DESCRIPTION:
Martin Street
END DESCRIPTION:
Bridge Culvert--1,0,-1,-1, 0
Deck Dist Width WeirC Skew NumUp NumDn MinLoCord MaxHiCord MaxSubmerge Is_Ogee
8,34,2.6,0, 96, 96, 950.22, , 0.95, 0, 0,0,,
  -508.8  -491.3  -485.9  -481.7  -472.1  -467.3  -462.7  -449.4  -442.5  -416.7
    -403  -398.8    -391  -380.4  -339.8  -332.8  -324.6  -304.1  -286.9  -270.8
  -262.3  -251.7  -249.7  -243.3  -238.9  -234.8  -228.8  -223.6  -210.4  -198.8
  -193.9  -190.6  -176.4  -162.3  -154.7  -113.9   -75.6   -34.2       0    27.3
    62.4      88   109.1   136.4     159   182.7   191.7   197.3   202.3   223.7
   227.2   260.7   294.3     305   337.6   342.4   345.7   350.9   354.9     364
   398.1     405   421.2   424.8   434.5   454.4   474.3   491.1     497   501.2
   505.3   523.1   538.1   591.1   596.4   599.8   606.6   613.7   618.7   629.3
   634.6   640.6   648.4   668.4   691.2   708.1   717.8   728.6   738.9   749.9
   768.9     773   784.9   786.9   798.8     800
   966.8   966.4   966.2   966.2   966.1   966.3   966.3   965.7   965.6     966
     966   966.1   966.7     968   968.1     968   968.6   968.6   968.6   968.1
   966.8   964.5     964     963     963   963.2   963.2   962.9     962   960.8
   960.4     960   959.1     958  957.89  954.91  952.25  950.48  950.22  950.55
   952.2     954   956.1     958     960     962   962.7   962.8     963   964.3
   964.4   966.2   967.6   967.7   968.7   968.8   968.9   968.9   968.9   969.2
     970   970.4   970.9     971     971   971.3   972.8   973.6     974   974.6
   974.7   975.7   975.9   981.1   982.6   982.8   983.5   983.7   984.3   984.4
   984.6   984.8   985.2   986.3     988   989.4     990   990.8     992     994
   995.7     996   997.6     998   999.4   999.5
                                                                                
                                                                                
                                                                                
                                                                                
                                                                                
                                                                                
                                                                                
                                                                                
                                                                                
                                                
  -508.8  -491.3  -485.9  -481.7  -472.1  -467.3  -462.7  -449.4  -442.5  -416.7
    -403  -398.8    -391  -380.4  -339.8  -332.8  -324.6  -304.1  -286.9  -270.8
  -262.3  -251.7  -249.7  -243.3  -238.9  -234.8  -228.8  -223.6  -210.4  -198.8
  -193.9  -190.6  -176.4  -162.3  -154.7  -113.9   -75.6   -34.2       0    27.3
    62.4      88   109.1   136.4     159   182.7   191.7   197.3   202.3   223.7
   227.2   260.7   294.3     305   337.6   342.4   345.7   350.9   354.9     364
   398.1     405   421.2   424.8   434.5   454.4   474.3   491.1     497   501.2
   505.3   523.1   538.1   591.1   596.4   599.8   606.6   613.7   618.7   629.3
   634.6   640.6   648.4   668.4   691.2   708.1   717.8   728.6   738.9   749.9
   768.9     773   784.9   786.9   798.8     800
   966.8   966.4   966.2   966.2   966.1   966.3   966.3   965.7   965.6     966
     966   966.1   966.7     968   968.1     968   968.6   968.6   968.6   968.1
   966.8   964.5     964     963     963   963.2   963.2   962.9     962   960.8
   960.4     960   959.1     958  957.89  954.91  952.25  950.48  950.22  950.55
   952.2     954   956.1     958     960     962   962.7   962.8     963   964.3
   964.4   966.2   967.6   967.7   968.7   968.8   968.9   968.9   968.9   969.2
     970   970.4   970.9     971     971   971.3   972.8   973.6     974   974.6
   974.7   975.7   975.9   981.1   982.6   982.8   983.5   983.7   984.3   984.4
   984.6   984.8   985.2   986.3     988   989.4     990   990.8     992     994
   995.7     996   997.6     998   999.4   999.5
                                                                                
                                                                                
                                                                                
                                                                                
                                                                                
                                                                                
                                                                                
                                                                                
                                                                                
                                                
BR Coef=-1 , 0 , 0 ,, 0 ,,,0.8,-1,,0,
WSPro=,,,, 1 ,,,, 0 ,,,, 0 ,,,,-1 ,-1 ,-1 , 0 , 0 , 0 , 0 , 0
Culvert=9,6,20,34,0.013,0.5,1,60,2,939.53,0,939.36,0,Culvert #1  , 0 ,16
Culvert Bottom n=0.035
BC Design=,, 0 ,, 0 ,,,,,,
BC Use User HTab Curves=0
BC User HTab FreeFlow(D)= 0

Type RM Length L Ch R = 1 ,10      ,65,60,45
BEGIN DESCRIPTION:
DS Face Martin St.
END DESCRIPTION:
#Sta/Elev= 28
    -182     960    -175     958    -135     956    -102     954     -80     952
   -77.2  951.78   -67.7  951.52   -34.6  950.18   -27.6  948.55   -17.7  948.15
   -10.6  946.93     -10 945.464     -10  939.36       0  939.36      10  939.36
      10   943.9   12.57   943.9    12.6   943.9    13.4  945.61      16  947.02
    18.8  948.79    35.5  950.32    39.6  950.63    73.1  952.49      85     954
     110     956     138     958     165     960
#Mann= 3 , 0 , 0
    -182     .04       0     -10    .035       0      10     .04       0
#XS Ineff= 2 , 0
       0     -10     948      10       0     948
Permanent Ineff=
       F       F
#Block Obstruct= 4 ,-1
    -205    -156     968    -125     -65     962      90     135     960
     171     210     968
Bank Sta=-10,10
XS Rating Curve= 0 ,0
Exp/Cntr=0.5,0.3

Type RM Length L Ch R = 1 ,9.75    ,100,90,80
BEGIN DESCRIPTION:
27+15
27+15
END DESCRIPTION:
#Sta/Elev= 23
    -222     960 -213.34  958.43 -197.43  957.57 -178.63   956.4 -162.73   955.3
  -134.6     950  -118.4     948   -75.9     946   -37.2   944.5     -13   944.6
      -6     941      -4     939       4     939       6     941      15     948
   26.24  948.32   46.57  949.54   58.18  949.83   90.98  951.61  106.39  953.09
     131  955.01  168.78  958.44     210  963.33
#Mann= 3 , 0 , 0
    -222     .04       0      -6    .035       0       6     .04       0
#Block Obstruct= 1 ,-1
      61     115     960
Bank Sta=-6,6
XS Rating Curve= 0 ,0
Exp/Cntr=0.5,0.3

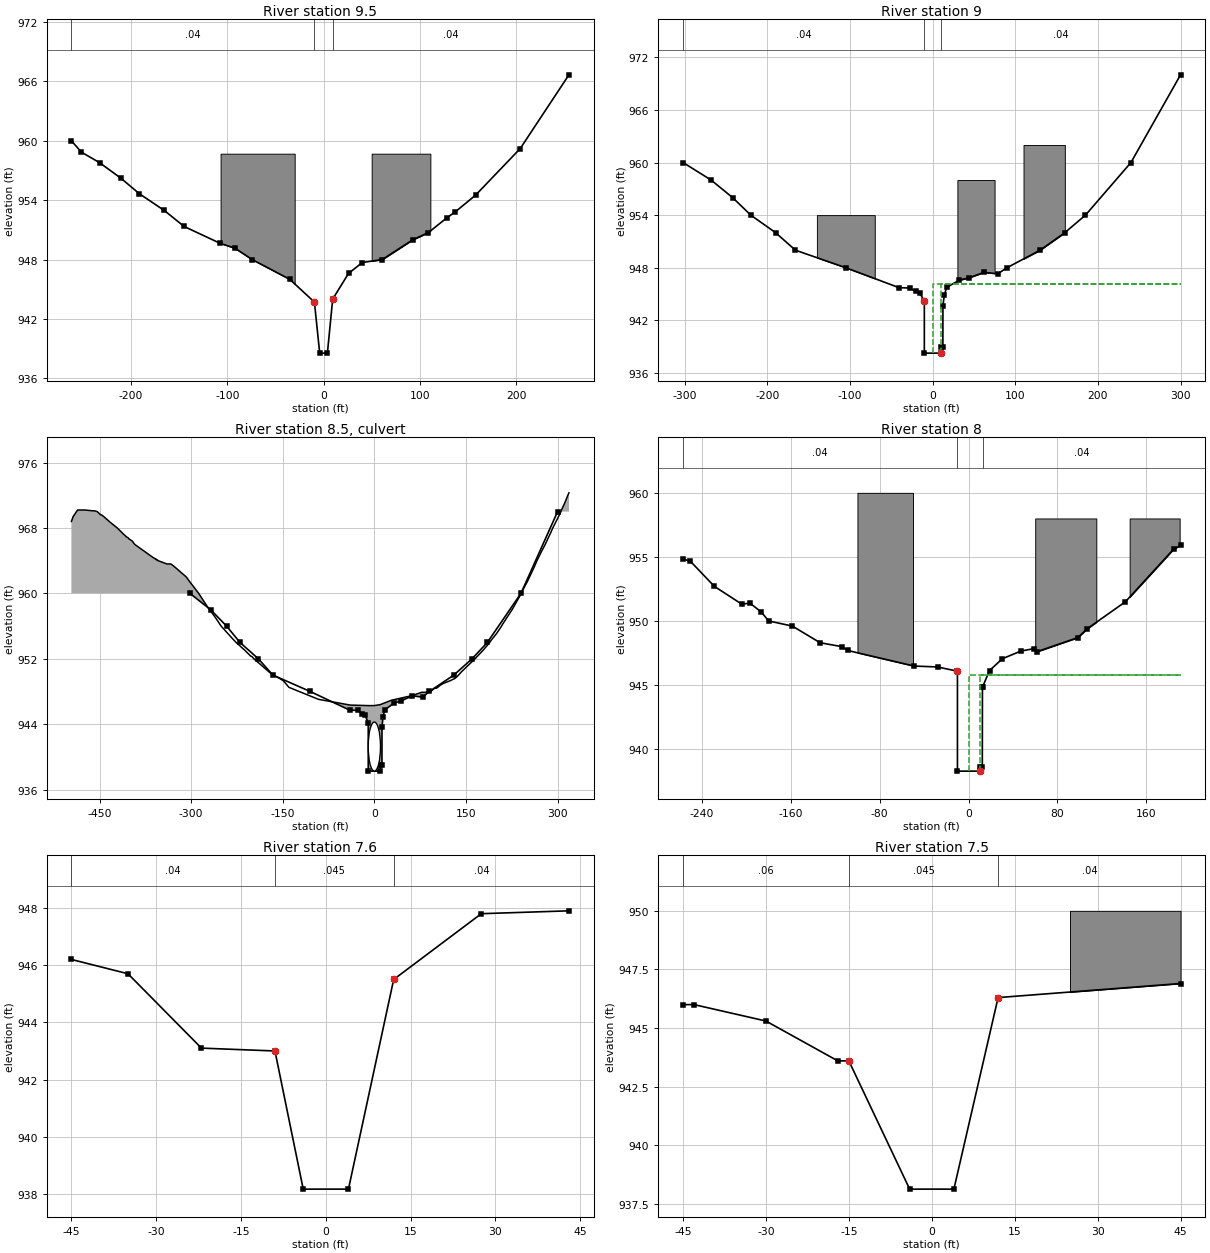
Type RM Length L Ch R = 1 ,9.5     ,36,72,124
BEGIN DESCRIPTION:
Sta. 26+25
END DESCRIPTION:
XS GIS Cut Line= 2
 1834539.0727887   424130.812355 1835045.4297949  424070.8803633
#Sta/Elev= 25
    -262     960 -251.68  958.86 -232.71  957.79 -210.32   956.2 -191.37  954.65
 -165.52  952.96 -144.85  951.34 -107.47  949.64  -92.31  949.16   -74.2     948
   -35.1     946    -9.5   943.7      -4  938.54       4  938.54     9.5     944
   25.99   946.6    40.3   947.7      61     948    92.7     950  108.87  950.72
  127.79  952.19  136.91  952.82     158  954.51  204.39  959.22     255  966.67
#Mann= 3 , 0 , 0
    -262     .04       0    -9.5    .035       0     9.5     .04       0
#Block Obstruct= 2 ,-1
    -107     -30   958.7      50     111   958.7
Bank Sta=-9.5,9.5
XS Rating Curve= 0 ,0
Exp/Cntr=0.5,0.3

Type RM Length L Ch R = 1 ,9       ,59,59,59
BEGIN DESCRIPTION:
US Face Valley Rd.
END DESCRIPTION:
#Sta/Elev= 29
    -302     960    -268     958    -242     956    -220     954    -190     952
    -166     950    -105     948   -40.7  945.73   -27.2  945.68   -20.5  945.29
   -15.4  945.11     -10 944.181     -10  938.26      10  938.26      10 938.974
   12.43  938.98    12.5  943.63    14.2  944.93    17.2  945.77    32.5  946.59
    43.6  946.84    62.1  947.47      79  947.31      90     948     130     950
     160     952     185     954     240     960     300     970
#Mann= 3 , 0 , 0
    -302     .04       0     -10    .035       0      10     .04       0
#XS Ineff= 2 , 0
       0     -10   946.1      10       0   946.1
Permanent Ineff=
       T       T
#Block Obstruct= 3 ,-1
    -140     -70     954      30      75     958     110     160     962
Bank Sta=-10,10
XS Rating Curve= 0 ,0
Exp/Cntr=0.5,0.3

Type RM Length L Ch R = 2 ,8.5     ,,,
BEGIN DESCRIPTION:
Valley Road
END DESCRIPTION:
Bridge Culvert--1,0,-1,-1, 0
Deck Dist Width WeirC Skew NumUp NumDn MinLoCord MaxHiCord MaxSubmerge Is_Ogee
1,57,2.6,0, 123, 123, 946.27, , 0.95, 0, 0,0,,
    -496  -493.2  -493.2  -493.1  -485.9  -485.4  -484.9  -481.2  -473.8  -461.3
  -458.2  -453.7  -449.3  -448.1  -446.7  -443.1  -432.5  -420.9    -410  -405.6
  -403.2  -402.2  -400.4  -398.4  -396.4  -392.5  -362.6  -360.1  -358.1  -357.5
  -357.1  -356.8  -356.2    -356  -355.2  -354.1  -339.6  -336.5  -336.3  -335.8
  -335.7  -333.2  -329.7  -326.3  -307.8    -303  -287.6  -278.9    -270  -267.6
  -258.9  -250.9  -232.7  -226.4  -212.9  -202.1  -200.7  -197.3  -184.8  -166.4
  -157.3  -148.8  -139.9   -91.5   -39.5    -7.3       0     9.4    28.3    63.2
    77.1    78.5    81.5    83.1    83.9    87.3    92.1    92.9    93.6    98.7
   100.8   101.9   102.4   103.1   103.7   105.3   106.4   113.4   123.5     132
     135   137.7   142.5   164.8   166.2   166.4   167.1   169.8   178.7   188.9
   191.6   200.2   208.3   209.7   225.4   226.2   240.6   244.3   250.2     254
   261.6   266.2   273.5   279.8   289.2   292.1   301.6   304.2   305.3   306.4
   311.9   316.8   318.6
   968.8   969.4   969.4   969.4   970.2   970.2   970.2   970.2   970.2   970.1
   970.1     970   969.7   969.6   969.6   969.4   968.7     968   967.2   966.9
   966.8   966.7   966.6   966.5   966.4     966   964.4   964.3   964.2   964.2
   964.1   964.1   964.1   964.1   964.1     964   963.6   963.6   963.6   963.6
   963.6   963.6   963.4   963.2     962   961.5     960     959     958   957.8
   956.9     956   954.5     954   953.1   952.3   952.3     952   951.2     950
   949.7   949.3  948.51  947.04  946.34  946.27  946.28  946.39  946.94  947.52
   947.9   947.9   947.9   947.9   947.9     948     948     948   948.1   948.4
   948.4   948.4   948.5   948.5   948.5   948.6   948.7     949   949.3   949.6
   949.8     950   950.4     952   952.1   952.1   952.2   952.4   953.1     954
   954.3   955.1     956   956.2     958   958.1     960   960.6   961.4     962
   963.2     964   965.1     966   967.5     968   969.4   969.8     970   970.2
   971.1     972   972.3
                                                                                
                                                                                
                                                                                
                                                                                
                                                                                
                                                                                
                                                                                
                                                                                
                                                                                
                                                                                
                                                                                
                                                                                
                        
    -496  -493.2  -493.2  -493.1  -485.9  -485.4  -484.9  -481.2  -473.8  -461.3
  -458.2  -453.7  -449.3  -448.1  -446.7  -443.1  -432.5  -420.9    -410  -405.6
  -403.2  -402.2  -400.4  -398.4  -396.4  -392.5  -362.6  -360.1  -358.1  -357.5
  -357.1  -356.8  -356.2    -356  -355.2  -354.1  -339.6  -336.5  -336.3  -335.8
  -335.7  -333.2  -329.7  -326.3  -307.8    -303  -287.6  -278.9    -270  -267.6
  -258.9  -250.9  -232.7  -226.4  -212.9  -202.1  -200.7  -197.3  -184.8  -166.4
  -157.3  -148.8  -139.9   -91.5   -39.5    -7.3       0     9.4    28.3    63.2
    77.1    78.5    81.5    83.1    83.9    87.3    92.1    92.9    93.6    98.7
   100.8   101.9   102.4   103.1   103.7   105.3   106.4   113.4   123.5     132
     135   137.7   142.5   164.8   166.2   166.4   167.1   169.8   178.7   188.9
   191.6   200.2   208.3   209.7   225.4   226.2   240.6   244.3   250.2     254
   261.6   266.2   273.5   279.8   289.2   292.1   301.6   304.2   305.3   306.4
   311.9   316.8   318.6
   968.8   969.4   969.4   969.4   970.2   970.2   970.2   970.2   970.2   970.1
   970.1     970   969.7   969.6   969.6   969.4   968.7     968   967.2   966.9
   966.8   966.7   966.6   966.5   966.4     966   964.4   964.3   964.2   964.2
   964.1   964.1   964.1   964.1   964.1     964   963.6   963.6   963.6   963.6
   963.6   963.6   963.4   963.2     962   961.5     960     959     958   957.8
   956.9     956   954.5     954   953.1   952.3   952.3     952   951.2     950
   949.7   949.3  948.51  947.04  946.34  946.27  946.28  946.39  946.94  947.52
   947.9   947.9   947.9   947.9   947.9     948     948     948   948.1   948.4
   948.4   948.4   948.5   948.5   948.5   948.6   948.7     949   949.3   949.6
   949.8     950   950.4     952   952.1   952.1   952.2   952.4   953.1     954
   954.3   955.1     956   956.2     958   958.1     960   960.6   961.4     962
   963.2     964   965.1     966   967.5     968   969.4   969.8     970   970.2
   971.1     972   972.3
                                                                                
                                                                                
                                                                                
                                                                                
                                                                                
                                                                                
                                                                                
                                                                                
                                                                                
                                                                                
                                                                                
                                                                                
                        
BR Coef=-1 , 0 , 0 ,, 0 ,,,0.8,-1,,0,
WSPro=,,,, 1 ,,,, 0 ,,,, 0 ,,,,-1 ,-1 ,-1 , 0 , 0 , 0 , 0 , 0
Culvert=9,6,20,57,0.013,0.5,1,60,1,938.26,0,938.21,0,Culvert #1  , 0 ,1
Culvert Bottom n=0.035
BC Design=,, 0 ,, 0 ,,,,,,
BC Use User HTab Curves=0
BC User HTab FreeFlow(D)= 0

Type RM Length L Ch R = 1 ,8       ,35,30,40
BEGIN DESCRIPTION:
DS Face Valley Rd.
END DESCRIPTION:
#Sta/Elev= 30
    -257   954.8  -250.8   954.7  -228.8   952.7  -203.9   951.3  -196.9   951.4
  -186.6   950.7  -179.9     950  -158.6   949.6  -133.6   948.3  -114.3     948
  -108.9   947.7   -48.9  946.48   -27.9  946.41     -10 946.079     -10  938.28
      10  938.28      10 938.615   12.38  938.61    12.5  944.85    12.6  944.85
    18.9  946.13    30.4  947.05    47.1  947.65    58.9  947.84    61.5   947.6
    98.3   948.7   106.9   949.4   141.2   951.5   184.5   955.6   190.8   955.9
#Mann= 3 ,-1 , 0
    -257     .04       0     -10    .035       0    12.6     .04       0
#XS Ineff= 2 , 0
       0     -10   945.8      10       0   945.8
Permanent Ineff=
       F       F
#Block Obstruct= 3 ,-1
    -100     -50     960      60     115     958     145     190     958
Bank Sta=-10,10
XS Rating Curve= 0 ,0
Exp/Cntr=0.5,0.3

Type RM Length L Ch R = 1 ,7.6     ,42,50,57
BEGIN DESCRIPTION:
Sta. 24+50
END DESCRIPTION:
#Sta/Elev= 9
     -45   946.2     -35   945.7     -22   943.1      -9     943      -4  938.17
       4  938.17      12   945.5    27.5   947.8      43   947.9
#Mann= 3 , 0 , 0
     -45     .04       0      -9    .045       0      12     .04       0
Bank Sta=-9,12
XS Rating Curve= 0 ,0
Exp/Cntr=0.3,0.1

Type RM Length L Ch R = 1 ,7.5     ,140,130,110
BEGIN DESCRIPTION:
Sta. 24+00
END DESCRIPTION:
#Sta/Elev= 9
     -45     946     -43     946     -30   945.3     -17   943.6     -15   943.6
      -4  938.13       4  938.13      12   946.3      45   946.9
#Mann= 3 , 0 , 0
     -45     .06       0     -15    .045       0      12     .04       0
#Block Obstruct= 1 ,-1
      25      45     950
Bank Sta=-15,12
XS Rating Curve= 0 ,0
Exp/Cntr=0.3,0.1

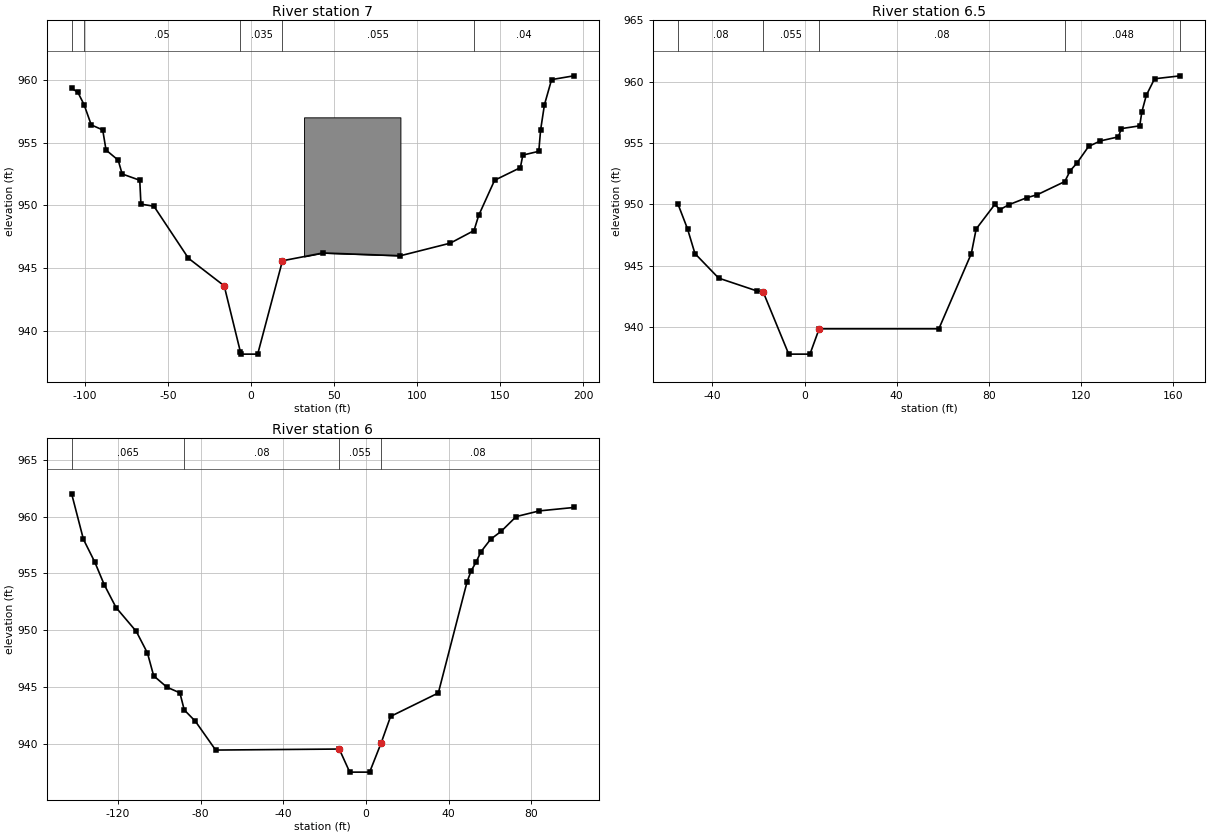
Type RM Length L Ch R = 1 ,7       ,160,162.6,160
#Sta/Elev= 30
  -107.9   959.3  -104.2     959  -100.4     958   -96.1   956.4   -89.2     956
   -87.2   954.4   -79.9   953.6   -77.5   952.5   -66.9     952   -66.2   950.1
   -58.4  949.94   -37.6   945.8  -16.08  943.61    -6.3938.3468   -5.99  938.18
    4.09  938.18      19   945.6    43.3  946.22      90     946     120     947
   134.3     948   137.1   949.2   146.7     952   162.2     953   163.7     954
   173.3   954.3   174.4     956   176.7     958     181     960   194.4   960.3
#Mann= 5 ,-1 , 0
  -107.9    .065       0  -100.4     .05       0    -6.3    .035       0
      19    .055       0   134.3     .04       0
#Block Obstruct= 1 ,-1
      32      90     957
Bank Sta=-16.08,19
XS Rating Curve= 0 ,0
Exp/Cntr=0.3,0.1

Type RM Length L Ch R = 1 ,6.5     ,210,300,310
#Sta/Elev= 29
   -54.9     950   -50.8     948   -47.6     946   -37.3     944  -20.76  942.96
  -17.99  942.88   -6.88  937.81    2.34  937.81    6.33  939.87    58.3  939.87
    72.4     946    74.5     948    82.6     950    84.8  949.57   88.61  949.97
    96.4  950.54  101.03  950.79  112.97  951.86  115.31  952.74  118.14  953.34
  123.32  954.72  128.41  955.17  136.26   955.5  137.51  956.17  145.52   956.4
  146.44  957.54  148.36  958.88  151.95  960.23  163.13  960.47
#Mann= 5 ,-1 , 0
   -54.9     .08       0  -17.99    .055       0    6.33     .08       0
  112.97    .048       0  163.13    .048       0
Bank Sta=-17.99,6.33
XS Rating Curve= 0 ,0
Exp/Cntr=0.3,0.1

Type RM Length L Ch R = 1 ,6       ,466.1,466.1,320
#Sta/Elev= 28
  -142.5     962  -136.8     958  -131.3     956  -126.7     954    -121     952
  -111.2   949.9  -105.8     948  -102.8     946   -96.4     945   -90.1   944.5
     -88     943   -82.6     942  -72.79  939.47  -12.96  939.56   -7.89  937.53
    1.75  937.53    7.25  940.06    11.9  942.43      35  944.49    48.9  954.25
    50.8   955.2    53.3     956    55.6   956.9    60.3     958    65.4   958.7
    72.7     960    83.9   960.5   100.6   960.8
#Mann= 4 ,-1 , 0
  -142.5    .065       0     -88     .08       0  -12.96    .055       0
    7.25     .08       0
Bank Sta=-12.96,7.25
XS Rating Curve= 0 ,0
Exp/Cntr=0.3,0.1