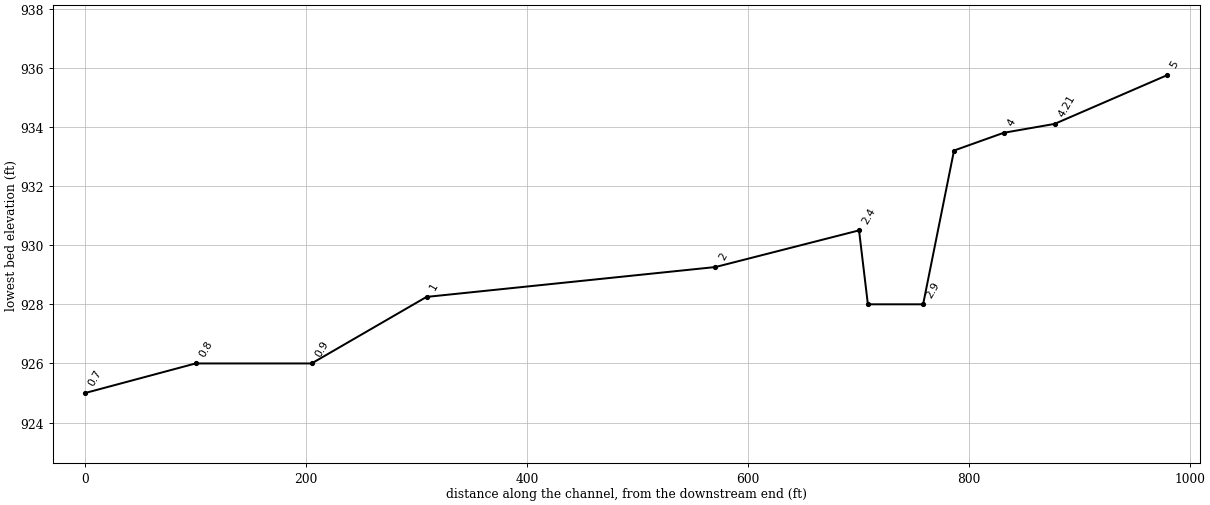
HEC-RAS study BurroughsRun.prj: Burroughs Run

--- BurroughsRun.g02 (geometry) --- (continued)

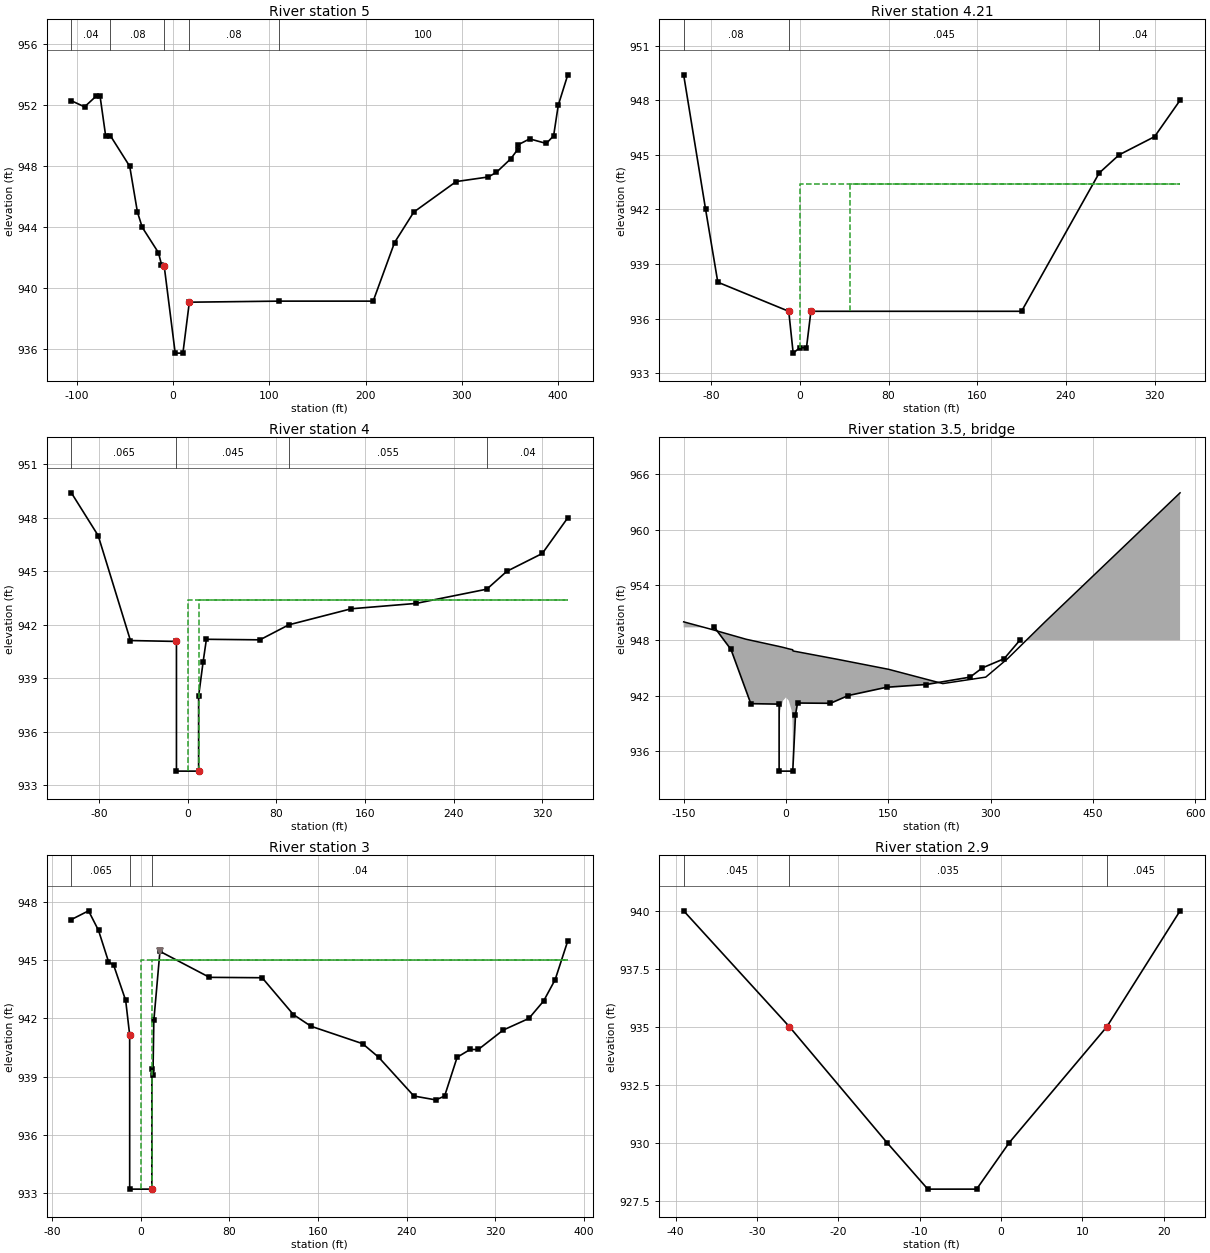
Type RM Length L Ch R = 1 ,5       ,52,102,52
#Sta/Elev= 30
  -105.6   952.3   -91.9   951.9   -79.9   952.6   -75.8   952.6     -70     950
     -65     950     -45     948     -37     945     -32     944   -15.2  942.34
     -12  941.56   -9.19  941.46    2.23  935.75   10.23  935.75   16.91  939.09
     110  939.16  207.82  939.16     230     943     250     945     294     947
   327.2   947.3   335.7   947.6   350.8   948.5   357.8   949.1     358   949.4
   370.3   949.8   387.6   949.5   395.2     950     400     952   409.9     954
#Mann= 5 ,-1 , 0
  -105.6     .04       0     -65     .08       0   -9.19     .45       0
   16.91     .08       0     110     100       0
Bank Sta=-9.19,16.91
XS Rating Curve= 0 ,0
Exp/Cntr=0.3,0.1

Type RM Length L Ch R = 1 ,4.21    ,46,46,46
#Sta/Elev= 13
  -104.8   949.4     -85     942     -74     938     -10   936.4      -6   934.1
       0   934.4       6   934.4      10   936.4     200   936.4     270     944
     288     945     320     946     343     948
#Mann= 3 ,-1 , 0
  -104.8     .08       0     -10    .045       0     270     .04       0
#XS Ineff= 2 , 0
       0     -36   943.4      45       0   943.4
Permanent Ineff=
       T       T
Bank Sta=-10,10
XS Rating Curve= 0 ,0
Exp/Cntr=0.5,0.3

Type RM Length L Ch R = 1 ,4       ,45,45,45
BEGIN DESCRIPTION:
US Face Woodland Dr.
END DESCRIPTION:
#Sta/Elev= 17
  -104.8   949.4   -80.6     947   -51.5  941.12     -10  941.07     -10   933.8
      10   933.8      10  938.01   14.02  939.91   17.01  941.19    65.3  941.16
    91.3     942   147.6   942.9     206   943.2     270     944     288     945
     320     946     343     948
#Mann= 4 ,-1 , 0
  -104.8    .065       0     -10    .045       0    91.3    .055       0
     270     .04       0
#XS Ineff= 2 , 0
       0     -10   943.4      10       0   943.4
Permanent Ineff=
       T       T
Bank Sta=-10,10
XS Rating Curve= 0 ,0
Exp/Cntr=0.5,0.3

Type RM Length L Ch R = 3 ,3.5     ,,,
BEGIN DESCRIPTION:
Woodland Drive
END DESCRIPTION:
Bridge Culvert--1,0,-1,-1, 0
Deck Dist Width WeirC Skew NumUp NumDn MinLoCord MaxHiCord MaxSubmerge Is_Ogee
1,43,2.6,0, 21, 21, 943.3, , 0.95, 0, 0,0,,
    -150    -110   -58.3     -10   -9.99   -9.52   -8.23   -4.17       0    4.17
    8.23    9.52    9.99    10.4    75.9   150.5     230     293     325     380
     578
     950   949.2  948.11  947.33  947.33  947.32   947.3  947.23  947.15  947.07
     947  946.98  946.97  946.84  945.93  944.85   943.3     944     946     950
     964
                           933.8  937.92   939.3  940.41  941.45   941.8  941.45
  940.41   939.3  937.92
        
    -150    -110   -58.3     -10   -9.99   -9.52   -8.23   -4.17       0    4.17
    8.23    9.52    9.99    10.4    75.9   150.5     230     293     325     380
     578
     950   949.2  948.11  947.33  947.33  947.32   947.3  947.23  947.15  947.07
     947  946.98  946.97  946.84  945.93  944.85   943.3     944     946     950
     964
                           933.2  937.32   938.7  939.81  940.85   941.2  940.85
  939.81   938.7  937.32
        
BR Coef=-1 , 0 , 0 ,, 0 ,,,0.8,0,,1,941.2
WSPro=,,,, 1 ,,,, 0 ,,,, 0 ,,,,-1 ,-1 ,-1 , 0 , 0 , 0 , 0 , 0
BR U #Sta/Elev= 16
  -104.8   949.4   -80.6     947   -51.5  941.12     -10  941.07     -10   933.8
      10   933.8   14.02  939.91   17.01  941.19    65.3  941.16    91.3     942
   147.6   942.9     206   943.2     270     944     288     945     320     946
     343     948
BR U #Mann= 4
  -104.8    .065     -10    .035      10    .045     270     .04
BR D #Sta/Elev= 54
   -62.6   947.1   -57.3  947.37   -47.1  947.55   -38.1  946.54   -29.1  944.93
   -24.4  944.74   -13.6  942.93     -10  941.15     -10   933.2      10   933.2
   10.03 939.391      11  939.07    11.8   941.9    17.3  945.46      62  944.12
   106.3   944.1   109.5   944.1   114.3   943.8   115.1   943.7   116.3   943.7
   131.8   942.5   137.7   942.2     139   942.2   147.9   941.8   148.6   941.8
   153.5   941.6   200.1   940.7   204.8   940.4   206.5   940.4   213.6     940
   214.6     940   242.9   938.3   243.7   938.2   246.4     938   266.2   937.8
   274.1     938   280.2   939.2   285.4     940   297.1   940.4   301.1   940.4
   302.2   940.5   302.8   940.4   304.5   940.4   305.4   940.5   326.9   941.4
   335.6   941.6   336.7   941.7   339.7   941.7   340.8   941.8   350.1     942
   351.5   942.1   363.4   942.9   373.8     944   385.2     946
BR D #Mann= 3
   -62.6    .065     -10    .035      10    .045
BR D Banks=,10
BC Design=,, 0 ,, 0 ,,,,,,
BC Use User HTab Curves=0
BC User HTab FreeFlow(D)= 0

Type RM Length L Ch R = 1 ,3       ,27.96,27.96,27.96
BEGIN DESCRIPTION:
DS Face Woodland Dr.
END DESCRIPTION:
#Sta/Elev= 30
   -62.6   947.1   -47.1  947.55   -38.1  946.54   -29.1  944.93   -24.4  944.74
   -13.6  942.93     -10  941.15   -9.99   933.2      10   933.2   10.03 939.391
      11  939.07    11.8   941.9    17.3  945.46      62  944.12   109.5   944.1
   137.7   942.2   153.5   941.6   200.1   940.7   214.6     940   246.4     938
   266.2   937.8   274.1     938   285.4     940   297.1   940.4   304.5   940.4
   326.9   941.4   350.1     942   363.4   942.9   373.8     944   385.2     946
#Mann= 3 ,-1 , 0
   -62.6    .065       0     -10    .035       0      10     .04       0
Levee=0,,,-1,17.3,945.46,,
#XS Ineff= 2 , 0
       0     -10     945      10       0     945
Permanent Ineff=
       F       F
Bank Sta=-10,10
XS Rating Curve= 0 ,0
Exp/Cntr=0.5,0.3

Type RM Length L Ch R = 1 ,2.9     ,60,50,40
BEGIN DESCRIPTION:
Bottom of Dissipator
END DESCRIPTION:
#Sta/Elev= 8
     -39     940     -26     935     -14     930      -9     928      -3     928
       1     930      13     935      22     940
#Mann= 3 ,-1 , 0
     -39    .045       0     -26    .035       0      13    .045       0
Bank Sta=-26,13
XS Rating Curve= 0 ,0
Exp/Cntr=0.5,0.3

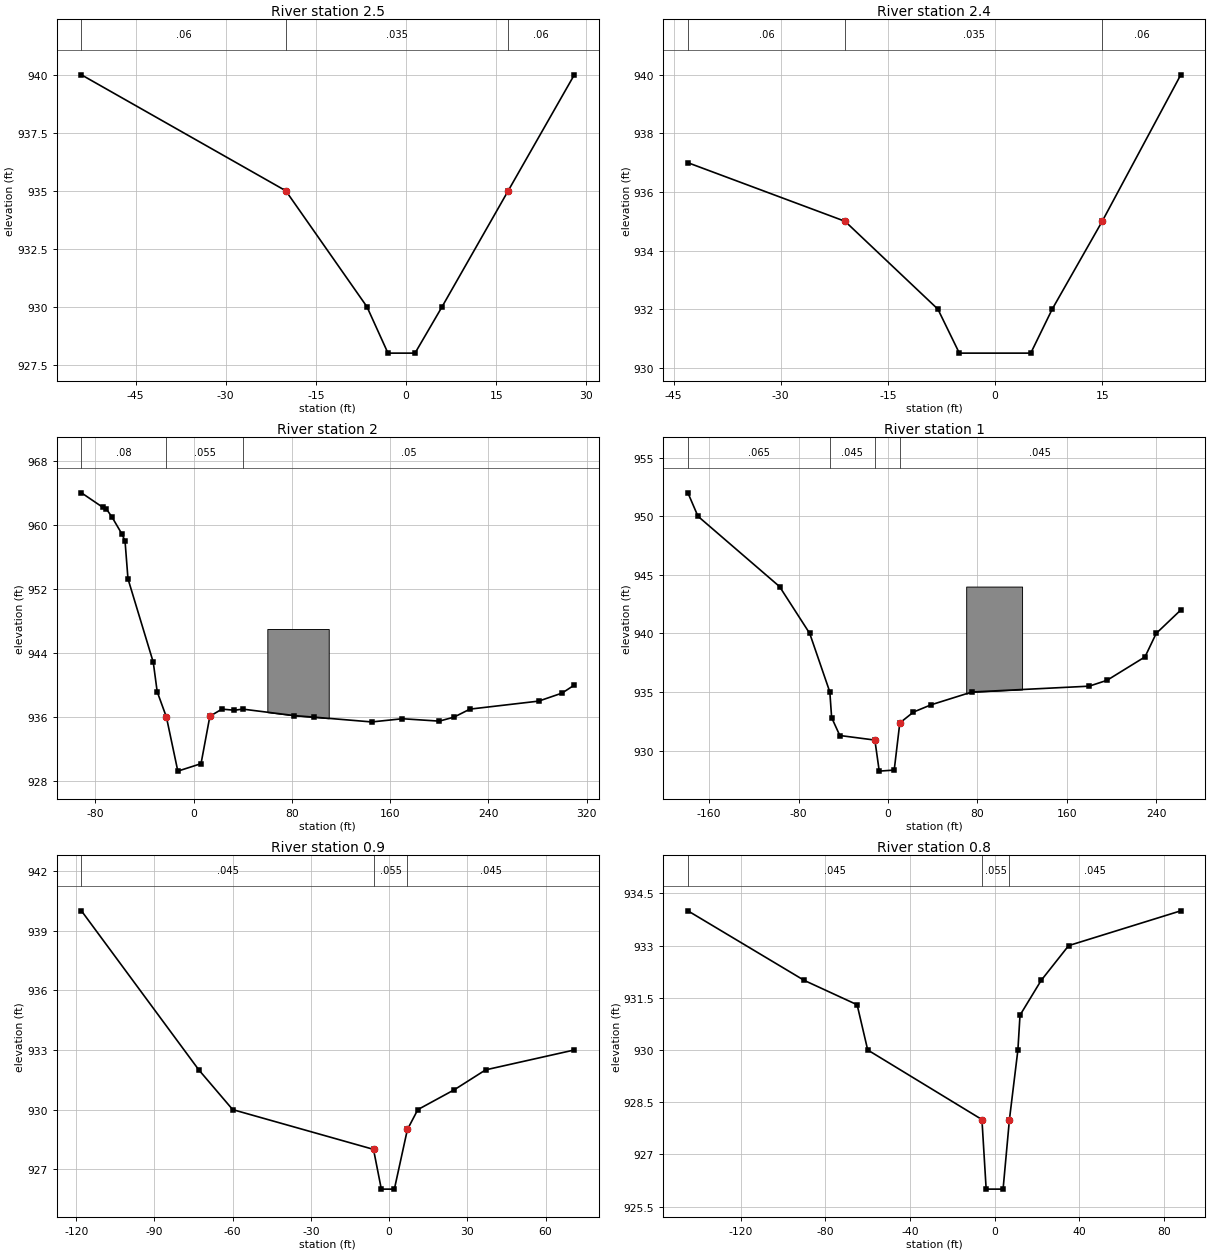
Type RM Length L Ch R = 1 ,2.5     ,8,8,8
BEGIN DESCRIPTION:
Bottom of Dissipator
END DESCRIPTION:
#Sta/Elev= 8
     -54     940     -20     935    -6.5     930      -3     928     1.5     928
       6     930      17     935      28     940
#Mann= 3 , 0 , 0
     -54     .06       0     -20    .035       0      17     .06       0
Bank Sta=-20,17
XS Rating Curve= 0 ,0
Exp/Cntr=0.3,0.1

Type RM Length L Ch R = 1 ,2.4     ,192,130.02,27
BEGIN DESCRIPTION:
Top of Dissipator
END DESCRIPTION:
#Sta/Elev= 8
     -43     937     -21     935      -8     932      -5   930.5       5   930.5
       8     932      15     935      26     940
#Mann= 3 , 0 , 0
     -43     .06       0     -21    .035       0      15     .06       0
Bank Sta=-21,15
XS Rating Curve= 0 ,0
Exp/Cntr=0.3,0.1

Type RM Length L Ch R = 1 ,2       ,290,261.5,70
#Sta/Elev= 26
   -91.4     964   -74.1   962.2   -71.2     962   -66.6     961   -58.6   958.9
   -55.9     958   -53.5  953.27   -32.9  942.85   -29.7  939.17   -22.2  936.01
   -12.9  929.26       6  930.19    13.2  936.11      23     937    33.2  936.86
      40     937    82.1  936.19      98     936     145   935.4     170   935.8
     200   935.5     212     936     225     937     281     938     300     939
     310     940
#Mann= 3 ,-1 , 0
   -91.4     .08       0   -22.2    .055       0      40     .05       0
#Block Obstruct= 1 ,-1
      60     110     947
Bank Sta=-22.2,13.2
XS Rating Curve= 0 ,0
Exp/Cntr=0.3,0.1

Type RM Length L Ch R = 1 ,1       ,75,104,112
#Sta/Elev= 19
    -179     952    -170     950     -97     944     -70     940     -52     935
   -50.4  932.82   -43.1  931.29   -11.7   930.9    -7.8  928.25     5.6  928.34
    10.6  932.36    22.8  933.29    38.6  933.91      75     935     180   935.5
     196     936     230     938     240     940     262     942
#Mann= 4 ,-1 , 0
    -179    .065       0     -52    .045       0   -11.7    .055       0
    10.6    .045       0
#Block Obstruct= 1 ,-1
      70     120     944
Bank Sta=-11.7,10.6
XS Rating Curve= 0 ,0
Exp/Cntr=0.3,0.1

Type RM Length L Ch R = 1 ,0.9     ,92,105,107
#Sta/Elev= 11
    -118     940     -73     932     -60     930      -6     928      -3     926
       2     926       7     929      11     930      25     931      37     932
      71     933
#Mann= 3 , 0 , 0
    -118    .045       0      -6    .055       0       7    .045       0
Bank Sta=-6,7
XS Rating Curve= 0 ,0
Exp/Cntr=0.3,0.1

Type RM Length L Ch R = 1 ,0.8     ,72,100,135
#Sta/Elev= 13
    -145     934     -90     932     -65   931.3     -60     930      -6     928
      -4     926       4     926       7     928      11     930      12     931
      22     932      35     933      88     934
#Mann= 3 , 0 , 0
    -145    .045       0      -6    .055       0       7    .045       0
Bank Sta=-6,7
XS Rating Curve= 0 ,0
Exp/Cntr=0.3,0.1

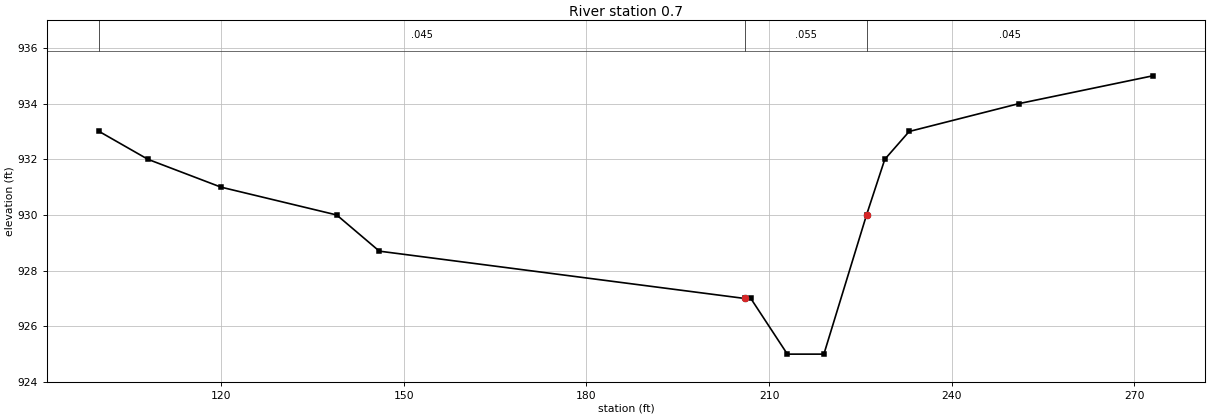
Type RM Length L Ch R = 1 ,0.7     ,1,1,1
#Sta/Elev= 14
     100     933     108     932     120     931     139     930     146   928.7
     206     927     207     927     213     925     219     925     226     930
     229     932     233     933     251     934     273     935
#Mann= 3 , 0 , 0
     100    .045       0     206    .055       0     226    .045       0
Bank Sta=206,226
XS Rating Curve= 0 ,0
Exp/Cntr=0.3,0.1