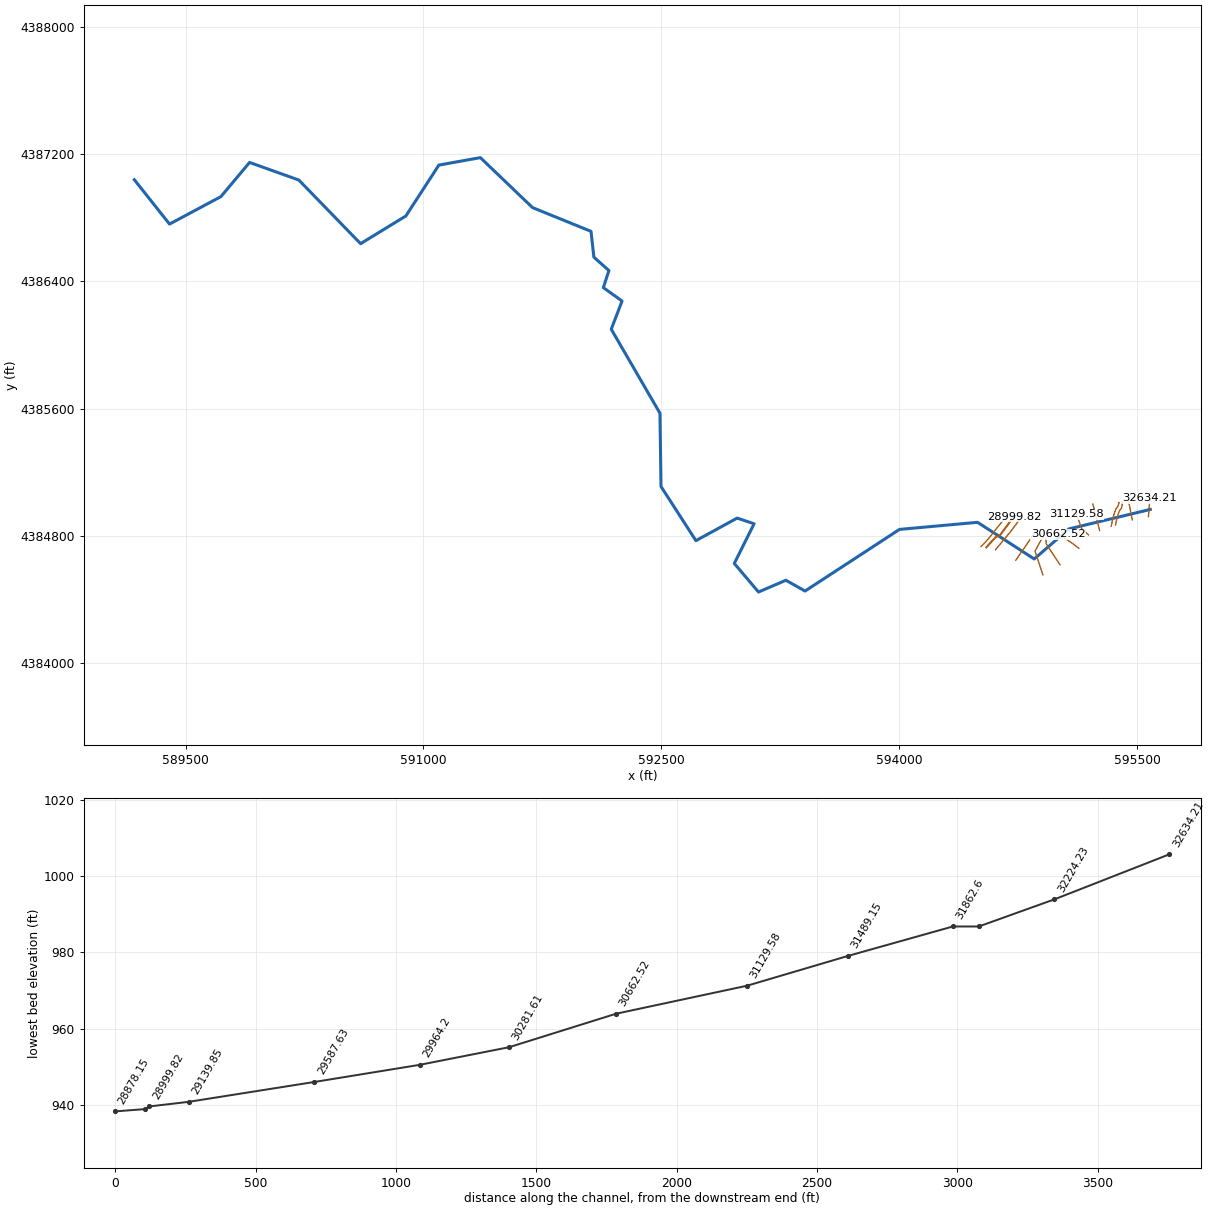
--- Deckers_Creek_Detail_Study.prj (project) ---

Proj Title=Deckers_Creek_Detail_Study
Current Plan=p01
Default Exp/Contr=0.3,0.1
English Units
Geom File=g01
Flow File=f01
Flow File=f03
Flow File=f04
Plan File=p01
Plan File=p04
Plan File=p05
Y Axis Title=Elevation
X Axis Title(PF)=Main Channel Distance
X Axis Title(XS)=Station
BEGIN DESCRIPTION:
Detailed Study for Deckers Creek
Upper Monongahela Watershed, Monongalia County, WV
Submitted by RAMPP for FEMA Region III
Model date: January 2016
HEC-RAS version 4.1.0
Vertical Datum: NAVD88 (feet)
Horizontal Datum: NAD_1983_UTM_Zone_17N
Model calibrated using rating curve for USGS gage 03062500
END DESCRIPTION:
DSS Export Rating Curves= 0
DSS Export Rating Curve Sorted= 0
DSS Export Volume Flow Curves= 0
DXF Filename=..\..\..\..\..\..\DETAILED\Basin_HUC_Stream\HEC-RAS\Deckers Creek\Model\Deckers_Creek.
DXF OffsetX= 0
DXF OffsetY= 0
DXF ScaleX= 1
DXF ScaleY= 10

--- Deckers_Creek_Detail_Study.p01 (plan) ---

Plan Title=Deckers_Creek_Mutiprofile_Run
Program Version=4.10
Short Identifier=Multi-profile
Geom File=g01
Flow File=f01
Subcritical Flow
K Sum by GR= 0
Std Step Tol= 0.01
Critical Tol= 0.01
Num of Std Step Trials= 20
Max Error Tol= 0.3
Flow Tol Ratio= 0.001
Split Flow NTrial= 30
Split Flow Tol= 0.02
Split Flow Ratio= 0.02
Log Output Level= 0
Friction Slope Method= 1
Unsteady Friction Slope Method= 2
Unsteady Bridges Friction Slope Method= 1
Parabolic Critical Depth
Global Vel Dist= 0 , 0 , 0
Global Log Level= 0
CheckData=True
Encroach Param=-1 ,0,0, 0
Computation Interval=1HOUR
Output Interval=1HOUR
Run HTab= 0
Run UNet= 0
Run PostProcess= 0
Run WQNet= 0
UNET Theta= 1
UNET Theta Warmup= 1
UNET ZTol= 0.02
UNET ZSATol= 0.05
UNET MxIter= 20
UNET MaxInSteps= 0
UNET DtIC= 0
UNET DtMin= 0
UNET MaxCRTS= 20
UNET WFStab= 2
UNET SFStab= 1
UNET WFX= 1
UNET SFX= 1
UNET DSS MLevel= 4
UNET DZMax Abort= 98.43
UNET Convert EG Bridges= 0
UNET Use Existing IB Tables=-1
UNET Froude Reduction=False
UNET Froude Limit= 1
UNET Froude Power= 10
UNET Time Slicing=0,0, 5
UNET Junction Losses=0
Instantaneous Interval=1HOUR
Write IC File= 0
Write IC File at Sim End=0
Echo Input=False
Echo Parameters=False
Echo Output=False
Write Detailed= 0
WQ AD Non Conservative
WQ ULTIMATE=-1
WQ Max Comp Step=1HOUR
WQ Output Interval=15MIN
WQ Output Selected Increments= 0
WQ Output face flow=0
WQ Output face velocity=0
WQ Output face area=0
WQ Output face dispersion=0
WQ Output cell volume=0
WQ Output cell surface area=0
WQ Output cell continuity=0
WQ Output cumulative cell continuity=0
WQ Output face conc=0
WQ Output face dconc_dx=0
WQ Output face courant=0
WQ Output face peclet=0
WQ Output face adv mass=0
WQ Output face disp mass=0
WQ Output cell mass=0
WQ Output cell source sink temp=0
WQ Output cell source sink nsm=0
WQ Output MaxMinRange=-1
WQ Daily Max Min Mean=-1
WQ Daily Range=0
WQ Daily Time=0
WQ Create Restart=0
WQ Fixed Restart=0
WQ System Summary=0
WQ Use Fixed Temperature=0
Sorting and Armoring Iterations= 10
XS Update Threshold= 0.02
Hydraulics Update Threshold= 0.02
Energy Slope Method= 1
Volume Change Method= 0
XS Weighting Method= 0
Number of US Weighted Cross Sections= 1
Number of DS Weighted Cross Sections= 1
Upstream XS Weight=0.25
Main XS Weight=0.5
Downstream XS Weight=0.25
Number of DS XS's Weighted with US Boundary= 1
Upstream Boundary Weight= 1
Weight of XSs Associated with US Boundary= 0
Number of US XS's Weighted with DS Boundary= 1
Downstream Boundary Weight= 0.5
Weight of XSs Associated with DS Boundary= 0.5
Sediment Output Level= 4
Mass or Volume Output= 0
Output Increment Type= 1
Profile and TS Output Increment= 10
XS Output Flag= 0
XS Output Increment= 10
Disregard all LS=0
Disregard all Conn=0
Disregard all Breaches=0
Disregard all Pumps=0

--- Deckers_Creek_Detail_Study.p04 (plan) ---

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Plan Title=Calibration Run
Short Identifier=Calib
Geom File=g01
Flow File=f03

--- Deckers_Creek_Detail_Study.p05 (plan) ---

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Plan Title=Deckers_Creek_Floodway_Run
Short Identifier=Floodway
Geom File=g01
Flow File=f04
Encroach Param=-1 ,0,0, 2
Encroach River=Deckers_Creek
Encroach Reach=1
Encroach Node=32634.21
       1  -30.38   22.57
Encroach Node=32224.23
       1  -40.26    14.9
Encroach Node=31954.88
       1  -46.99    47.1
Encroach Node=31862.6
       1  -34.96   28.57
Encroach Node=31489.15
       1  -22.24   34.09
Encroach Node=31129.58
       1  -41.88   48.33
Encroach Node=30662.52
       1  -25.16   23.36
Encroach Node=30281.61
       1  -31.91      31
Encroach Node=29964.2
       1  -73.09   23.58
Encroach Node=29587.63
       1  -22.62   28.75
Encroach Node=29139.85
       1  -19.78   22.87
Encroach Node=28999.82
       1  -90.57   30.08
Encroach Node=28984.87
       1 -105.77   24.74
Encroach Node=28878.15
       1 -215.05    34.9
Encroach Node=28812.39
       1 -290.11   30.67
Encroach Node=28507.4
       1 -361.23   35.05
Encroach Node=28151.15
       1 -223.22   75.22
Encroach Node=27768.36
       1  -73.64  106.05
Encroach Node=27338.08
       1   -59.4   49.17
Encroach Node=27023.72
       1  -51.35   30.18
Encroach Node=26492.81
       1  -68.16   50.45
Encroach Node=26009.77
       1 -104.72   40.48
Encroach Node=25587.14
       1     -94   50.58
Encroach Node=25164.04
       1 -140.98   53.51
Encroach Node=24704.62
       1   -38.7  112.52
Encroach Node=24391.41
       1  -20.87  197.42
Encroach Node=24107.35
       1  -36.25   52.31
Encroach Node=23778.37
       1  -41.32   21.21
Encroach Node=23329.29
       1  -22.93  110.23
Encroach Node=22930.34
       1  -31.09  123.71
Encroach Node=22456.16
       1  -32.08  116.26
Encroach Node=22004.35
       1  -30.42  113.31
Encroach Node=21611.34
       1 -132.25   21.06
Encroach Node=21099.53
       1  -56.32   28.96
Encroach Node=20693.49
       1   -63.6   40.55
Encroach Node=20450.61
       1   -41.8      68
Encroach Node=20355.27
       1   -41.8      70
Encroach Node=19902.23
       1  -36.03   28.92
Encroach Node=19640.56
       1  -45.74   30.51
Encroach Node=19192.91
       1  -47.66   31.93
Encroach Node=18766.4
       1  -25.26   34.84
Encroach Node=18557.19
       1  -43.92   47.87
Encroach Node=18345.87
       1  -28.25   36.52
Encroach Node=18045.25
       1  -29.79    33.1
Encroach Node=17765.29
       1  -27.69   22.47
Encroach Node=17486.88
       1  -25.95   26.64
Encroach Node=16968.09
       1   -19.9   33.68
Encroach Node=16549.47
       1  -62.21   35.05
Encroach Node=16094.65
       1  -85.26   35.38
Encroach Node=15827.13
       1   -35.9   57.38
Encroach Node=15755.6
       1  -37.76    47.1
Encroach Node=15354.33
       1   -53.4  140.92
Encroach Node=14980.86
       1  -38.25  173.16
Encroach Node=14501.31
       1    -175   60.68
Encroach Node=14335
       1 -125.69   80.65
Encroach Node=14266.69
       1    -125   92.46
Encroach Node=13828.97
       1  -52.82  102.96
Encroach Node=13485.22
       1 -133.72   47.96
Encroach Node=13149.25
       1  -13.75  155.49
Encroach Node=12610
       1 -158.18   22.11
Encroach Node=12017.29
       1  -21.23  266.34
Encroach Node=11820.24
       1  -47.43  209.57
Encroach Node=11807.11
       1  -50.71   207.3
Encroach Node=11687.36
       1  -41.37   159.4
Encroach Node=11587.01
       1     -35  181.84
Encroach Node=10935.1
       1 -105.48   73.21
Encroach Node=10712.01
       1 -133.17   55.35
Encroach Node=10346.77
       1  -25.46  123.73
Encroach Node=10109.68
       1  -66.77  104.61
Encroach Node=10017.43
       1  -92.27   95.66
Encroach Node=9548.69
       1   -58.3    71.6
Encroach Node=9078.49
       1  -77.64   71.85
Encroach Node=8556.13
       1  -69.44   49.54
Encroach Node=8430.79
       1   -72.6    58.4
Encroach Node=8365.01
       1  -64.26   55.34
Encroach Node=8103.67
       1   -55.2   48.65
Encroach Node=7701.83
       1  -51.61    54.5
Encroach Node=7156.21
       1  -54.47   62.33
Encroach Node=6834.83
       1  -43.33   57.42
Encroach Node=6664.79
       1  -48.28   46.74
Encroach Node=6469.790
       1  -56.97   48.11
Encroach Node=6456.440
       1  -52.22   50.83
Encroach Node=6404.83
       1  -45.37   54.46
Encroach Node=6357.02
       1  -21.49   28.37
Encroach Node=6224.39
       1  -55.38   48.29
Encroach Node=6060.97
       1  -56.15   55.39
Encroach Node=5788.79
       1  -32.09   41.03
Encroach Node=5520.79
       1  -21.93   31.85
Encroach Node=5189.62
       1     -46   37.29
Encroach Node=4785.26
       1  -28.41   52.32
Encroach Node=4281.1
       1  -24.93   25.66
Encroach Node=3838.58
       1  -27.07   30.51
Encroach Node=3541.66
       1  -19.32   38.98
Encroach Node=3299.573
       1  -32.45    42.6
Encroach Node=3281.026
       1   -32.8   40.09
Encroach Node=3081.75
       1  -31.13   35.71
Encroach Node=2915.59
       1  -34.78   47.14
Encroach Node=2808.03
       1  -41.24   32.86
Encroach Node=2531.33
       1  -28.02   28.11
Encroach Node=2281.79
       1  -34.27   25.71
Encroach Node=2203.6
       1  -29.36   30.61
Encroach Node=1951.26
       1   -18.9   32.51
Encroach Node=1706.04
       1  -25.89   24.67
Encroach Node=1279.53
       1  -37.63   30.38
Encroach Node=1036.52
       1  -38.65   17.68
Encroach Node=956.57
       1  -31.72   21.95
Encroach Node=664.95
       1  -38.11   30.72
Encroach Node=485.02
       1  -43.04   33.89
Encroach Node=278.93
       1  -35.53    41.4
Encroach Node=95.51
       1  -54.13   44.03
Encroach Node=40.39
       1  -68.15   55.01
Encroach Node=20.32
       1   -52.1   52.29

--- Deckers_Creek_Detail_Study.f01 (steady flow) ---

Flow Title=Deckers_Creek_Mutiprofile_Run
Program Version=4.10
Number of Profiles= 6
Profile Names=10PCT,4PCT,2PCT,1PCT,1PCT_PLUS,0.2PCT
River Rch & RM=Deckers_Creek,1               ,32634.21
    2919    4041    5004    6055    8023    9030
River Rch & RM=Deckers_Creek,1               ,31129.58
    2923    4046    5011    6063    8033    9041
River Rch & RM=Deckers_Creek,1               ,30281.61
    2946    4078    5049    6109    8094    9108
River Rch & RM=Deckers_Creek,1               ,29587.63
    3032    4195    5193    6282    8324    9359
River Rch & RM=Deckers_Creek,1               ,28151.15
    3038    4203    5203    6295    8341    9377
River Rch & RM=Deckers_Creek,1               ,26492.81
    3048    4216    5218    6314    8366    9404
River Rch & RM=Deckers_Creek,1               ,24704.62
    3064    4239    5246    6347    8410    9453
River Rch & RM=Deckers_Creek,1               ,19640.56
    3069    4246    5255    6357    8423    9468
River Rch & RM=Deckers_Creek,1               ,18766.4
    3120    4315    5339    6459    8558    9615
River Rch & RM=Deckers_Creek,1               ,17765.29
    3138    4340    5369    6496    8607    9669
River Rch & RM=Deckers_Creek,1               ,15354.33
    3143    4346    5377    6506    8620    9682
River Rch & RM=Deckers_Creek,1               ,13828.97
    3144    4347    5378    6507    8622    9684
River Rch & RM=Deckers_Creek,1               ,13485.22
    3227    4461    5517    6675    8844    9926
River Rch & RM=Deckers_Creek,1               ,10935.1
    3535    4880    6028    7293    9663   10818
River Rch & RM=Deckers_Creek,1               ,9078.49
    3584    4948    6110    7392    9794   10961
River Rch & RM=Deckers_Creek,1               ,7701.83
    3594    4961    6126    7411    9820   10989
River Rch & RM=Deckers_Creek,1               ,5788.79
    3601    4970    6137    7425    9838   11009
River Rch & RM=Deckers_Creek,1               ,5189.62
    3612    4985    6155    7447    9867   11040
River Rch & RM=Deckers_Creek,1               ,3081.75
    3613    4986    6157    7449    9870   11043
River Rch & RM=Deckers_Creek,1               ,2531.33
    3621    4997    6169    7463    9888   11061
River Rch & RM=Deckers_Creek,1               ,1706.04
    3628    5005    6179    7474    9903   11075
River Rch & RM=Deckers_Creek,1               ,664.95
    3629    5006    6180    7475    9905   11077
River Rch & RM=Deckers_Creek,1               ,95.51
    3633    5011    6185    7481    9913   11084
Boundary for River Rch & Prof#=Deckers_Creek,1               , 1
Up Type= 0
Dn Type= 3
Dn Slope=0.0048
Boundary for River Rch & Prof#=Deckers_Creek,1               , 2
Up Type= 0
Dn Type= 3
Dn Slope=0.0048
Boundary for River Rch & Prof#=Deckers_Creek,1               , 3
Up Type= 0
Dn Type= 3
Dn Slope=0.0048
Boundary for River Rch & Prof#=Deckers_Creek,1               , 4
Up Type= 0
Dn Type= 3
Dn Slope=0.0048
Boundary for River Rch & Prof#=Deckers_Creek,1               , 5
Up Type= 0
Dn Type= 3
Dn Slope=0.0048
Boundary for River Rch & Prof#=Deckers_Creek,1               , 6
Up Type= 0
Dn Type= 3
Dn Slope=0.0048
Observed RC=Gage03062500,Deckers_Creek   ,1               ,3541.66 ,0
Observed RC Data= 96
  804.81     .01  806.26     167  807.46     628  808.56    1240   809.3    1710
  809.97    2160  810.89    2750  811.27    3000  811.39    3080  811.47    3140
  811.51    3160  811.72    3310  811.82    3370  811.91    3440  811.95    3460
  812.24    3660  812.28    3680   812.4    3770  812.53    3850  812.62    3920
  812.69    3960  812.78    4030  812.82    4050  812.91    4120  812.95    4140
  813.07    4230  813.17    4290   813.2    4320   813.3    4380  813.33    4410
   813.4    4450  813.53    4550   813.6    4590   813.7    4670  813.77    4710
  813.87    4790  813.98    4860  814.13    4980  814.17    5000  814.36    5150
  814.37    5150  814.48    5240  814.53    5270   814.6    5330  814.65    5360
  814.77    5460  814.82    5490  814.98    5620  815.03    5650  815.17    5770
  815.22    5800  815.42    5960  815.72    6210  815.78    6250  815.93    6380
  815.94    6380  816.11    6550  816.12    6550  817.05    7480  817.06    7500
  817.33    7770  817.34    7790  817.54    7990  817.55    8010   817.7    8160
  817.71    8180  817.85    8320  817.86    8340  817.98    8460  817.99    8480
   818.1    8590  818.11    8610  818.21    8710  818.22    8730  818.32    8830
  818.33    8850  818.42    8940  818.52    9060   818.8    9340  818.81    9360
  819.12    9670  819.13    9690  819.35    9910  819.43   10000  819.48   10100
  819.58   10200  819.67   10300  819.77   10400  819.86   10500  819.96   10600
  820.05   10700  820.14   10800  820.23   10900  820.33   11000  820.42   11100
  820.46   11100
Observed RC Point Data= 0
DSS Import GetInterval= 0
DSS Import GetPeak= 0
DSS Import FillOption= 0

--- Deckers_Creek_Detail_Study.f03 (steady flow) ---

Flow Title=Calibration_Run
Program Version=4.10
Number of Profiles= 31
Profile Names=1,2,3,4,5,6,PF 7,PF 8,PF 9,PF 10,PF 11,PF 12,PF 13,PF 14,PF 15,PF 16,PF 17,PF 18,PF 19,PF 20,PF 21,PF 22,PF 23,PF 24,PF 25,PF 26,PF 27,PF 28,PF 29,PF 30,PF 31
River Rch & RM=Deckers_Creek,1               ,32634.21
    3000    3300    3600    3900    4200    4500    4800    5100    5400    5700
    6000    6300    6600    6900    7200    7500    7800    8100    8400    8700
    9000    9300    9600    9900   10200   10500   10800   11100   11400   11700
   12000
Boundary for River Rch & Prof#=Deckers_Creek,1               , 1
Up Type= 0
Dn Type= 3
Dn Slope=0.0048
Boundary for River Rch & Prof#=Deckers_Creek,1               , 2
Up Type= 0
Dn Type= 3
Dn Slope=0.0048
Boundary for River Rch & Prof#=Deckers_Creek,1               , 3
Up Type= 0
Dn Type= 3
Dn Slope=0.0048
Boundary for River Rch & Prof#=Deckers_Creek,1               , 4
Up Type= 0
Dn Type= 3
Dn Slope=0.0048
Boundary for River Rch & Prof#=Deckers_Creek,1               , 5
Up Type= 0
Dn Type= 3
Dn Slope=0.0048
Boundary for River Rch & Prof#=Deckers_Creek,1               , 6
Up Type= 0
Dn Type= 3
Dn Slope=0.0048
Observed RC=Gage03062500,Deckers_Creek   ,1               ,3541.66 ,0
Observed RC Data= 96
  804.81     .01  806.26     167  807.46     628  808.56    1240   809.3    1710
  809.97    2160  810.89    2750  811.27    3000  811.39    3080  811.47    3140
  811.51    3160  811.72    3310  811.82    3370  811.91    3440  811.95    3460
  812.24    3660  812.28    3680   812.4    3770  812.53    3850  812.62    3920
  812.69    3960  812.78    4030  812.82    4050  812.91    4120  812.95    4140
  813.07    4230  813.17    4290   813.2    4320   813.3    4380  813.33    4410
   813.4    4450  813.53    4550   813.6    4590   813.7    4670  813.77    4710
  813.87    4790  813.98    4860  814.13    4980  814.17    5000  814.36    5150
  814.37    5150  814.48    5240  814.53    5270   814.6    5330  814.65    5360
  814.77    5460  814.82    5490  814.98    5620  815.03    5650  815.17    5770
  815.22    5800  815.42    5960  815.72    6210  815.78    6250  815.93    6380
  815.94    6380  816.11    6550  816.12    6550  817.05    7480  817.06    7500
  817.33    7770  817.34    7790  817.54    7990  817.55    8010   817.7    8160
  817.71    8180  817.85    8320  817.86    8340  817.98    8460  817.99    8480
   818.1    8590  818.11    8610  818.21    8710  818.22    8730  818.32    8830
  818.33    8850  818.42    8940  818.52    9060   818.8    9340  818.81    9360
  819.12    9670  819.13    9690  819.35    9910  819.43   10000  819.48   10100
  819.58   10200  819.67   10300  819.77   10400  819.86   10500  819.96   10600
  820.05   10700  820.14   10800  820.23   10900  820.33   11000  820.42   11100
  820.46   11100
Observed RC Point Data= 0
DSS Import GetInterval= 0
DSS Import GetPeak= 0
DSS Import FillOption= 0

--- Deckers_Creek_Detail_Study.f04 (steady flow) ---

Flow Title=Floodway_Run
Program Version=4.10
Number of Profiles= 2
Profile Names=FP,FW
River Rch & RM=Deckers_Creek,1               ,32634.21
    6055    6055
River Rch & RM=Deckers_Creek,1               ,31129.58
    6063    6063
River Rch & RM=Deckers_Creek,1               ,30281.61
    6109    6109
River Rch & RM=Deckers_Creek,1               ,29587.63
    6282    6282
River Rch & RM=Deckers_Creek,1               ,28151.15
    6295    6295
River Rch & RM=Deckers_Creek,1               ,26492.81
    6314    6314
River Rch & RM=Deckers_Creek,1               ,24704.62
    6347    6347
River Rch & RM=Deckers_Creek,1               ,19640.56
    6357    6357
River Rch & RM=Deckers_Creek,1               ,18766.4
    6459    6459
River Rch & RM=Deckers_Creek,1               ,17765.29
    6496    6496
River Rch & RM=Deckers_Creek,1               ,15354.33
    6506    6506
River Rch & RM=Deckers_Creek,1               ,13828.97
    6507    6507
River Rch & RM=Deckers_Creek,1               ,13485.22
    6675    6675
River Rch & RM=Deckers_Creek,1               ,10935.1
    7293    7293
River Rch & RM=Deckers_Creek,1               ,9078.49
    7392    7392
River Rch & RM=Deckers_Creek,1               ,7701.83
    7411    7411
River Rch & RM=Deckers_Creek,1               ,5788.79
    7425    7425
River Rch & RM=Deckers_Creek,1               ,5189.62
    7447    7447
River Rch & RM=Deckers_Creek,1               ,3081.75
    7449    7449
River Rch & RM=Deckers_Creek,1               ,2531.33
    7463    7463
River Rch & RM=Deckers_Creek,1               ,1706.04
    7474    7474
River Rch & RM=Deckers_Creek,1               ,664.95
    7475    7475
River Rch & RM=Deckers_Creek,1               ,95.51
    7481    7481
Boundary for River Rch & Prof#=Deckers_Creek,1               , 1
Up Type= 0
Dn Type= 3
Dn Slope=0.0048
Boundary for River Rch & Prof#=Deckers_Creek,1               , 2
Up Type= 0
Dn Type= 3
Dn Slope=0.0048
Observed RC=Gage03062500,Deckers_Creek   ,1               ,3541.66 ,0
Observed RC Data= 96
  804.81     .01  806.26     167  807.46     628  808.56    1240   809.3    1710
  809.97    2160  810.89    2750  811.27    3000  811.39    3080  811.47    3140
  811.51    3160  811.72    3310  811.82    3370  811.91    3440  811.95    3460
  812.24    3660  812.28    3680   812.4    3770  812.53    3850  812.62    3920
  812.69    3960  812.78    4030  812.82    4050  812.91    4120  812.95    4140
  813.07    4230  813.17    4290   813.2    4320   813.3    4380  813.33    4410
   813.4    4450  813.53    4550   813.6    4590   813.7    4670  813.77    4710
  813.87    4790  813.98    4860  814.13    4980  814.17    5000  814.36    5150
  814.37    5150  814.48    5240  814.53    5270   814.6    5330  814.65    5360
  814.77    5460  814.82    5490  814.98    5620  815.03    5650  815.17    5770
  815.22    5800  815.42    5960  815.72    6210  815.78    6250  815.93    6380
  815.94    6380  816.11    6550  816.12    6550  817.05    7480  817.06    7500
  817.33    7770  817.34    7790  817.54    7990  817.55    8010   817.7    8160
  817.71    8180  817.85    8320  817.86    8340  817.98    8460  817.99    8480
   818.1    8590  818.11    8610  818.21    8710  818.22    8730  818.32    8830
  818.33    8850  818.42    8940  818.52    9060   818.8    9340  818.81    9360
  819.12    9670  819.13    9690  819.35    9910  819.43   10000  819.48   10100
  819.58   10200  819.67   10300  819.77   10400  819.86   10500  819.96   10600
  820.05   10700  820.14   10800  820.23   10900  820.33   11000  820.42   11100
  820.46   11100
Observed RC Point Data= 0
DSS Import GetInterval= 0
DSS Import GetPeak= 0
DSS Import FillOption= 0

--- Deckers_Creek_Detail_Study.g01 (geometry) ---

Geom Title=Deckers_Creek_Detail_Study
Program Version=4.10

River Reach=Deckers_Creek   ,1
Reach XY= 30
595583.4105527964384966.64517766595070.0663864524384844.24664015
594851.6253677524384655.43827782594494.1193473344384885.73296866
594001.9953572524384841.28398411593406.4374858914384454.01424333
593285.5019883974384521.66460416593112.7809702624384447.79327525
592960.1676083764384627.28694947593084.8399539174384876.63164055
592978.1599525984384912.19265699592718.0222933834384770.58562324
592497.8865866634385110.94664345592491.5376025844385570.89899313
592184.1986147864386099.22103166592252.3549436284386276.38603385
592134.2693261694386360.60227489592169.5925986054386467.75776422
592074.7144534334386551.76674125592056.4813172074386714.21904726
591687.7860886514386863.44303311591358.7758205844387177.37179699
591097.2330333524387130.54232441590888.8747987774386810.66081645
 590603.47531525 4386636.7145023590214.1847504384387036.48104324
589903.4320025984387147.21183661589722.8532403664386932.50156996
589398.6039483594386759.85979983589176.7918416174387038.61769127

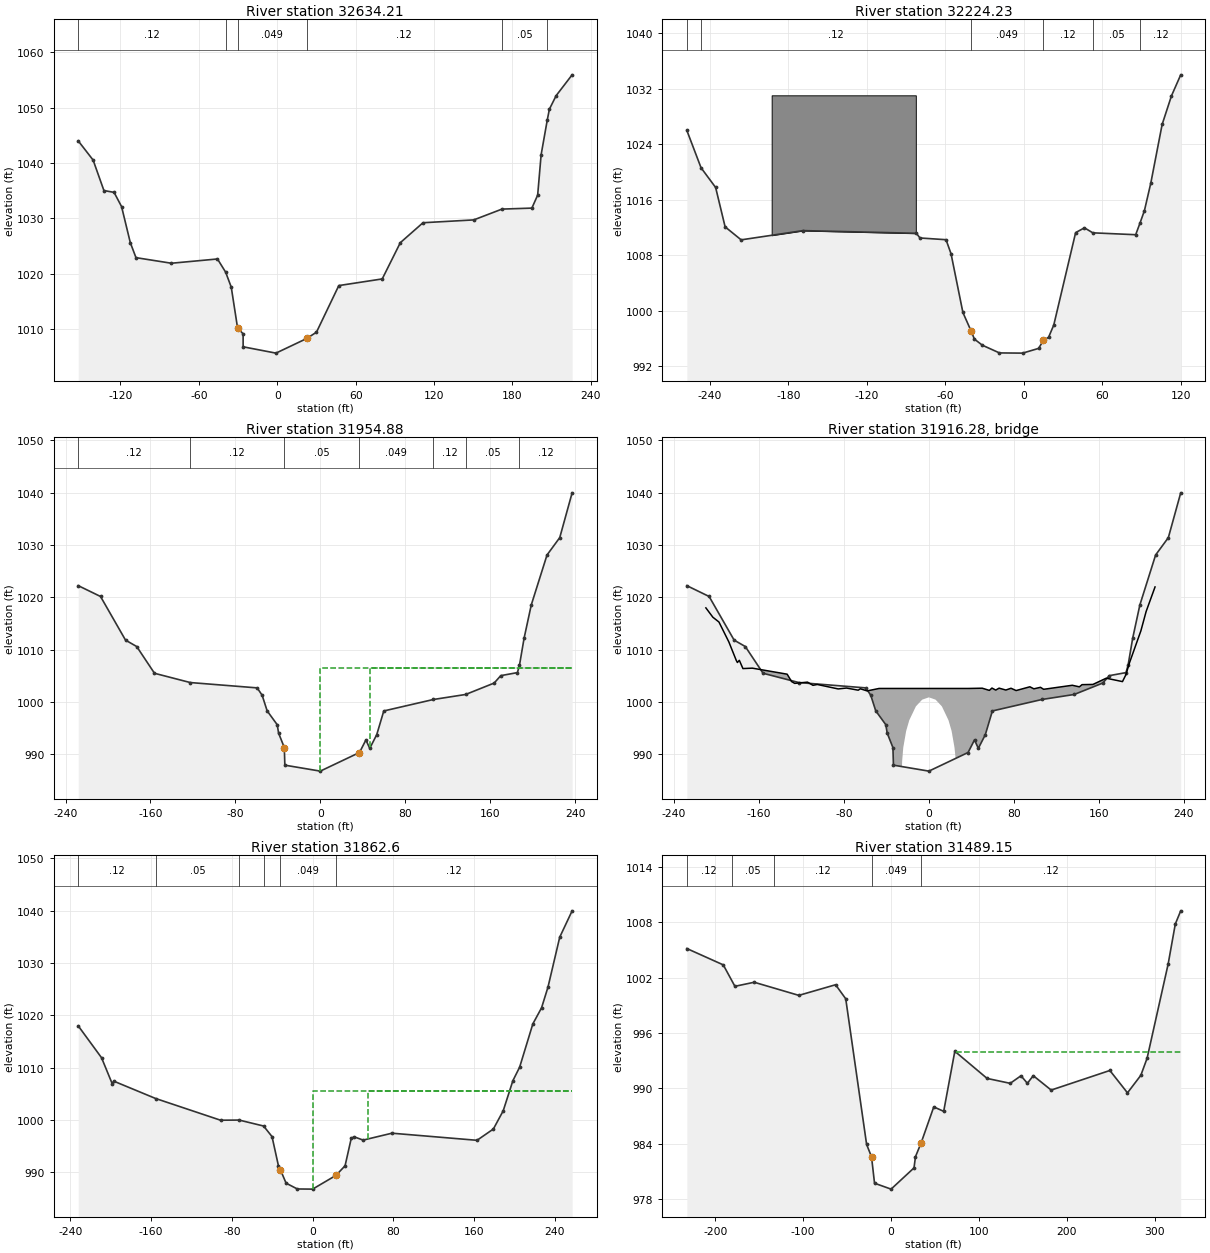
Type RM Length L Ch R = 1 ,32634.21,389.115,409.977,406.584
Node Name=BK
XS GIS Cut Line= 5
595571.706232652 4384920.9617531595575.1291366944384967.69368968
595577.8479527284384999.76169807595579.8169607524385024.42916238
595580.5180007614385035.84087452
#Sta/Elev= 30
-152.329    1044-140.945 1040.54-132.677 1035.04-124.902 1034.71 -119.16 1032.14
-112.467 1025.63-108.136 1022.93 -81.004 1021.92 -45.768 1022.69 -39.501 1020.31
 -35.203  1017.6 -30.381 1010.25 -26.131 1009.18  -26.11 1006.84      -1  1005.7
  22.572 1008.34   30.02 1009.48  47.113 1017.89  80.348 1019.09  94.193 1025.63
 111.549 1029.23 150.394 1029.74 171.982 1031.69 194.882 1031.87 199.311 1034.21
 201.969 1041.51 206.693  1047.8 208.301 1049.73 213.484 1052.17 225.689 1055.92
#Mann= 6 ,-1 , 0
-152.329     .12       0 -39.501     .12       0 -30.381    .049       0
  22.572     .12       0 171.982     .05       0 206.693     .12       0
Bank Sta=-30.381,22.572
XS Rating Curve= 0 ,0
Exp/Cntr=0.3,0.1

Type RM Length L Ch R = 1 ,32224.23,284.191,269.355,237.694
Node Name=BJ
XS GIS Cut Line= 3
595469.7719673924384901.37835286595454.6660792054384978.44398581
595446.7687111084385014.09949025
#Sta/Elev= 30
-257.644 1025.97-246.785 1020.59 -235.63 1017.75-228.379 1012.08-216.142 1010.21
-168.766 1011.54 -82.185 1011.15 -79.462 1010.48 -59.547 1010.23 -55.709  1008.2
 -46.654  999.75 -40.256  997.03  -37.87  995.92   -31.8  995.04  -18.73  993.93
      -1   993.9   11.18  994.58  14.895  995.74  18.832  996.18  22.802  997.95
  39.501 1011.25  46.227 1011.94  52.657 1011.22    85.4 1010.95  88.845  1012.7
  92.093 1014.43  96.949 1018.38  105.61 1026.82 112.762 1030.95 119.816 1033.97
#Mann= 6 ,-1 , 0
-257.644     .12       0-246.785     .12       0 -40.256    .049       0
  14.895     .12       0  52.657     .05       0  88.845     .12       0
#Block Obstruct= 1 ,-1
-192.815 -82.644 1031.02
Bank Sta=-40.256,14.895
XS Rating Curve= 0 ,0
Exp/Cntr=0.5,0.3

Type RM Length L Ch R = 1 ,31954.88,93.684,92.283,109.225
XS GIS Cut Line= 6
595364.3264060894384869.53894446595371.6233181794384905.87110491
595383.7269263294384944.89464939 595390.35023041 4384961.1557296
595401.5912545494384974.13716176595409.4215666464385011.20084221
#Sta/Elev= 30
-228.018 1022.25-207.022 1020.18-183.468 1011.84-172.924 1010.61-156.183  1005.5
-122.487 1003.73 -59.471 1002.71 -54.785 1001.31 -50.068  998.32 -40.541  995.66
 -39.308  994.08 -33.882   991.3 -33.387  987.94       0   986.8  36.935  990.36
  42.977  992.76  46.583  991.15  53.181  993.77   59.81   998.3 106.517 1000.49
 136.915 1001.45 163.769 1003.63 170.027 1005.05 185.688 1005.63 187.599 1006.99
 191.977 1012.19  198.76 1018.57 213.589 1028.11 225.582 1031.43 237.236 1039.99
#Mann= 7 ,-1 , 0
-228.018     .12       0-122.487     .12       0 -33.882     .05       0
  36.935    .049       0 106.517     .12       0 136.915     .05       0
 187.599     .12       0
#XS Ineff= 2 , 0
       0 -46.985  1006.6  47.105       0  1006.6
Permanent Ineff=
       F       F
Bank Sta=-33.882,36.935
XS Rating Curve= 0 ,0
Skew Angle= 20
Exp/Cntr=0.5,0.3

Type RM Length L Ch R = 3 ,31916.28,,,
BEGIN DESCRIPTION:
Earl L Core Road / STATE ROUTE 7 - Field Recon ID Deck 12
END DESCRIPTION:
Bridge Culvert--1,0,-1,-1, 0
Deck Dist Width WeirC Skew NumUp NumDn MinLoCord MaxHiCord MaxSubmerge Is_Ogee
27.1,30,2.5,20, 60, 60, , , 0.98, 0, 0,0,,
-210.075-203.476-197.773-188.432-181.403-180.385-178.566-175.175-166.265-133.524
  -129.3-126.372-114.347-109.199-105.099  -85.46  -77.63 -66.562 -64.558 -58.175
 -46.985 -25.372 -25.174 -24.131 -21.425 -18.493 -12.225  -6.305       0   6.305
  12.225  18.493  21.425  24.131  25.174  25.372  37.588  50.284  56.943  59.409
  62.955  66.131  72.511  77.352  82.161  95.141  98.902  105.13 108.089 135.096
 141.755 144.283 154.519 167.068 182.359 185.626 188.617 199.716 204.649 213.034
    1018 1016.21  1015.3 1011.49 1007.94 1007.56 1007.98  1006.4 1006.48 1005.33
 1003.91 1003.57 1003.81  1003.2 1003.36 1002.51 1002.68 1002.27 1002.54 1002.13
  1002.6  1002.6  1002.6  1002.6  1002.6  1002.6  1002.6  1002.6  1002.6  1002.6
  1002.6  1002.6  1002.6  1002.6  1002.6  1002.6  1002.6 1002.65 1002.23 1002.68
 1002.29 1002.66  1002.3 1002.64  1002.2 1002.92 1002.53 1002.82 1002.44 1003.21
 1002.91 1003.33 1003.37 1004.56 1003.91 1005.24  1007.3 1013.62 1017.31    1022
                                                                                
                                                                                
             987  988.74   991.3  994.45  996.52  999.18 1000.46  1000.9 1000.46
  999.18  996.52  994.45   991.3  988.74     987
                                                                                
                                                                                
-210.075-203.476-197.773-188.432-181.403-180.385-178.566-175.175-166.265-133.524
  -129.3-126.372-114.347-109.199-105.099  -85.46  -77.63 -66.562 -64.558 -58.175
 -46.985 -25.372 -25.174 -24.131 -21.425 -18.493 -12.225  -6.305       0   6.305
  12.225  18.493  21.425  24.131  25.174  25.372  37.588  50.284  56.943  59.409
  62.955  66.131  72.511  77.352  82.161  95.141  98.902  105.13 108.089 135.096
 141.755 144.283 154.519 167.068 182.359 185.626 188.617 199.716 204.649 213.034
    1018 1016.21  1015.3 1011.49 1007.94 1007.56 1007.98  1006.4 1006.48 1005.33
 1003.91 1003.57 1003.81  1003.2 1003.36 1002.51 1002.68 1002.27 1002.54 1002.13
  1002.6  1002.6  1002.6  1002.6  1002.6  1002.6  1002.6  1002.6  1002.6  1002.6
  1002.6  1002.6  1002.6  1002.6  1002.6  1002.6  1002.6 1002.65 1002.23 1002.68
 1002.29 1002.66  1002.3 1002.64  1002.2 1002.92 1002.53 1002.82 1002.44 1003.21
 1002.91 1003.33 1003.37 1004.56 1003.91 1005.24  1007.3 1013.62 1017.31    1022
                                                                                
                                                                                
             987  988.74   991.3  994.45  996.52  999.18 1000.46  1000.9 1000.46
  999.18  996.52  994.45   991.3  988.74     987
                                                                                
                                                                                
BR Coef=-1 , 1 , 0 ,, 0 ,,,0.8,-1,0.3,1,
WSPro=,,,, 1 ,,,, 0 ,,,, 0 ,,,,-1 ,-1 ,-1 , 0 , 0 , 0 , 0 , 0
BC Design=,, 0 ,, 0 ,,,,,,
BC Use User HTab Curves=0
BC User HTab FreeFlow(D)= 0

Type RM Length L Ch R = 1 ,31862.6 ,356.314,373.447,388.664
XS GIS Cut Line= 6
595337.1351977534384860.85519236595347.787957884  4384913.155825
595359.8702300344384951.93248148595368.1150701364384972.17424973
595379.097014271 4384985.8628179595385.948918356 4385009.9084902
#Sta/Elev= 30
-232.117    1018-209.026 1011.91-198.482 1006.95-196.972 1007.44-155.444 1004.12
 -91.164  999.97  -72.76    1000 -48.526  998.86 -40.202  996.84 -33.789  991.22
 -31.908  990.51 -26.264  987.94 -15.119  986.83       0   986.8  23.091  989.42
  32.155  991.26  38.353  996.57  41.405  996.78  50.068  996.17  78.586  997.49
 162.843  996.13 179.028  998.29 188.772 1001.77 198.359 1007.53  205.05 1010.11
 218.121 1018.38 226.754 1021.45 233.135 1025.42 244.758 1034.96 257.028 1039.99
#Mann= 6 ,-1 , 0
-232.117     .12       0-155.444     .05       0  -72.76     .12       0
 -48.526     .12       0 -31.908    .049       0  23.091     .12       0
#XS Ineff= 2 , 0
       0 -56.381  1005.6  54.502       0  1005.6
Permanent Ineff=
       F       F
Bank Sta=-31.908,23.091
XS Rating Curve= 0 ,0
Skew Angle= 20
Exp/Cntr=0.5,0.3

Type RM Length L Ch R = 1 ,31489.15,357.306,359.57,369.121
Node Name=BI
XS GIS Cut Line= 3
595263.9649088484384834.25834403595261.8160688224384842.61291213
 595221.241092324385000.15793808
#Sta/Elev= 30
-232.447 1005.14-190.978 1003.37-177.723 1001.05-155.774 1001.49-104.987 1000.07
 -63.156 1001.22 -51.608   999.7 -27.854  983.94 -22.244  982.59  -18.84  979.74
       0   979.1  26.115   981.4  27.756  982.61  34.088  984.08  48.589     988
  59.875  987.52  72.539  994.02 109.285  991.08 135.564  990.55 147.867  991.37
 155.118  990.55 161.811  991.38 182.185  989.82 248.983  991.94 269.029  989.52
 284.252  991.42 291.371  993.27 315.322 1003.46 323.458 1007.79 329.626 1009.22
#Mann= 5 ,-1 , 0
-232.447     .12       0-181.266     .05       0 -132.94     .12       0
 -22.244    .049       0  34.088     .12       0
#XS Ineff= 2 , 0
                           73.57          993.97
Permanent Ineff=
       F       F
Bank Sta=-22.244,34.088
XS Rating Curve= 0 ,0
Exp/Cntr=0.3,0.1

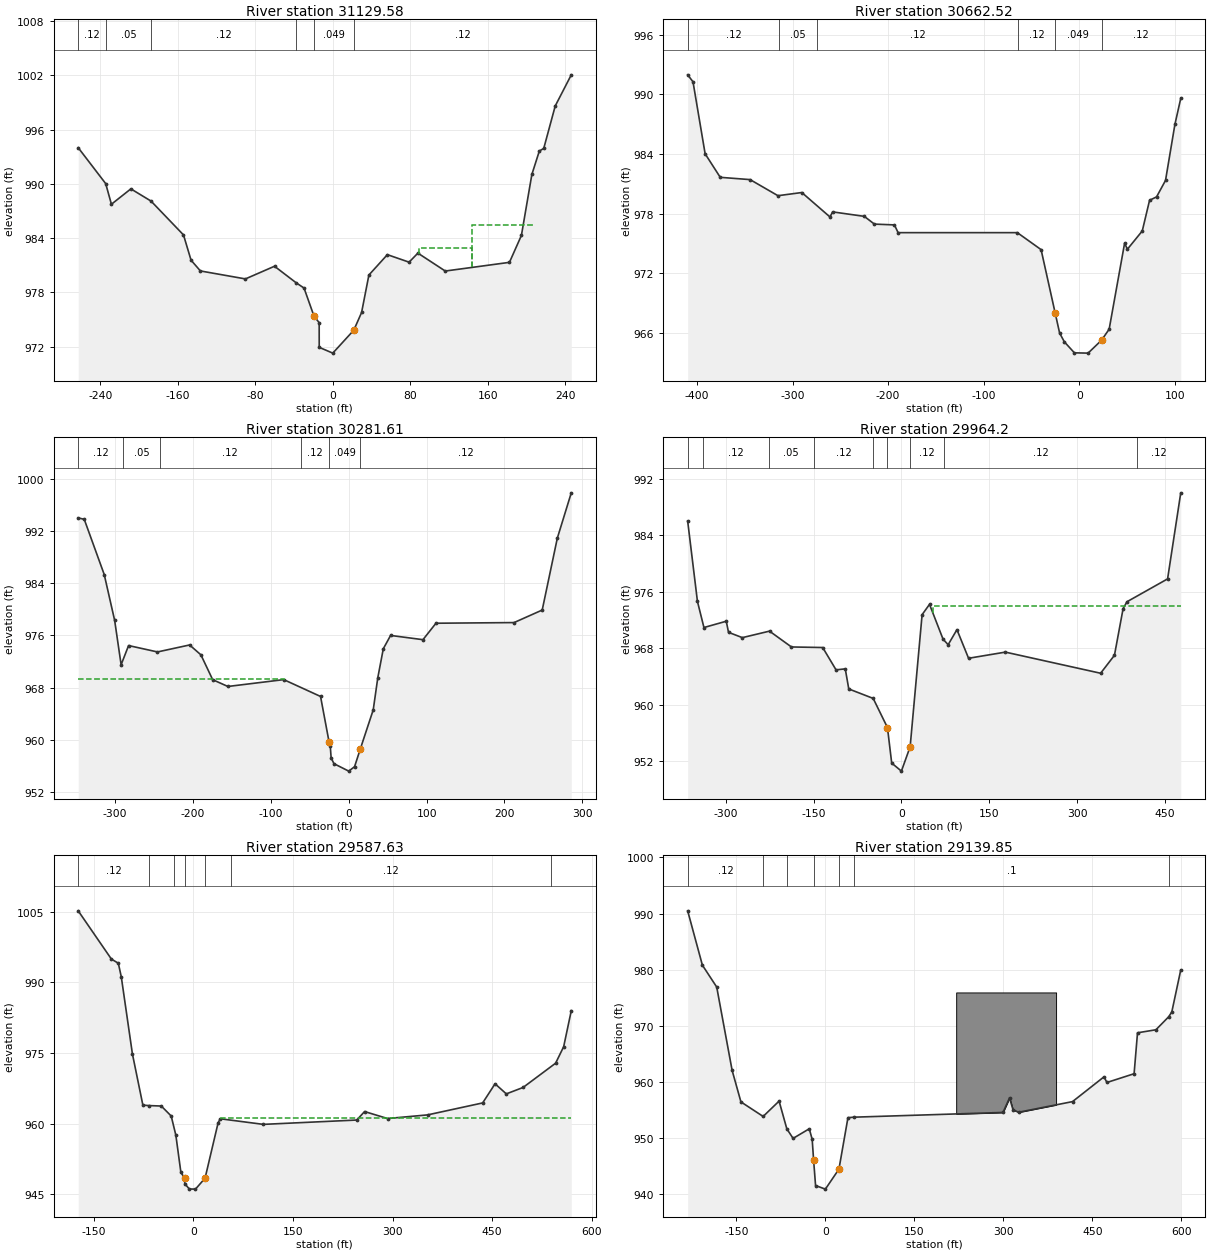
Type RM Length L Ch R = 1 ,31129.58,439.388,467.057,492.033
Node Name=BH
XS GIS Cut Line= 3
595193.7908039814384806.86901569595151.0822274534384844.81356816
595117.913891043 4384936.9942333
#Sta/Elev= 30
 -262.73     994 -234.35  990.03-228.445  987.75-208.366  989.45-187.566   988.1
-154.068  984.36 -146.26  981.57-136.614  980.38 -90.157   979.5 -60.138   980.9
 -37.533  979.05 -29.659  978.49 -19.291  975.36 -14.042  974.67     -14  971.94
       0   971.3  21.719  973.84  29.724  975.79   37.27  979.93  56.332  982.18
   78.74  981.35  87.828  982.35 116.076  980.37 182.316  981.33 194.652   984.3
 205.446  991.04 213.156  993.63 217.717  993.92  229.56  998.61 246.129 1002.05
#Mann= 6 ,-1 , 0
 -262.73     .12       0 -234.35     .05       0-187.566     .12       0
 -37.533     .12       0 -19.291    .049       0  21.719     .12       0
#XS Ineff= 2 ,-1
   89.03  143.89  982.94  143.89  206.73  985.51
Permanent Ineff=
       F       F
Bank Sta=-19.291,21.719
XS Rating Curve= 0 ,0
Exp/Cntr=0.3,0.1

Type RM Length L Ch R = 1 ,30662.52,392.351,380.914,371.506
Node Name=BG
XS GIS Cut Line= 3
595132.9710112294384722.23824664595085.1753226394384758.47896709
595003.3852896284384811.18803174
#Sta/Elev= 30
-409.744  991.98-404.167  991.28 -391.47  984.03-375.656  981.66 -344.39  981.43
-315.256  979.81-290.289  980.13-260.827  977.67-258.038  978.18-224.902  977.73
-214.337  976.95-193.373  976.87-189.534  976.09 -64.764  976.09 -39.895  974.38
 -25.164     968 -20.505  965.98 -15.584   965.1  -5.052  963.99   9.285  963.96
   23.36  965.26  31.332  966.37  47.507  975.03  50.427  974.42  65.978  976.26
  73.622  979.35  80.938  979.69  90.322  981.35 100.164     987 106.266  989.61
#Mann= 6 ,-1 , 0
-409.744     .12       0-313.878     .05       0-274.606     .12       0
 -63.681     .12       0 -25.164    .049       0   23.36     .12       0
Bank Sta=-25.164,23.36
XS Rating Curve= 0 ,0
Exp/Cntr=0.3,0.1

Type RM Length L Ch R = 1 ,30281.61,328.043,317.408,311.269
Node Name=BF
XS GIS Cut Line= 3
595013.9679457594384619.22498937594927.0054566844384750.33775899
594925.4418326654384785.95973543
#Sta/Elev= 30
-347.375     994  -339.6  993.78-313.944  985.32-300.558  978.29-292.257   971.5
-282.677  974.44-245.571  973.46-204.331  974.53-189.829  973.02-174.705  969.21
-155.151  968.17 -83.432  969.22 -36.188  966.64  -25.23  959.66 -23.688  959.02
   -22.6  957.22  -18.95  956.34       0   955.2     7.5  955.88  14.797  958.57
  31.463  964.59  37.303   969.5   44.39  973.95   53.74  975.99  95.308  975.34
 112.008  977.86  212.27  977.96 248.425  979.88 267.848   990.9 285.761  997.84
#Mann= 6 ,-1 , 0
-347.375     .12       0-290.026     .05       0-242.487     .12       0
 -61.549     .12       0  -25.23    .049       0  14.797     .12       0
#XS Ineff= 2 , 0
          -83.46   969.3
Permanent Ineff=
       F       F
Bank Sta=-25.23,14.797
XS Rating Curve= 0 ,0
Exp/Cntr=0.3,0.1

Type RM Length L Ch R = 1 ,29964.2 ,404.726,376.567,355.094
Node Name=BJ
XS GIS Cut Line= 3
594906.0199764254384555.83573259594856.4381598124384704.71529443
594904.1363124014384792.41235151
#Sta/Elev= 30
-365.125  985.98-348.425  974.61-337.336  970.92-299.213  971.81-295.341  970.24
-271.686  969.49-225.328  970.41-187.861  968.17-134.449  968.09-111.647  964.93
 -95.899  965.07 -89.928  962.23 -48.196  960.89 -23.819  956.76  -16.58  951.74
       0   950.6  14.928  954.05  35.367  972.74  48.031   974.2  71.161  969.27
  79.856  968.49  94.882  970.62 114.731  966.57 177.625  967.44 340.322  964.45
 363.944  966.99 378.773  973.61   385.4  974.57 454.724   977.8 477.231  989.98
#Mann= 9 ,-1 , 0
-365.125     .12       0-338.255     .12       0-226.739     .05       0
-149.705     .12       0 -48.458     .12       0 -23.819    .049       0
  14.928     .12       0  72.244     .12       0 402.723     .12       0
#XS Ineff= 2 , 0
                           53.87             974
Permanent Ineff=
       F       F
Bank Sta=-23.819,14.928
XS Rating Curve= 0 ,0
Exp/Cntr=0.3,0.1

Type RM Length L Ch R = 1 ,29587.63,449.552,447.779,444.931
Node Name=BI
XS GIS Cut Line= 3
594735.1917663134384647.77865372594852.5306237634384816.58908781
 594864.384295914384833.79504802
#Sta/Elev= 30
 -173.72 1005.15-123.688  994.91-113.255  994.03-108.793  991.15 -91.995  974.77
 -76.247  963.92 -67.356  963.83 -48.491  963.73 -33.563  961.61 -26.575  957.55
 -18.963  949.65 -13.189  948.41  -13.11  947.24   -6.27  946.13       3   946.1
  17.454  948.42  37.106  960.16  40.387  961.03 105.217  959.84 245.997  960.76
 257.874  962.56 292.454  961.08  352.69  961.85 435.761  964.39 454.462  968.45
 471.424  966.31 496.654  967.67 545.702  972.82 557.841  976.32 569.324  983.97
#Mann= 7 ,-1 , 0
 -173.72     .12       0 -67.356     .05       0 -29.823     .12       0
 -13.189    .049       0  17.454     .12       0  56.201     .12       0
 538.714     .12       0
#XS Ineff= 2 , 0
                           40.73          961.24
Permanent Ineff=
       F       F
Bank Sta=-13.189,17.454
XS Rating Curve= 0 ,0
Exp/Cntr=0.3,0.1

Type RM Length L Ch R = 1 ,29139.85,162.945,140.033,124.104
Node Name=BH
XS GIS Cut Line= 4
594607.2519647324384713.64288654 594700.953581894384825.53801592
594745.9969264474384885.58361666594765.2267586854384911.54343298
#Sta/Elev= 30
-232.087  990.48-207.283   980.8-183.136   976.9-157.152  962.05-142.323  956.44
-104.888  953.85 -78.018  956.58 -64.961  951.64 -54.429  949.94 -27.133  951.65
 -22.244  949.78 -19.783  946.02  -16.53  941.54       0   940.9  22.867  944.46
  38.058  953.63  48.491  953.72 299.377  954.56   310.4  957.17 316.306  955.02
 325.886   954.6 416.535  956.49 469.554   960.9 474.573   959.9 520.341  961.46
 526.083  968.75 557.119  969.29 578.675  971.61 583.891  972.47 598.983  979.95
#Mann= 7 ,-1 , 0
-232.087     .12       0-104.888     .05       0 -64.961     .12       0
 -19.783    .049       0  22.867     .12       0  48.491      .1       0
 578.675     .12       0
#XS Ineff= 2 ,-1
     -80     -29   951.5    -125     -95     954
Permanent Ineff=
       F       F
#Block Obstruct= 1 ,-1
 220.472 388.845  975.94
Bank Sta=-19.783,22.867
XS Rating Curve= 0 ,0
Exp/Cntr=0.5,0.3

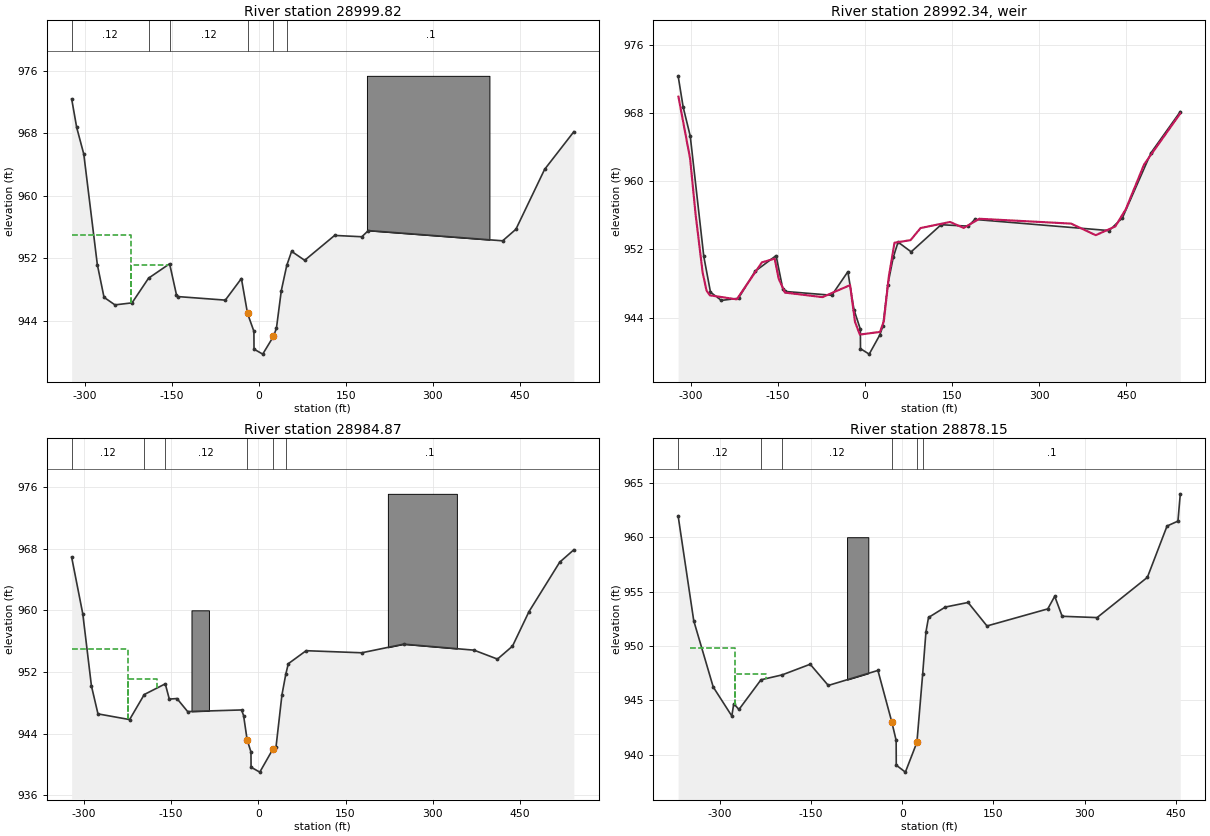
Type RM Length L Ch R = 1 ,28999.82,13.814,14.95,15.144
XS GIS Cut Line= 4
594550.2726520284384726.36828669594609.0990527554384790.59574349
594635.0741090764384800.79435161594724.0696141764384919.92238509
#Sta/Elev= 30
-322.178  972.41-313.484  968.74 -301.28  965.33-277.953  951.18-266.404  946.98
-247.572  946.01-218.143  946.27-189.698949.4304-153.412951.2789-141.634  947.31
-138.517  947.07 -57.448  946.62 -29.724  949.39  -19.16  944.91   -8.19  942.62
      -8  940.34       7   939.7  25.361  941.96   30.61  943.01  39.042  947.85
  48.425951.0709  56.759  952.87  79.265  951.72 130.873  954.91 177.756  954.74
 188.944  955.53 420.308  954.22 443.176   955.7 492.585  963.37 542.979   968.2
#Mann= 6 ,-1 , 0
-322.178     .12       0-189.698     .05       0-153.412     .12       0
  -19.16    .049       0  25.361     .12       0  48.425      .1       0
#XS Ineff= 2 ,-1
    -220    -157   951.1    -350    -220     955
Permanent Ineff=
       F       F
#Block Obstruct= 1 ,-1
 186.516 397.572  975.36
Bank Sta=-19.16,25.361
XS Rating Curve= 0 ,0
Exp/Cntr=0.5,0.3

Type RM Length L Ch R = 5 ,28992.34,,,
IW Pilot Flow=0
#Inline Weir SE= 30
-321.654  969.96-301.509  962.67-292.192   956.2-279.987   949.3-273.196  947.16
-267.487  946.61-221.194  946.14-177.756  950.49-155.807  950.92-148.819  948.54
-137.992  946.93 -73.524   946.4 -25.951  947.81 -17.421  943.49  -9.154     942
  25.689  942.31  32.218  943.56  40.945  948.88  50.591  952.79  78.314   953.1
  95.505  954.52 146.325  955.23 169.882  954.53 196.686  955.61 354.888  955.04
 397.211  953.68 431.102  954.71  449.18  956.75 480.676     962 542.815  967.98
IW Dist,WD,Coef,Skew,MaxSub,Min_El,Is_Ogee,SpillHt,DesHd
1,2,2.6,0,0.98,, 0 ,,,0,0,

Type RM Length L Ch R = 1 ,28984.87,89.555,106.719,123.968
XS GIS Cut Line= 4
594547.3221879914384729.07186273594606.7764767264384793.98207153
594632.5534130454384804.10143165594720.8661661364384922.31506512
#Sta/Elev= 30
-321.096   966.9-301.936  959.54-287.073  950.19 -275.82  946.56-221.424  945.82
-196.227949.0704-160.072950.4606 -153.15  948.48-139.961  948.55-121.588  946.86
 -28.806  947.07 -25.328  946.32 -19.259  943.19  -12.69  941.62   -12.5  939.64
     2.5     939  24.738  941.95  30.446  942.29  40.617  949.03  47.178 951.688
  51.509  953.07  82.185  954.76 177.854  954.49 249.869  955.61 370.997  954.83
 411.319  953.67 437.106  955.35  465.42  959.82  518.34  966.25 542.651  967.86
#Mann= 6 ,-1 , 0
-321.096     .12       0-196.227     .05       0-160.072     .12       0
 -19.259    .049       0  24.738     .12       0  47.178      .1       0
#XS Ineff= 2 ,-1
    -225    -175   951.1    -375    -225     955
Permanent Ineff=
       F       F
#Block Obstruct= 2 ,-1
 222.802  341.47  975.12    -115     -85     960
Bank Sta=-19.259,24.738
XS Rating Curve= 0 ,0
Exp/Cntr=0.5,0.3

Type RM Length L Ch R = 1 ,28878.15,65.627,65.762,65.861
XS GIS Cut Line= 6
594516.2386836074384733.94561479594527.3273077444384744.12288691
594571.6360842924384793.00671152594600.7993486524384831.38103199
594669.1141734974384914.58838502594678.3343736114384926.49692117
#Sta/Elev= 30
-369.062  961.97 -343.34  952.32-311.286  946.23-280.676  943.56-277.461  944.69
 -268.93  944.16-232.677  946.89  -197.9  947.34-151.673  948.32-121.883  946.37
  -40.19  947.75 -17.487  943.04  -10.19  941.32     -10  939.04       5   938.4
  23.983  941.14   33.53  947.46  38.845  951.29  43.077  952.62  70.801  953.58
 108.202     954 139.304  951.84 239.403  953.41 250.787  954.57 263.058  952.73
 320.505  952.61 403.314  956.31 435.696  961.03 453.609  961.48 457.513  963.99
#Mann= 6 ,-1 , 0
-369.062     .12       0-232.677     .05       0  -197.9     .12       0
 -17.487    .049       0  23.983     .12       0   33.53      .1       0
#XS Ineff= 2 ,-1
    -350    -275   949.8    -275    -225   947.4
Permanent Ineff=
       F       F
#Block Obstruct= 1 ,-1
     -91     -56     960
Bank Sta=-17.487,23.983
XS Rating Curve= 0 ,0
Exp/Cntr=0.5,0.3