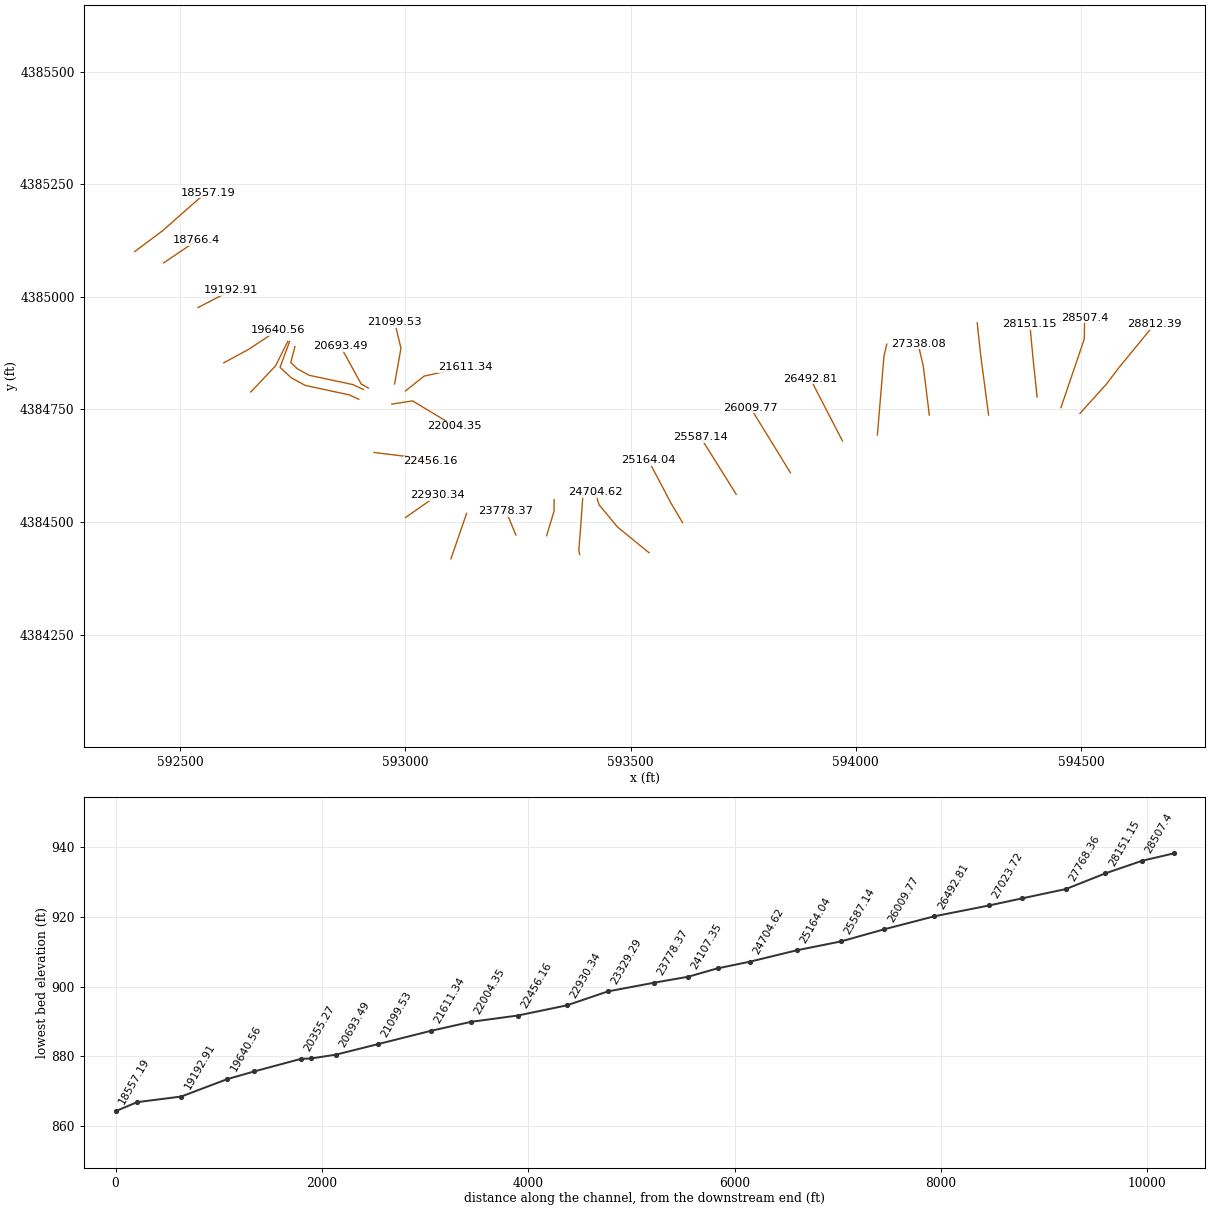
HEC-RAS study Deckers_Creek_Detail_Study.prj: Deckers_Creek_Detail_Study

--- Deckers_Creek_Detail_Study.g01 (geometry) --- (continued)

Type RM Length L Ch R = 3 ,28845.27,,,
BEGIN DESCRIPTION:
Private Road - Field Recon ID Deck 11
END DESCRIPTION:
Bridge Culvert--1,0,-1,-1, 0
Deck Dist Width WeirC Skew NumUp NumDn MinLoCord MaxHiCord MaxSubmerge Is_Ogee
25.16,16.3,2.6,0, 60, 60, , , 0.98, 0, 0,0,,
-384.744-377.854-364.272 -360.63-350.853 -346.03-331.529-324.344-317.421-312.238
-303.806-298.031-289.764-275.525-266.043-256.299-236.942-207.119-196.588-138.091
-125.755-121.293 -77.428 -46.654   -35.1     -35     -30      28    28.1  34.055
  40.059  54.035   71.49   97.31 107.513  114.37 126.739  130.61 170.833 184.711
  191.47 197.113 202.789 215.715 220.636 223.261 227.428 251.476 259.219 263.681
 276.116 281.463 311.155 336.319 362.172 386.056  411.68 420.735 446.982   452.1
  963.95  959.86  953.93  953.27   949.7  948.59   946.2  945.88  944.92  945.24
  944.35  943.07  942.71  943.85  945.67  945.52  946.82  945.59  946.15  946.05
  946.75  946.44   946.9  948.48  948.33     949     949     949  948.33  948.62
  949.57   949.8  950.82  951.07  950.48  951.14   950.9  951.39  951.42  952.11
  951.58  952.33  951.96  952.51  952.09  952.71  952.27  952.93  952.69  953.44
  953.71  953.12  953.62  955.56  955.82  957.24  958.01  959.05  963.84  963.99
                                                                                
                                                                                
                                                     947     947
                                                                                
                                                                                
                                                                                
-384.744-377.854-364.272 -360.63-350.853 -346.03-331.529-324.344-317.421-312.238
-303.806-298.031-289.764-275.525-266.043-256.299-236.942-207.119-196.588-138.091
-125.755-121.293 -77.428 -46.654   -35.1     -35     -30      28    28.1  34.055
  40.059  54.035   71.49   97.31 107.513  114.37 126.739  130.61 170.833 184.711
  191.47 197.113 202.789 215.715 220.636 223.261 227.428 251.476 259.219 263.681
 276.116 281.463 311.155 336.319 362.172 386.056  411.68 420.735 446.982   452.1
  963.95  959.86  953.93  953.27   949.7  948.59   946.2  945.88  944.92  945.24
  944.35  943.07  942.71  943.85  945.67  945.52  946.82  945.59  946.15  946.05
  946.75  946.44   946.9  948.48  948.33     949     949     949  948.33  948.62
  949.57   949.8  950.82  951.07  950.48  951.14   950.9  951.39  951.42  952.11
  951.58  952.33  951.96  952.51  952.09  952.71  952.27  952.93  952.69  953.44
  953.71  953.12  953.62  955.56  955.82  957.24  958.01  959.05  963.84  963.99
                                                                                
                                                                                
                                                     947     947
                                                                                
                                                                                
                                                                                
Pier Skew, UpSta & Num, DnSta & Num=  ,-10, 2 ,-10, 2 , 0 , 0 , 0 ,,
       1       1
     937     948
       1       1
     937     948
Pier Skew, UpSta & Num, DnSta & Num=  ,10, 2 ,10, 2 , 0 , 0 , 0 ,,
       1       1
     937     948
       1       1
     937     948
BR Coef=-1 , 1 , 1 ,1.25, 0 ,,,0.8,0,2,0,
WSPro=,,,, 1 ,,,, 0 ,,,, 0 ,,,,-1 ,-1 ,-1 , 0 , 0 , 0 , 0 , 0
BC Design=,, 0 ,, 0 ,,,,,,
BC Use User HTab Curves=0
BC User HTab FreeFlow(D)= 0

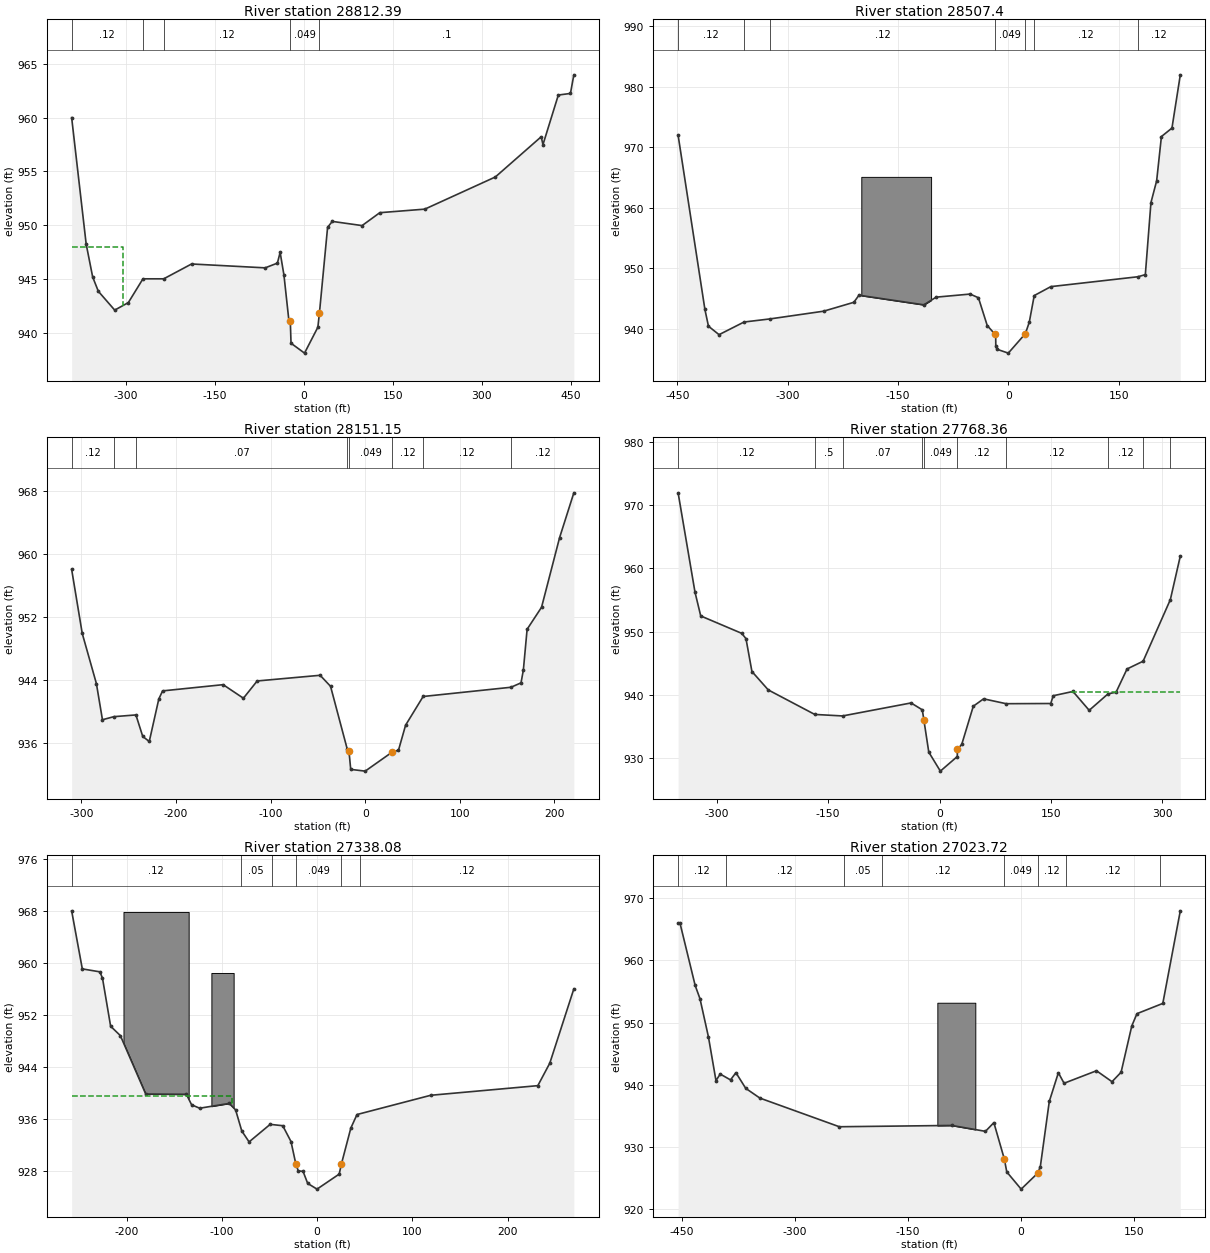
Type RM Length L Ch R = 1 ,28812.39,290.484,304.993,313.564
XS GIS Cut Line= 6
594497.7830433794384741.00783088 594510.825435544384755.69919106
594556.2375881024384805.79611968594585.1021484584384843.78029615
594652.8073732954384926.24698516594663.1248534234384938.90532932
#Sta/Elev= 30
 -391.01     960-366.535  948.24-355.577  945.18 -346.03  943.85-318.438   942.1
 -295.44   942.8-270.833  945.01-235.827  945.01-188.878  946.39 -64.829  946.03
 -44.226  946.47   -39.6  947.47 -33.202  945.37 -24.803  941.11 -22.474  941.11
  -21.25  939.02     1.5   938.1      24  940.51  26.673  941.85  40.387   949.8
  48.327  950.35  98.524  949.96 128.412  951.16 204.232  951.49  323.13  954.48
 400.427  958.22 403.412  957.49 429.298   962.1 449.738  962.25 455.446  963.98
#Mann= 5 ,-1 , 0
 -391.01     .12       0-270.833     .05       0-235.827     .12       0
 -22.474    .049       0  26.673      .1       0
#XS Ineff= 1 ,-1
    -430    -305     948
Permanent Ineff=
       F
Bank Sta=-22.474,26.673
XS Rating Curve= 0 ,0
Exp/Cntr=0.5,0.3

Type RM Length L Ch R = 1 ,28507.4 ,341.83,356.253,367.817
Node Name=BG
XS GIS Cut Line= 3
594455.5651948574384754.08375104594507.3659554984384906.32525692
594508.170627508 4384953.6911775
#Sta/Elev= 30
-449.081     972-412.631  943.21-407.808  940.45-393.406  939.05-359.416  941.14
 -323.72  941.66-251.181  942.93-210.039   944.4-203.117  945.57-114.862  943.98
  -98.13  945.25 -51.903  945.76 -40.617  945.15 -28.642  940.56 -17.815  939.08
 -17.159  939.14     -17  937.14  -15.38  936.64       0     936  23.196  939.21
  28.543  941.11  35.269  945.51  57.874  946.99 176.247  948.62 186.385  948.97
 194.029  960.88 201.772  964.47 208.268  971.79 222.605  973.19 233.957  981.99
#Mann= 7 ,-1 , 0
-449.081     .12       0-359.416     .05       0 -323.72     .12       0
 -17.815    .049       0  23.196     .12       0  35.269     .12       0
 176.247     .12       0
#Block Obstruct= 1 ,-1
-199.934-104.987  965.13
Bank Sta=-17.815,23.196
XS Rating Curve= 0 ,0
Exp/Cntr=0.3,0.1

Type RM Length L Ch R = 1 ,28151.15,389.674,382.785,387.363
Node Name=BF
XS GIS Cut Line= 3
594402.5787622034384777.70575133594392.9013620834384869.86508047
594386.4792260044384938.64624932
#Sta/Elev= 30
-310.203  957.99-299.016  949.87-284.055  943.51-277.657  938.92-265.551  939.31
 -242.29  939.53-235.072   936.8-228.182  936.16 -218.11  941.55-214.108  942.58
-150.131  943.37-128.707  941.65 -114.14  943.84 -47.638  944.56 -36.614  943.16
 -18.996   935.2 -17.126  934.91  -15.31  932.62       0   932.4  28.576  934.82
  35.171  935.05  42.684  938.23   61.22  941.87 154.003  943.04 164.665   943.6
 167.126  945.22 171.096   950.4 186.352  953.19 205.381  962.01 220.472  967.71
#Mann= 8 ,-1 , 0
-310.203     .12       0-265.551     .05       0 -242.29     .07       0
 -18.996     .12       0 -17.126    .049       0  28.576     .12       0
   61.22     .12       0 154.003     .12       0
Bank Sta=-17.126,28.576
XS Rating Curve= 0 ,0
Exp/Cntr=0.3,0.1

Type RM Length L Ch R = 1 ,27768.36,434.362,430.273,432.882
Node Name=BE
XS GIS Cut Line= 3
594294.8380568714384737.56054283594277.9033686624384865.94535242
594269.5183205584384942.06610536
#Sta/Elev= 30
-352.067  971.98-329.331  956.24-321.621  952.48-266.371  949.72-260.696  948.88
 -252.69  943.68-230.676  940.76 -168.11  936.88-130.676  936.64 -38.451   938.7
 -23.327  937.61 -21.194  936.01  -14.59  930.91       1   927.9   23.77  930.21
  24.016  931.36  29.757  932.12  45.341  938.18  59.186  939.35  89.567  938.58
 149.606  938.61 152.953  939.84 179.528  940.52 201.378  937.53 226.837  940.15
 237.533  940.39 252.329  944.08 273.983  945.31  310.63  955.06 324.049  961.97
#Mann= 10 ,-1 , 0
-352.067     .12       0 -168.11      .5       0-130.676     .07       0
 -23.327     .12       0 -21.194    .049       0  24.016     .12       0
  89.567     .12       0 226.837     .12       0 273.983     .12       0
  310.63     .12       0
#XS Ineff= 2 , 0
       0                  177.22       0  940.51
Permanent Ineff=
       F       F
Bank Sta=-21.194,24.016
XS Rating Curve= 0 ,0
Exp/Cntr=0.3,0.1

Type RM Length L Ch R = 1 ,27338.08,326.19,314.36,307.971
Node Name=BD
XS GIS Cut Line= 3
594163.2437032454384737.64283883594149.8111670794384846.33147218
594138.2318149354384896.16932079
#Sta/Elev= 30
-257.579  967.99-246.391  959.06-227.953  958.61-225.197  957.63-216.667  950.25
 -206.43   948.8-179.823  939.82-137.139  939.78 -131.66  938.17-123.228  937.64
 -92.159  938.38 -85.466  937.38 -79.003  934.15 -71.325  932.46  -49.18  935.16
 -35.991  934.95 -27.329  932.52 -22.244  929.07 -19.718  928.02 -14.633  927.92
    -9.8  926.08       0   925.2   23.27  927.51  25.591  929.06  35.499  934.59
  41.962  936.67 119.357  939.63 231.791  941.11 244.357  944.57 269.587  955.99
#Mann= 6 ,-1 , 0
-257.579     .12       0 -79.987     .05       0 -47.703     .12       0
 -22.244    .049       0  25.591     .12       0  44.915     .12       0
#XS Ineff= 2 , 0
          -89.03  939.53
Permanent Ineff=
       F       F
#Block Obstruct= 2 ,-1
-203.182-134.744  967.82-110.892 -87.533  958.44
Bank Sta=-22.244,25.591
XS Rating Curve= 0 ,0
Exp/Cntr=0.3,0.1

Type RM Length L Ch R = 1 ,27023.72,436.89,530.915,564.682
Node Name=BC
XS GIS Cut Line= 3
 594047.947005824384693.07498228   594062.5194944384867.88388044
594068.7496060774384894.96536078
#Sta/Elev= 30
-455.381  965.98-452.854  965.99-432.743  955.98-426.345  953.84-415.125   947.7
-405.118  940.66-399.508  941.72-385.827  940.78-378.642  941.94-365.617  939.42
-346.785  937.85-241.371  933.24 -92.126  933.45 -47.375   932.5  -36.22   933.9
 -22.244  928.01 -19.094  925.97       0   923.2   22.08  925.78  25.492  926.84
  37.369  937.32  49.409  941.93  56.988  940.24     100  942.25 120.636  940.49
 132.677  942.01 146.883  949.47 153.773  951.44 188.058  953.09 211.286  967.99
#Mann= 8 ,-1 , 0
-455.381     .12       0-391.896     .12       0-235.531     .05       0
-184.514     .12       0 -22.244    .049       0   22.08     .12       0
  59.514     .12       0 184.514     .12       0
#Block Obstruct= 1 ,-1
-111.253 -60.827   953.2
Bank Sta=-22.244,22.08
XS Rating Curve= 0 ,0
Exp/Cntr=0.3,0.1

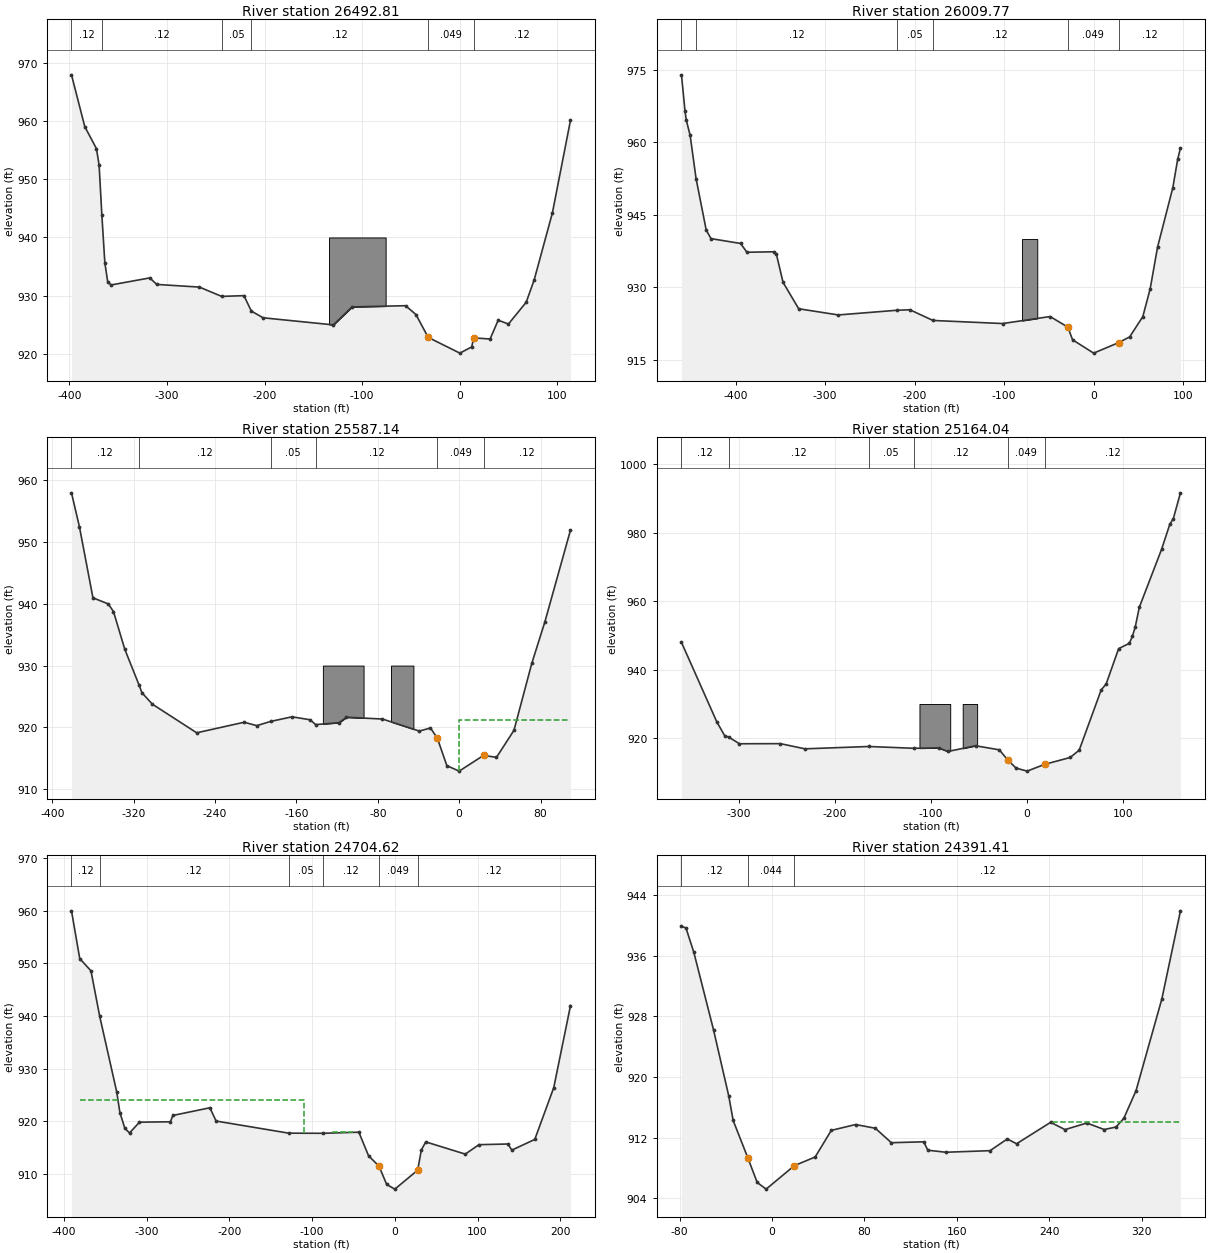
Type RM Length L Ch R = 1 ,26492.81,466.769,483.037,482.553
Node Name=BB
XS GIS Cut Line= 2
593970.5491408634384679.79789412593898.9668599784384818.15271183
#Sta/Elev= 30
-397.736  967.98-384.154  959.08-372.178  955.28-369.455  952.45-366.667  943.94
-363.583  935.66-360.597  932.32-357.152  931.83-317.552  933.04-310.433  931.92
-266.732  931.46 -243.93  929.86-221.096  929.99-213.583  927.34-201.542  926.18
-129.528  924.96  -110.4  928.05  -55.61  928.26 -44.948  926.74 -32.448  922.81
       0   920.1   12.17  921.17  14.108  922.72  30.971  922.53  39.272  925.76
   49.77  925.11  67.979  928.86  76.181  932.73  94.783  944.23  113.32  960.18
#Mann= 6 ,-1 , 0
-397.736     .12       0-366.667     .12       0 -243.93     .05       0
-213.583     .12       0 -32.448    .049       0  14.108     .12       0
#XS Ineff= 2 , 0
         -104.74  927.67
Permanent Ineff=
       F       F
#Block Obstruct= 1 ,-1
    -134     -76     940
Bank Sta=-32.448,14.108
XS Rating Curve= 0 ,0
Exp/Cntr=0.3,0.1

Type RM Length L Ch R = 1 ,26009.77,421.381,422.635,422.365
Node Name=BA
XS GIS Cut Line= 2
593854.9324034344384609.36166125593765.9308023344384754.07155904
#Sta/Elev= 30
  -460.4  973.98-456.398  966.45-454.954  964.56-450.722  961.48-444.094  952.52
-432.743  941.86-427.395  940.09-394.357  939.09-387.303  937.27-357.349  937.37
-354.364  936.87-346.949  931.05-329.462  925.58-285.269   924.3-219.619  925.27
-205.249  925.37-179.495  923.16-101.673  922.52 -48.655  923.97 -28.904  921.79
 -23.524  919.15       0   916.4  27.986  918.58  40.223  919.76  54.888  923.95
  63.156  929.74  71.391  938.36  88.419  950.63  93.865  956.55  96.949  958.82
#Mann= 6 ,-1 , 0
  -460.4     .12       0-444.094     .12       0-219.619     .05       0
-179.495     .12       0 -28.904    .049       0  27.986     .12       0
#Block Obstruct= 1 ,-1
     -80     -63     940
Bank Sta=-28.904,27.986
XS Rating Curve= 0 ,0
Exp/Cntr=0.3,0.1

Type RM Length L Ch R = 1 ,25587.14,434.542,423.097,420.126
Node Name=AZ
XS GIS Cut Line= 2
593734.4906819464384561.60864466593655.1542889654384688.35972622
#Sta/Elev= 30
-381.168  957.99-373.392  952.51-360.072  940.98-345.013  939.99-339.895  938.76
-328.806  932.66-314.665  926.82-311.909   925.6-301.673  923.75-258.071  919.11
 -211.45  920.82-198.983  920.27-185.433  920.95 -164.37   921.7-146.588  921.22
-141.109  920.44 -118.11  920.75-110.794  921.63 -75.394  921.34 -39.206  919.39
 -28.215  919.89 -21.457  918.23   -12.1  913.78       0   912.9  23.983  915.45
   36.68  915.13  53.871  919.51   71.49  930.42  84.219  937.06 109.449  951.96
#Mann= 6 ,-1 , 0
-381.168     .12       0-314.665     .12       0-185.433     .05       0
-141.109     .12       0 -21.457    .049       0  23.983     .12       0
#XS Ineff= 2 , 0
       0  -80.05  921.22               0
Permanent Ineff=
       F       F
#Block Obstruct= 2 ,-1
     -67     -45     930    -134     -94     930
Bank Sta=-21.457,23.983
XS Rating Curve= 0 ,0
Exp/Cntr=0.3,0.1

Type RM Length L Ch R = 1 ,25164.04,453.191,459.422,466.231
BEGIN DESCRIPTION:
2 nd Obstruction block was added to account for the building loacted just d/s of this XS.
END DESCRIPTION:
Node Name=AY
XS GIS Cut Line= 3
593615.4266564744384498.76193188593589.6710561564384541.91246841
593539.3424795344384637.40935759
#Sta/Elev= 30
-359.547     948  -322.9  924.85  -314.6  920.74-310.007  920.28-299.278  918.39
-256.594  918.42-231.102  916.91-164.797  917.59-117.946  917.07 -91.995  917.18
 -82.448  916.13 -53.707  917.81 -28.937  916.62 -20.144  913.65  -11.47  911.28
       0   910.4   18.11  912.37  44.751  914.38  54.134  916.51  77.034  934.11
  82.185  935.84  95.177  946.16 106.332  947.71 109.383   949.7 112.369  952.38
 116.667  958.22 139.829  975.14 148.425  982.47   152.1  984.14 159.482  991.64
#Mann= 6 ,-1 , 0
-359.547     .12       0-310.007     .12       0-164.797     .05       0
-117.946     .12       0 -20.144    .049       0   18.11     .12       0
#Block Obstruct= 2 ,-1
    -112     -80     930     -67     -52     930
Bank Sta=-20.144,18.11
XS Rating Curve= 0 ,0
Exp/Cntr=0.3,0.1

Type RM Length L Ch R = 1 ,24704.62,330.245,313.203,179.976
Node Name=AX
XS GIS Cut Line= 4
593540.7933275524384431.93148305593471.1922466924384488.62733176
593429.8766061814384538.42860437593421.5220380784384566.55859672
#Sta/Elev= 30
-390.781  959.95-380.807  950.88-367.224  948.55-356.759  939.97-336.188  925.61
-332.251  921.63-326.247  918.62-320.637  917.77-308.629  919.81-271.227  919.89
-268.274  921.09-223.524  922.55 -216.01  920.03-128.346  917.73 -86.975   917.7
 -43.471  917.91 -31.759  913.43 -19.226  911.48    -9.8  907.98       0   907.1
  27.625   910.7  32.054  914.54  37.369  916.07  85.138  913.75  101.64  915.54
 136.549  915.67 141.437  914.51 169.127  916.54  192.06  926.37 212.303  941.96
#Mann= 6 ,-1 , 0
-390.781     .12       0-356.759     .12       0-128.346     .05       0
 -86.975     .12       0 -19.226    .049       0  27.625     .12       0
#XS Ineff= 2 ,-1
    -380    -110     924     -75     -50   917.9
Permanent Ineff=
       F       F
Bank Sta=-19.226,27.625
XS Rating Curve= 0 ,0
Exp/Cntr=0.3,0.1

Type RM Length L Ch R = 1 ,24391.41,284.716,284.069,215.434
Node Name=AW
XS GIS Cut Line= 4
593386.7778856484384428.02394701593384.9521336264384438.12501913
593388.6615496724384483.09521169593394.0443177384384559.20377263
#Sta/Elev= 30
 -78.379  939.91 -74.475  939.69 -67.684  936.48 -50.591  926.22 -37.402  917.48
 -33.629  914.27 -20.866  909.31 -12.795  906.08  -5.085   905.2   19.39   908.3
  37.369  909.44  51.378  912.96  72.408  913.73  89.469  913.24 103.346  911.33
 131.365  911.45 134.941  910.34 150.492  910.07 188.812  910.28 203.773  911.83
 211.778  911.19  241.24  914.02 253.707  913.06 272.638  913.93 287.631  913.07
 297.867   913.4 304.626  914.55 315.223  918.21 337.533   930.3 353.675  941.95
#Mann= 3 ,-1 , 0
 -78.379     .12       0 -20.866    .044       0   19.39     .12       0
#XS Ineff= 2 , 0
                          242.89          914.07
Permanent Ineff=
       F       F
Bank Sta=-20.866,19.39
XS Rating Curve= 0 ,0
Exp/Cntr=0.3,0.1

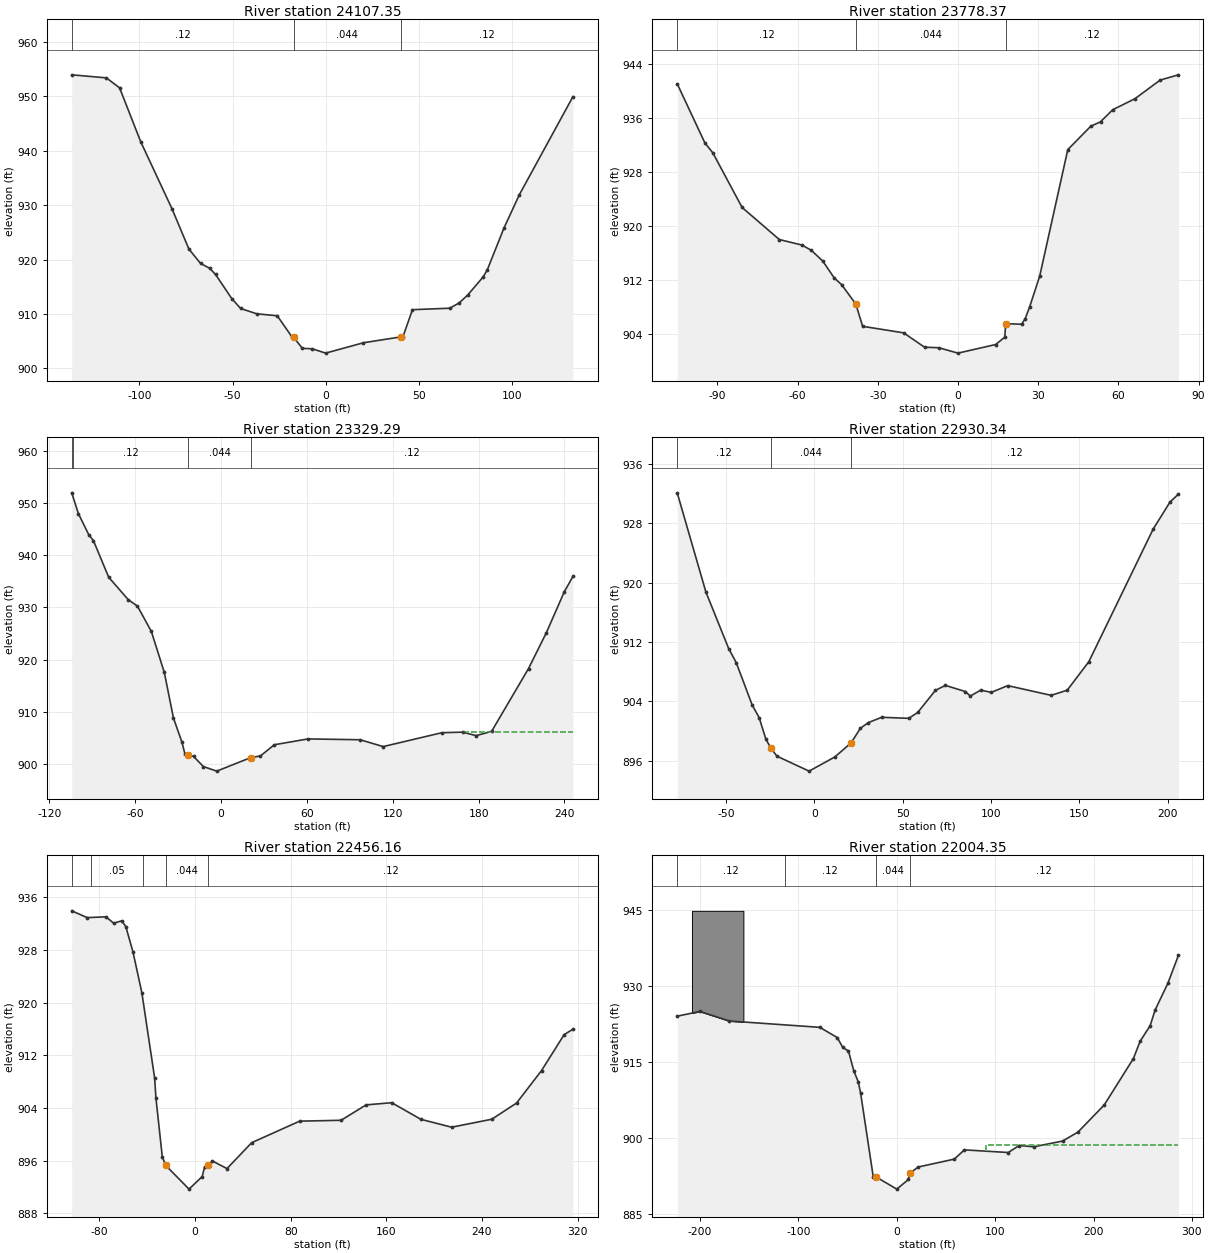
Type RM Length L Ch R = 1 ,24107.35,292.233,328.973,342.787
Node Name=AV
XS GIS Cut Line= 3
593313.4491007424384469.62609952593330.0332689474384524.21273219
593330.170428949 4384549.2246205
#Sta/Elev= 30
-136.385  953.98-117.782  953.42-110.663  951.58 -99.344  941.69 -82.513  929.34
 -73.458  921.95 -67.192   919.3  -62.27   918.4 -59.121  917.26 -50.262  912.76
 -45.636  911.01 -37.008  910.03 -25.984  909.67 -17.913   905.7 -17.224  905.75
  -12.51  903.68    -7.2   903.6       0   902.8   20.34  904.71  40.322  905.78
  41.568  905.84  46.654  910.79  66.699  911.06  71.785  912.04   76.28  913.47
  84.646  916.82  86.844  918.11  95.768  925.78 104.068  931.93 132.841  949.96
#Mann= 3 ,-1 , 0
-136.385     .12       0 -17.224    .044       0  40.322     .12       0
Bank Sta=-17.224,40.322
XS Rating Curve= 0 ,0
Exp/Cntr=0.3,0.1

Type RM Length L Ch R = 1 ,23778.37,467.804,449.08,383.493
Node Name=AU
XS GIS Cut Line= 2
  593245.28667594384471.29945154593223.2008676274384524.00242019
#Sta/Elev= 30
 -105.02  941.08 -94.652  932.29 -91.699  930.83 -80.741  922.72 -66.831  917.96
 -58.333  917.14 -54.823  916.35 -50.525  914.74 -46.293  912.26 -43.537  911.27
 -38.222  908.38 -35.663  905.08  -20.33  904.11  -12.51  901.98    -7.2   901.9
       0   901.1   14.13  902.38   17.52  903.49  17.815  905.47  23.786  905.39
  25.131  906.21  26.837     908  30.577  912.55  41.076  931.31  49.672  934.78
  53.314  935.44  57.874  937.23  66.142  938.85  75.623  941.63  82.448  942.41
#Mann= 3 ,-1 , 0
 -105.02     .12       0 -38.222    .044       0  17.815     .12       0
Bank Sta=-38.222,17.815
XS Rating Curve= 0 ,0
Exp/Cntr=0.3,0.1

Type RM Length L Ch R = 1 ,23329.29,427.235,398.958,353.348
Node Name=AT
XS GIS Cut Line= 2
593101.0065461164384418.42884289593135.8543305474384519.33898013
#Sta/Elev= 30
-104.364     952 -99.672  947.99 -92.487  943.98 -89.206  942.84 -78.543  935.81
 -64.895  931.51 -58.399  930.25  -48.72  925.41 -39.665  917.54 -33.268  908.79
 -27.362  904.18 -25.262  901.92 -22.933  901.76 -19.127  901.41  -12.39  899.48
      -3   898.6  20.866  901.21  27.526  901.51  37.205  903.66  60.761  904.78
  97.277  904.62 113.287  903.31 154.298  905.97 168.734  906.08 178.314  905.41
 189.075  906.23 214.895  918.29 227.297  925.14 239.895  933.02 245.899  935.95
#Mann= 4 ,-1 , 0
-104.364     .05       0-103.642     .12       0 -22.933    .044       0
  20.866     .12       0
#XS Ineff= 2 , 0
                           169.2           906.2
Permanent Ineff=
       F       F
Bank Sta=-22.933,20.866
XS Rating Curve= 0 ,0
Exp/Cntr=0.3,0.1

Type RM Length L Ch R = 1 ,22930.34,497.903,474.175,419.802
Node Name=AS
XS GIS Cut Line= 2
 593000.154320874384510.15230802593071.1087137474384559.61830063
#Sta/Elev= 30
 -77.657  932.13 -61.417  918.75 -48.524  911.13 -44.259  909.24 -35.236  903.53
 -31.266  901.81 -27.461  898.91 -24.508  897.66 -21.227  896.62      -3   894.6
   11.57  896.51  20.801  898.41   26.05  900.38   30.61  901.15  38.123  901.86
  53.445  901.72  58.497  902.51   68.57   905.5   74.18  906.16  85.531  905.33
  88.255  904.72   94.16  905.52 100.164  905.22 109.482  906.13 134.022  904.82
 143.143  905.51 155.413  909.37 191.765  927.22 201.312  930.87 206.102  931.96
#Mann= 3 ,-1 , 0
 -77.657     .12       0 -24.508    .044       0  20.801     .12       0
#XS Ineff= 2 , 0
       0                      74       0   905.5
Permanent Ineff=
       F       F
Bank Sta=-24.508,20.801
XS Rating Curve= 0 ,0
Exp/Cntr=0.3,0.1

Type RM Length L Ch R = 1 ,22456.16,461.471,451.811,423.531
Node Name=AR
XS GIS Cut Line= 3
592930.1539520054384654.53302181593009.2099289824384644.66664568
593056.2405695634384634.59910156
#Sta/Elev= 30
-103.117  933.95  -90.19  932.92 -74.409  933.04 -68.077  932.07 -61.319  932.43
 -57.907  931.57 -51.903  927.72 -44.488  921.54 -33.793  908.59 -32.677  905.51
 -27.395  896.64 -24.573  895.31      -5   891.7       6  893.61   7.972  895.04
  11.155  895.32  14.436  895.98  26.739  894.82  47.375  898.75    87.5  902.02
 122.113  902.15  143.11  904.49 164.501  904.82 188.878   902.3   214.6   901.1
 248.196  902.31  268.93  904.77 289.797   909.7 308.694  915.15 316.043  915.98
#Mann= 5 ,-1 , 0
-103.117     .12       0 -87.402     .05       0  -43.11     .12       0
 -24.573    .044       0  11.155     .12       0
#XS Ineff= 2 , 0
                          195.17          901.97
Permanent Ineff=
       F       F
Bank Sta=-24.573,11.155
XS Rating Curve= 0 ,0
Exp/Cntr=0.3,0.1

Type RM Length L Ch R = 1 ,22004.35,297.061,393.011,396.096
Node Name=AQ
XS GIS Cut Line= 3
592969.7749044954384761.81347913593015.8423770644384768.92446322
593108.9343942144384712.84126253
#Sta/Elev= 30
-223.228     924-200.164  924.93-170.276  923.05 -78.281   921.8 -60.597  919.79
 -54.888  917.83 -49.114  917.12 -43.832  913.28 -39.304   911.1 -36.844  908.88
 -23.852  892.21 -21.588  892.36       0   889.9   11.86  891.81  13.025  892.99
  21.719  894.26   58.53  895.82  68.668  897.64  113.32  897.12 124.344   898.5
 139.436  898.25 168.504  899.38 184.055  901.13 210.728  906.46 240.518  915.65
 247.277  919.03 257.579  922.15 262.598  925.23 275.525  930.47 286.253  935.98
#Mann= 4 ,-1 , 0
-223.228     .12       0-113.583     .12       0 -21.588    .044       0
  13.025     .12       0
#XS Ineff= 2 , 0
                           91.02          898.56
Permanent Ineff=
       F       F
#Block Obstruct= 1 ,-1
-208.235-155.971  944.77
Bank Sta=-21.588,13.025
XS Rating Curve= 0 ,0
Exp/Cntr=0.3,0.1

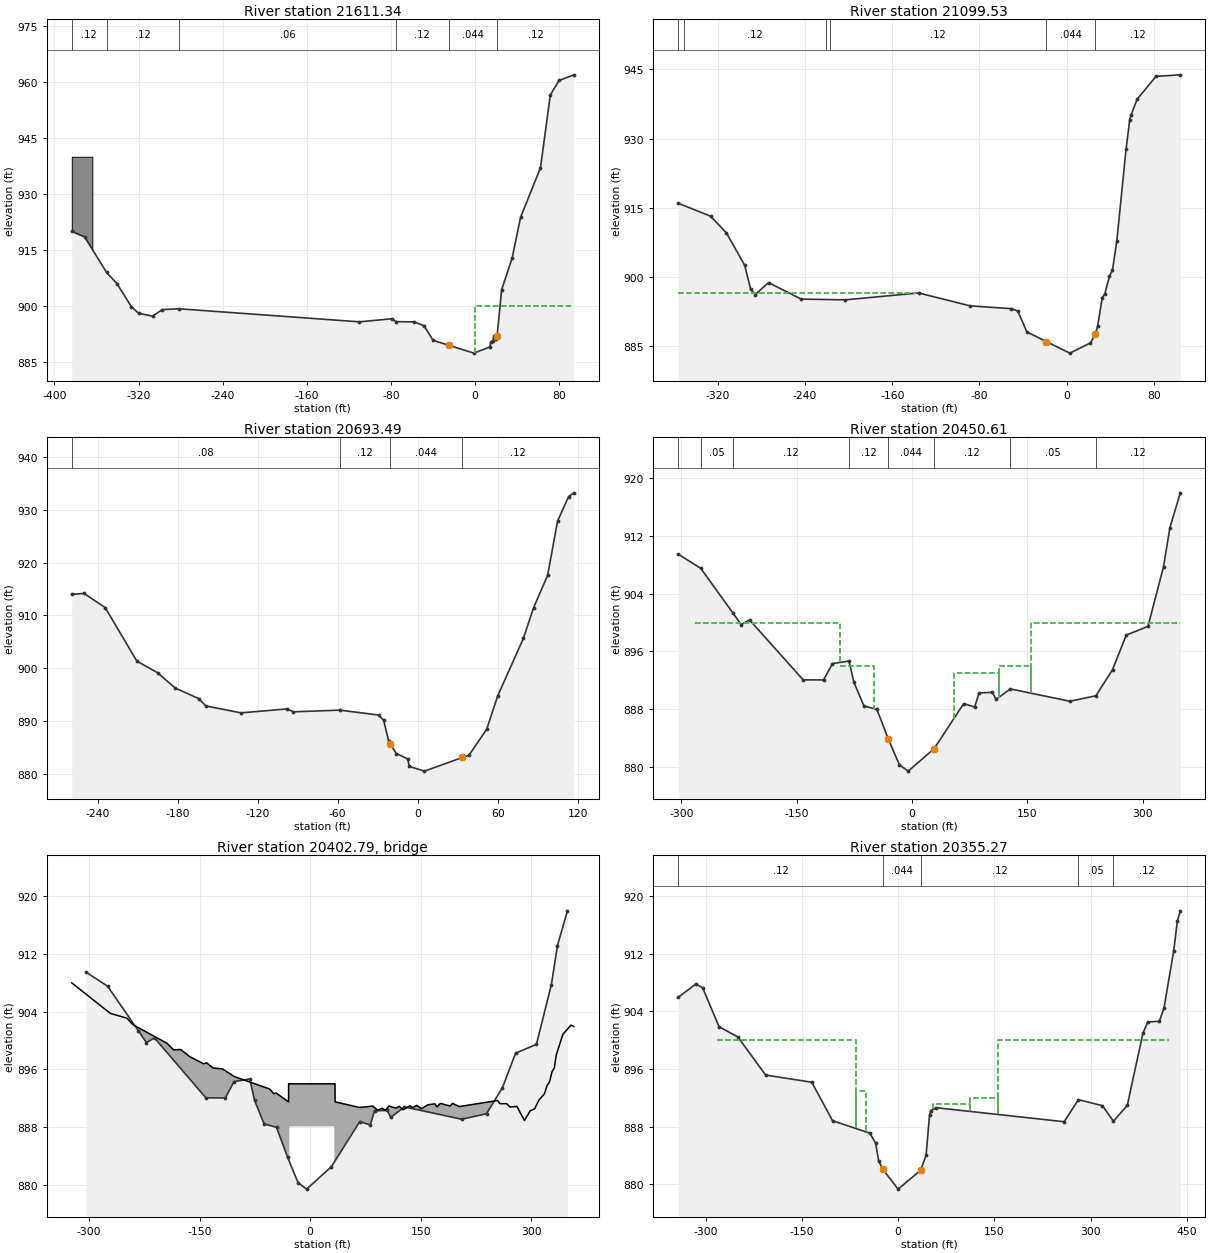
Type RM Length L Ch R = 1 ,21611.34,402.29,511.806,557.183
Node Name=AP
XS GIS Cut Line= 3
593000.2213768714384791.12304749 593041.45167338 4384823.8951439
593132.1510105014384843.99975215
#Sta/Elev= 30
-383.497  919.99-371.358  918.52-350.328  908.94-340.518  905.97-326.837  899.77
-319.816  897.98 -306.66  897.23-297.408  898.98-281.463   899.2-109.843   895.7
  -78.97  896.52 -75.131  895.75 -57.644  895.68 -48.491  894.66 -39.797  890.73
     -25  889.41      -1   887.3   14.14  888.96   15.19  890.36  17.159  890.43
  17.946  891.99  20.472  891.06  21.063  891.98  25.394  904.34    35.4  912.84
  43.406  923.76  62.336  937.04  71.654  956.59  80.052  960.48  94.062  961.99
#Mann= 6 ,-1 , 0
-383.497     .12       0-350.328     .12       0-281.463     .06       0
 -75.131     .12       0     -25    .044       0  21.063     .12       0
#XS Ineff= 2 , 0
       0 -185.72  899.88               0
Permanent Ineff=
       F       F
#Block Obstruct= 1 ,-1
-383.497-363.944     940
Bank Sta=-25,21.063
XS Rating Curve= 0 ,0
Exp/Cntr=0.3,0.1

Type RM Length L Ch R = 1 ,21099.53,392.003,406.038,417.515
Node Name=AO
XS GIS Cut Line= 3
 592975.889192574384806.57945568592990.0258167454384885.90975267
 592975.904432574384944.07168938
#Sta/Elev= 30
-356.365  915.98-326.673  913.18-312.205  909.58-295.407  902.55-289.993  897.44
-285.761   896.2-273.491  898.78-243.504  895.21-203.248  895.05-135.761  896.54
 -88.615  893.75 -50.656  893.14 -44.783  892.61 -36.385  888.08 -18.602  886.01
       3   883.5   21.85  885.71   26.28  887.54   28.51  889.36   32.71  895.51
  35.105  896.36   39.37  900.17  42.126  901.51  46.096  907.82   54.56  927.64
   57.94  934.11  59.055  935.03  64.829  938.57  82.087  943.49 104.364  943.82
#Mann= 6 ,-1 , 0
-356.365     .12       0-350.623     .12       0-220.571     .12       0
 -217.06     .12       0 -18.602    .044       0   26.28     .12       0
#XS Ineff= 2 , 0
         -138.15   896.6
Permanent Ineff=
       F       F
Bank Sta=-18.602,26.28
XS Rating Curve= 0 ,0
Exp/Cntr=0.3,0.1

Type RM Length L Ch R = 1 ,20693.49,195.294,242.886,318.438
Node Name=AN
XS GIS Cut Line= 3
592917.8461278534384797.39278357592901.8319356554384806.25331968
592855.4870950824384890.76521673
#Sta/Elev= 30
-259.318     914-250.098  914.17-234.252  911.49-210.531  901.35-194.947  899.14
-181.857  896.25-164.272  894.26-158.793  892.85-132.448  891.54 -98.064  892.29
 -93.176  891.74 -58.432  892.06 -29.298  891.13 -25.558   890.1 -21.883  886.21
 -20.636  885.59  -16.01  883.82  -7.644  882.83   -6.26  881.38       5   880.5
  33.432  883.09  38.287   883.5  51.575  888.42  59.908  894.79  79.101  905.65
  86.713  911.45  97.277   917.6 104.724  927.88 112.992  932.53 116.929  933.24
#Mann= 4 ,-1 , 0
-259.318     .08       0 -58.432     .12       0 -20.636    .044       0
  33.432     .12       0
Bank Sta=-20.636,33.432
XS Rating Curve= 0 ,0
Exp/Cntr=0.5,0.3

Type RM Length L Ch R = 1 ,20450.61,118.613,95.335,100.164
XS GIS Cut Line= 6
592906.5593837134384794.25334353592882.9800554224384805.22309567
592786.3615022284384825.71479992592760.499221908 4384839.8331361
592745.3567577214384854.03681627592754.6562058364384889.56430471
#Sta/Elev= 30
-303.889  909.48-274.632  907.53-232.919  901.35-222.129  899.72-211.061  900.36
-141.416  892.06-114.903  892.04-103.249  894.31 -81.822  894.67 -75.348  891.71
 -62.399  888.44 -45.505  887.96 -30.583  883.83 -16.266  880.28  -4.698   879.4
  28.918  882.51  67.394  888.76  81.668  888.29  87.434  890.25  104.76  890.32
 109.384  889.34 128.036   890.8 205.543  889.09 239.393  889.85 261.005  893.48
 278.825  898.26 307.065  899.47  327.32  907.74 335.613  913.17 349.147  917.99
#Mann= 8 ,-1 , 0
-303.889     .12       0-274.632     .05       0-232.919     .12       0
 -81.822     .12       0 -30.583    .044       0  28.918     .12       0
 128.036     .05       0 239.393     .12       0
#XS Ineff= 5 ,-1
-281.908 -93.969     900 -93.969 -49.804     894  54.502 112.763     893
 112.763 155.049     894 155.049 375.877     900
Permanent Ineff=
       F       F       F       F       F
Bank Sta=-30.583,28.918
XS Rating Curve= 0 ,0
Skew Angle= 20
Exp/Cntr=0.5,0.3

Type RM Length L Ch R = 3 ,20402.79,,,
BEGIN DESCRIPTION:
Earl L Core Road / STATE ROUTE 7 - Field Recon ID Deck 10
END DESCRIPTION:
Bridge Culvert--1,0,-1,-1, 0
Deck Dist Width WeirC Skew NumUp NumDn MinLoCord MaxHiCord MaxSubmerge Is_Ogee
24,50,2.6,20, 60, 60, , , 0.98, 0, 0,0,,
-323.343-270.932-248.365-240.349-194.259-185.195-175.514-163.398 -144.53-140.492
-131.767-118.849-102.786 -54.815 -49.143 -46.152 -29.224  -29.13 -28.191  32.889
  33.829  33.923  67.333  84.905  91.503  97.823 102.324 106.918  116.66 121.038
 126.064 135.435 138.981 144.746 150.943 159.791 169.349 172.061 176.778 190.066
 193.241 202.521 254.408 257.552 266.739 271.148 280.551 290.818 298.834 304.475
 310.703 317.979 321.524 324.731 328.214 331.389 333.825 342.889 353.988 357.842
     908  903.76   903.1   902.2  899.63  898.71  898.76  897.78  896.78  896.92
   896.2  896.07  895.01  893.28  892.62  892.73   891.5     894     894     894
     894   891.5  890.72  890.92  890.36  890.61  890.34  890.92  890.63  890.89
   890.4  890.96   890.7  891.01  890.55  891.09  891.23   890.8  891.29  890.92
  891.29  890.85  891.69  891.25  891.25  890.78  890.87  888.92  890.29  890.51
  891.78  892.61  893.78  894.21  895.67  896.21  897.94  900.86  902.14  901.96
                                                                                
                                                                   888.1   888.1
                                                                                
                                                                                
                                                                                
                                                                                
-323.343-270.932-248.365-240.349-194.259-185.195-175.514-163.398 -144.53-140.492
-131.767-118.849-102.786 -54.815 -49.143 -46.152 -29.224  -29.13 -28.191  32.889
  33.829  33.923  67.333  84.905  91.503  97.823 102.324 106.918  116.66 121.038
 126.064 135.435 138.981 144.746 150.943 159.791 169.349 172.061 176.778 190.066
 193.241 202.521 254.408 257.552 266.739 271.148 280.551 290.818 298.834 304.475
 310.703 317.979 321.524 324.731 328.214 331.389 333.825 342.889 353.988 357.842
     908  903.76   903.1   902.2  899.63  898.71  898.76  897.78  896.78  896.92
   896.2  896.07  895.01  893.28  892.62  892.73   891.5     894     894     894
     894   891.5  890.72  890.92  890.36  890.61  890.34  890.92  890.63  890.89
   890.4  890.96   890.7  891.01  890.55  891.09  891.23   890.8  891.29  890.92
  891.29  890.85  891.69  891.25  891.25  890.78  890.87  888.92  890.29  890.51
  891.78  892.61  893.78  894.21  895.67  896.21  897.94  900.86  902.14  901.96
                                                                                
                                                                   888.1   888.1
                                                                                
                                                                                
                                                                                
                                                                                
BR Coef=-1 , 0 , 0 ,, 0 ,,,0.8,0,,0,
WSPro=,,,, 1 ,,,, 0 ,,,, 0 ,,,,-1 ,-1 ,-1 , 0 , 0 , 0 , 0 , 0
BC Design=,, 0 ,, 0 ,,,,,,
BC Use User HTab Curves=0
BC User HTab FreeFlow(D)= 0

Type RM Length L Ch R = 1 ,20355.27,514.023,453.039,382.629
XS GIS Cut Line= 6
592896.4369755884384772.49367126592875.7044793324384782.13754338
592777.1504461144384803.40039165592746.3138297334384820.23449585
592721.5915014274384843.42063214592742.6897576884384900.66512085
#Sta/Elev= 30
-342.673  905.96 -315.05  907.83-304.537  907.27-279.072  901.88-249.629  900.45
-206.436  895.16-134.541  894.16-102.139  888.81 -44.272  887.09 -34.899  885.69
 -30.182  883.18 -23.615  882.04       0   879.3  34.992  881.91  43.593  883.98
  48.989  889.55  50.746  890.19  59.378  890.62 258.786  888.67 281.075  891.74
 318.564   890.9 335.582  888.74 357.225  890.94 381.611  900.98 389.041  902.53
   407.2  902.64 414.353  904.43 429.551   912.4 435.193  916.52 439.879  917.99
#Mann= 5 ,-1 , 0
-342.673     .12       0 -23.615    .044       0  34.992     .12       0
 281.075     .05       0 335.582     .12       0
#XS Ineff= 5 ,-1
-281.908 -65.778     900 -65.778 -49.804     893  54.502 112.763   891.2
 112.763 155.049     892 155.049 422.862     900
Permanent Ineff=
       F       F       F       F       F
Bank Sta=-23.615,34.992
XS Rating Curve= 0 ,0
Skew Angle= 20
Exp/Cntr=0.5,0.3

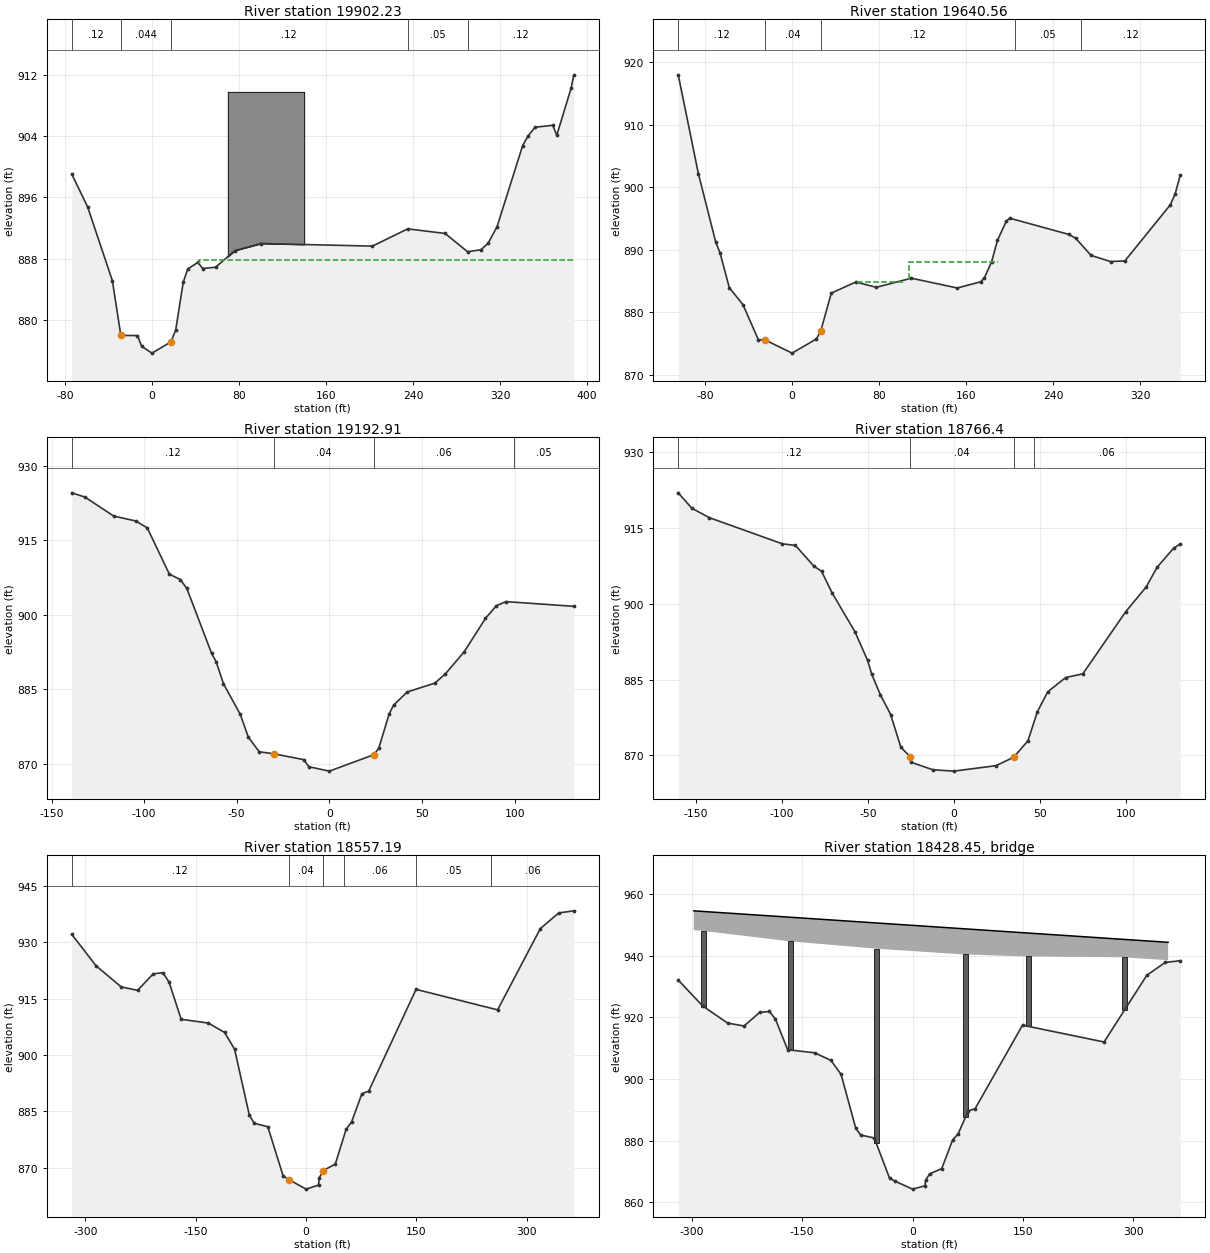
Type RM Length L Ch R = 1 ,19902.23,272.36,261.672,253.224
Node Name=AM
XS GIS Cut Line= 3
592656.7513966264384788.75475146592711.7159813054384846.88316018
 592738.800509644384901.12841685
#Sta/Elev= 30
 -73.688  899.05 -59.055  894.74 -36.385  885.15 -28.609  878.01 -13.386  877.99
   -9.39  876.58       0   875.7  17.388  877.16  21.818  878.71   28.74  884.95
  32.972  886.68  42.224  887.53  46.621  886.73  58.432   886.9   76.28  889.07
 100.328  889.99 202.625  889.65 235.007   891.9 269.423   891.3 290.059  888.91
 302.297  889.18 308.793     890 317.093  892.16 340.617  902.74 345.636  904.02
 352.165  905.15  368.34   905.4 371.982   904.1 385.171  910.23 387.697  911.98
#Mann= 5 ,-1 , 0
 -73.688     .12       0 -28.609    .044       0  17.388     .12       0
 235.007     .05       0 290.059     .12       0
#XS Ineff= 2 , 0
                           43.39          887.84
Permanent Ineff=
       F       F
#Block Obstruct= 1 ,-1
  69.718 139.895  909.76
Bank Sta=-28.609,17.388
XS Rating Curve= 0 ,0
Exp/Cntr=0.3,0.1

Type RM Length L Ch R = 1 ,19640.56,449.802,447.65,446.913
Node Name=AL
XS GIS Cut Line= 3
592596.6539798834384853.46074426592650.9236205544384882.87089663
592716.8914853694384926.22564916
#Sta/Elev= 30
-104.659  917.99 -86.122  902.18 -70.243  891.27 -66.207   889.5  -57.71  883.96
  -45.21  881.26 -31.037  875.65 -24.475  875.58       0   873.5  22.375  875.77
  26.411  877.09  36.056   883.1  58.629  884.87  77.395  884.02 109.613  885.48
 151.804  883.91 173.228   884.9 176.575  885.47 183.333  888.08 188.747  891.52
 196.785  894.57 200.033  895.07 254.101  892.49  260.63  891.88 274.738  889.13
 292.684  888.14 305.873  888.24 347.736  897.23   352.1  898.98 356.824  901.99
#Mann= 5 ,-1 , 0
-104.659     .12       0 -24.475     .04       0  26.411     .12       0
 204.987     .05       0 265.814     .12       0
#XS Ineff= 2 ,-1
   59.35  102.74  884.88  107.73  189.03  888.08
Permanent Ineff=
       F       F
Bank Sta=-24.475,26.411
XS Rating Curve= 0 ,0
Exp/Cntr=0.3,0.1

Type RM Length L Ch R = 1 ,19192.91,421.907,426.509,429.488
Node Name=AK
XS GIS Cut Line= 2
592539.5588431784384976.14884178592612.9059160844385014.16959425
#Sta/Elev= 30
-139.075  924.55-131.955  923.69-116.437  919.87-104.495  918.88 -98.294  917.48
 -86.385  908.17 -80.479  907.08 -76.968   905.3 -63.583  892.21 -61.122  890.54
 -57.185   886.1 -48.064  879.91 -43.766  875.35 -37.861   872.4 -29.921  871.99
 -13.878  870.81  -11.05  869.38       0   868.5   23.95   871.8   26.64  873.08
  32.349   880.1  34.678  881.78  41.962  884.43  56.988  886.23  62.598  888.08
  72.835  892.55  84.285  899.27  90.223  901.83  95.374  902.64 131.988  901.69
#Mann= 4 ,-1 , 0
-139.075     .12       0 -29.921     .04       0   23.95     .06       0
   99.77     .05       0
Bank Sta=-29.921,23.95
XS Rating Curve= 0 ,0
Exp/Cntr=0.3,0.1

Type RM Length L Ch R = 1 ,18766.4 ,205.13,209.212,213.735
Node Name=AJ
XS GIS Cut Line= 2
592463.057090232  4385075.184459592536.8461231444385125.04059562
#Sta/Elev= 30
-160.367  921.88-152.461  918.84-142.257  916.97 -99.738   911.8 -92.224   911.5
 -81.496  907.42 -76.968  906.38 -70.735  902.05  -57.48   894.4 -50.197  888.78
 -47.736  886.01 -42.717  881.96 -36.745  878.07 -30.873  871.66 -25.262  869.68
  -24.83  868.64  -12.17  867.17       0   866.9   24.58  867.98  34.843  869.65
  43.143   872.9  48.622  878.63  54.692  882.59  65.092  885.39  75.066  886.12
  99.967  898.37 112.041  903.33 118.176  907.13 127.854  910.93 131.791   911.8
#Mann= 4 ,-1 , 0
-160.367     .12       0 -25.262     .04       0  34.843     .12       0
  46.391     .06       0
Bank Sta=-25.262,34.843
XS Rating Curve= 0 ,0
Exp/Cntr=0.5,0.3

Type RM Length L Ch R = 1 ,18557.19,213.968,211.322,214.247
XS GIS Cut Line= 4
 592398.978985444385100.45542732592461.2221942094385146.97705189
592541.5156592024385217.77904477592560.9893314424385230.59893293
#Sta/Elev= 30
 -318.57  932.08  -285.4  923.69-251.345  918.11-229.035  917.19-207.907  921.58
-194.652  921.89-186.352   919.4-169.816  909.49 -132.94  908.49 -110.86     906
 -97.211  901.54 -77.264  884.08 -70.604  881.83 -52.034   880.9 -31.201  867.82
 -23.425  866.84       0   864.3      17  865.38  17.684  867.22  23.392  869.25
  39.731  870.97  54.396  880.19  61.975  882.23  75.886  889.68  85.105  890.38
 149.541  917.45   260.4     912  318.57  933.64  343.57  937.79 364.075  938.35
#Mann= 6 ,-1 , 0
 -318.57     .12       0 -23.425     .04       0  23.392     .12       0
  51.214     .06       0 149.672     .05       0 252.001     .06       0
Bank Sta=-23.425,23.392
XS Rating Curve= 0 ,0
Exp/Cntr=0.5,0.3

Type RM Length L Ch R = 3 ,18428.45,,,
BEGIN DESCRIPTION:
US ROUTE 68 - Survey ID  Dec_06X
END DESCRIPTION:
Bridge Culvert--1,0,-1,-1, 0
Deck Dist Width WeirC Skew NumUp NumDn MinLoCord MaxHiCord MaxSubmerge Is_Ogee
23.7,129,2.6,0, 8, 8, , , 0.98, 0, 0,0,,
 -297.39 -283.82  -166.5  -49.31   68.02  157.11  288.21   347.5
  954.52   954.3  952.45  950.59  948.73  947.32  945.25  944.31
  948.25  947.99  944.63  942.25  940.41  939.72  939.45   938.5
 -297.39 -283.82  -166.5  -49.31   68.02  157.11  288.21   347.5
  954.52   954.3  952.45  950.59  948.73  947.32  945.25  944.31
  948.25  947.99  944.63  942.25  940.41  939.72  939.45   938.5
Pier Skew, UpSta & Num, DnSta & Num=  ,-283.8, 2 ,-283.8, 2 , 0 , 0 , 0 ,,
       7       7
     880     955
       7       7
     880     955
Pier Skew, UpSta & Num, DnSta & Num=  ,-166.5, 2 ,-166.5, 2 , 0 , 0 , 0 ,,
       7       7
     880     955
       7       7
     880     955
Pier Skew, UpSta & Num, DnSta & Num=  ,-49.3, 2 ,-49.3, 2 , 0 , 0 , 0 ,,
       7       7
     880     955
       7       7
     880     955
Pier Skew, UpSta & Num, DnSta & Num=  ,72, 2 ,68, 2 , 0 , 0 , 0 ,,
       7       7
     880     955
       7       7
     880     955
Pier Skew, UpSta & Num, DnSta & Num=  ,157.1, 2 ,157.1, 2 , 0 , 0 , 0 ,,
       7       7
     880     955
       7       7
     880     955
Pier Skew, UpSta & Num, DnSta & Num=  ,288.2, 2 ,288.2, 2 , 0 , 0 , 0 ,,
       7       7
     880     955
       7       7
     880     955
BR Coef=-1 , 1 , 1 ,0.9, 0 ,,,0.8,-1,1.2,0,
WSPro=,,,, 1 ,,,, 0 ,,,, 0 ,,,,-1 ,-1 ,-1 , 0 , 0 , 0 , 0 , 0
BC Design=,, 0 ,, 0 ,,,,,,
BC Use User HTab Curves=0
BC User HTab FreeFlow(D)= 0