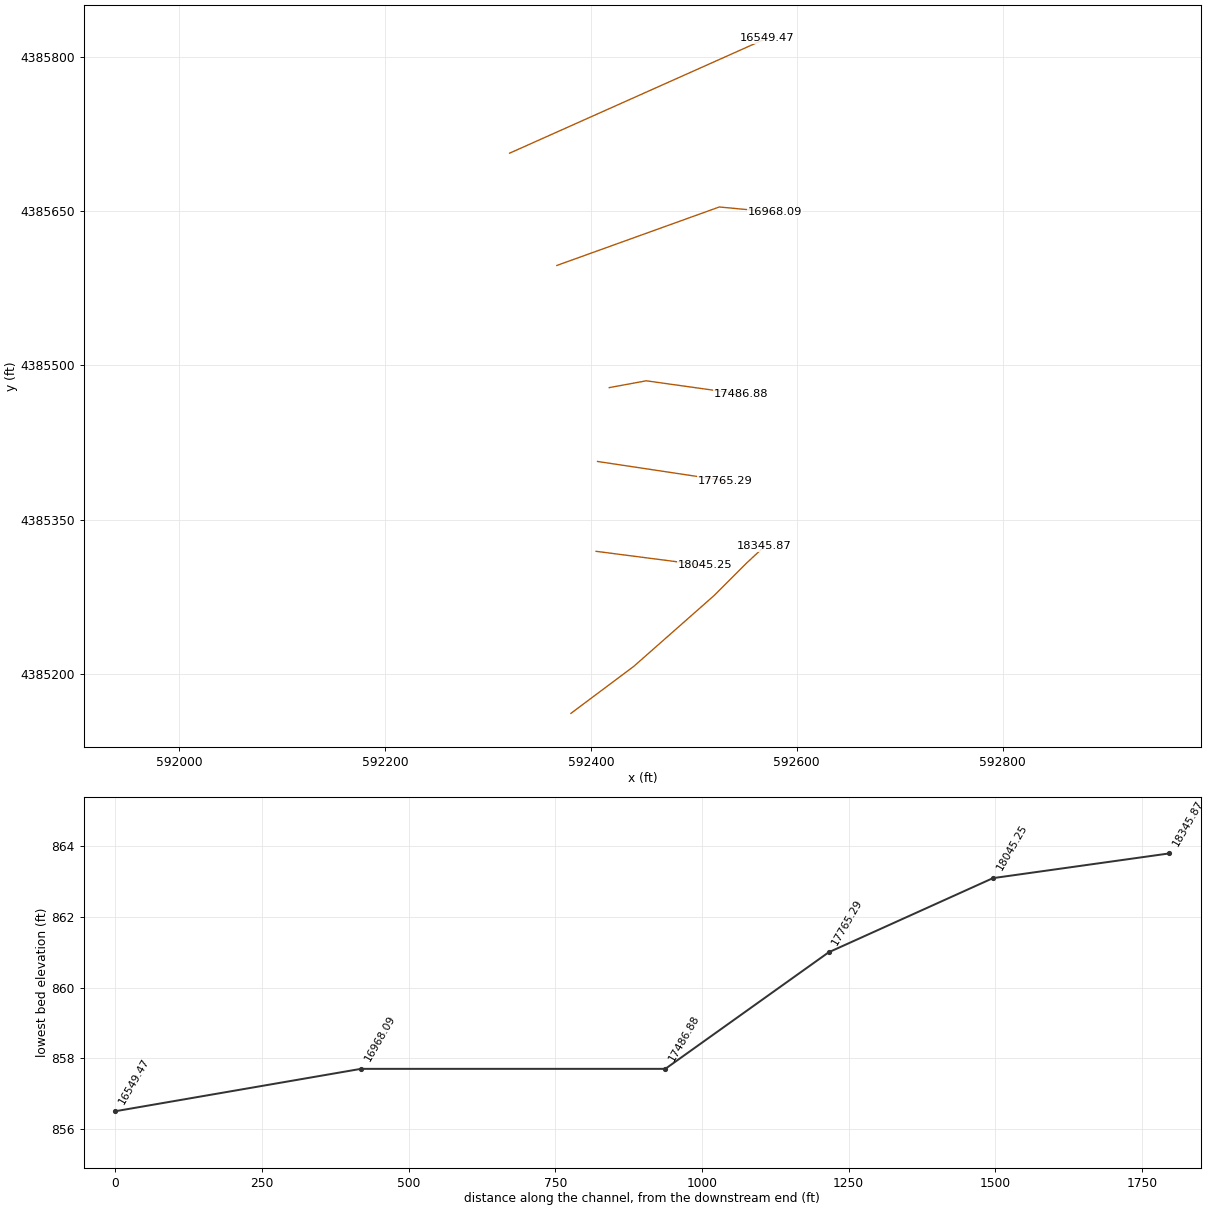
HEC-RAS study Deckers_Creek_Detail_Study.prj: Deckers_Creek_Detail_Study

--- Deckers_Creek_Detail_Study.g01 (geometry) --- (continued)

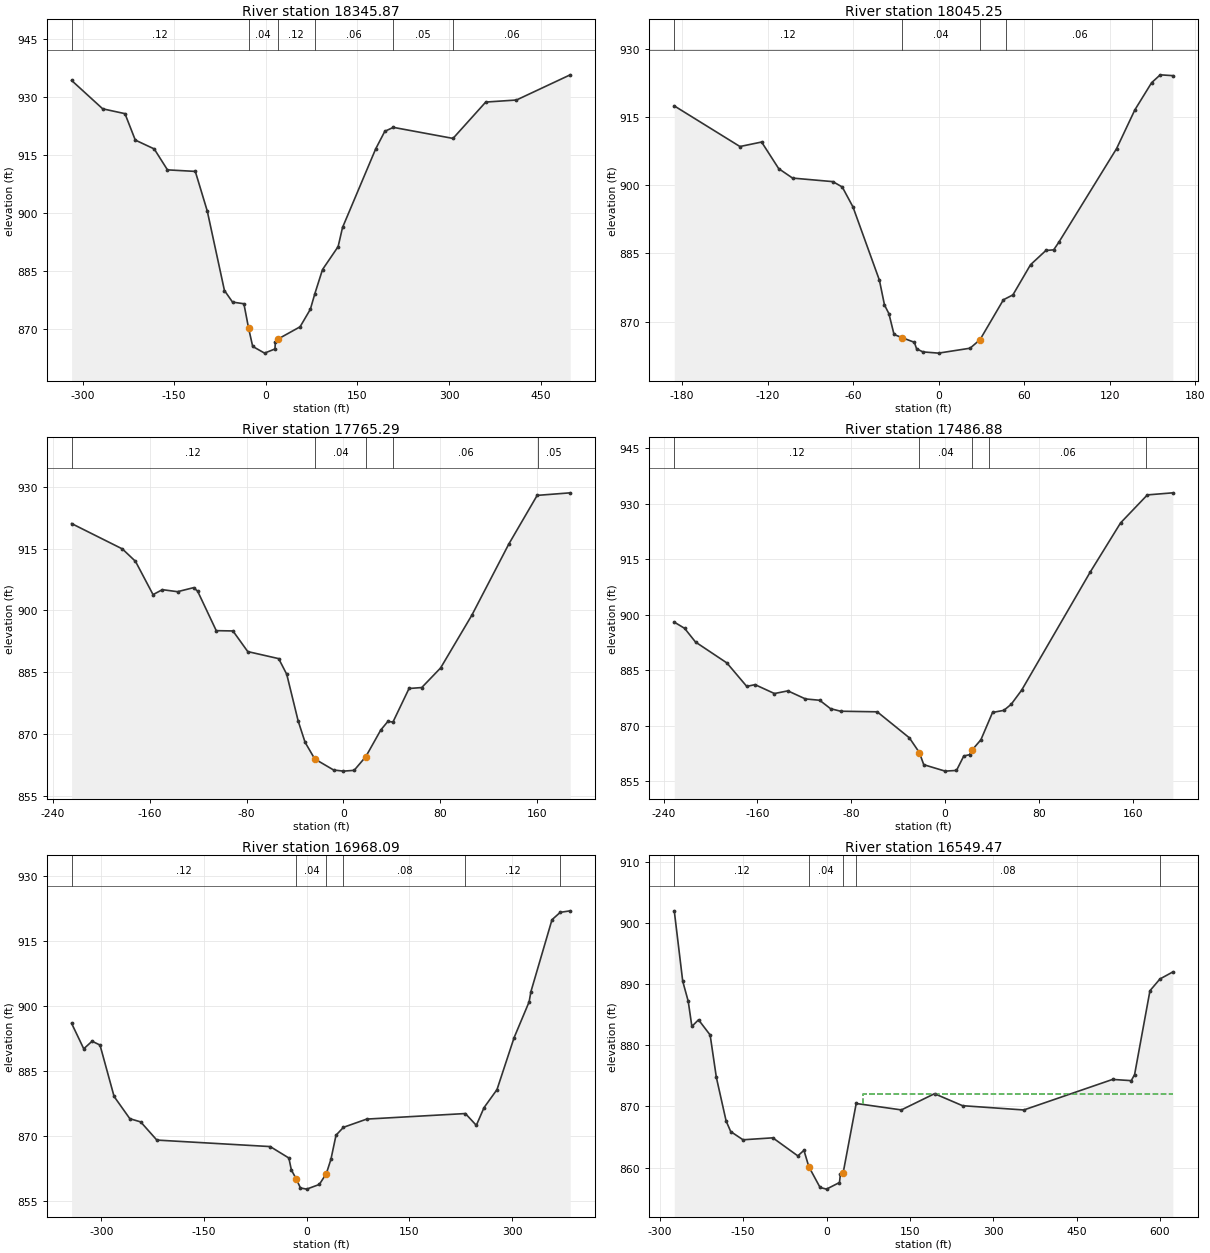
Type RM Length L Ch R = 1 ,18345.87,327.856,300.617,269.174
XS GIS Cut Line= 5
592380.6147852134385162.07989208592441.5625939664385207.63530064
592519.7011229324385276.53534149592550.9400753184385307.77429388
592568.7434435384385324.35541408
#Sta/Elev= 30
-317.881  934.39-266.962  927.04-230.512  925.79-213.615  918.95-182.644  916.66
-160.958  911.24-115.387  910.84 -95.801  900.59 -67.684  880.01 -54.429  877.01
 -35.827  876.58 -28.248  870.33  -21.45  865.54      -2   863.8      15  864.88
  15.684  866.72  19.357  867.39  56.102  870.61  72.966  875.16  80.381  879.22
  92.881  885.44 118.406  891.37 125.623  896.32 179.921  916.68 194.849  921.22
 208.793  922.24 306.463  919.38 360.039  928.79 410.335  929.32 498.327  935.84
#Mann= 6 ,-1 , 0
-317.881     .12       0 -28.248     .04       0  19.357     .12       0
  80.381     .06       0 208.793     .05       0 306.463     .06       0
Bank Sta=-28.248,19.357
XS Rating Curve= 0 ,0
Exp/Cntr=0.5,0.3

Type RM Length L Ch R = 1 ,18045.25,280.656,279.96,279.59
Node Name=AI
XS GIS Cut Line= 2
592405.0719375154385319.46947002592510.8314428224385305.81442986
#Sta/Elev= 30
-185.433  917.41-139.337  908.48-124.147  909.47-112.139  903.62-102.428  901.55
 -74.147  900.77 -67.552  899.59 -60.039  895.21 -41.503  879.13 -37.927  873.67
 -34.843  871.78 -31.234   867.2 -25.787  866.52 -16.995  865.48  -15.38  864.04
  -10.95  863.37       0   863.1   22.12  864.18  29.101  866.06  45.505  874.82
  52.165  875.89  64.534  882.52  75.328  885.65  80.774  885.79  84.416  887.47
 124.934  908.04  137.73  916.53 149.508  922.51 155.545  924.23 164.403  924.05
#Mann= 5 ,-1 , 0
-185.433     .12       0 -25.787     .04       0  29.101     .12       0
  47.671     .06       0     150     .05       0
Bank Sta=-25.787,29.101
XS Rating Curve= 0 ,0
Exp/Cntr=0.3,0.1

Type RM Length L Ch R = 1 ,17765.29,278.168,278.417,278.853
Node Name=AH
XS GIS Cut Line= 2
592406.480113533 4385406.7337111592530.5885790674385388.07995087
#Sta/Elev= 30
-224.508   921.1-182.579  914.94-171.752  911.93-157.251  903.85-149.541  905.05
-137.008  904.56-123.753  905.54 -120.44  904.69-105.052   895.1 -91.273  895.03
 -79.035  890.02  -53.51  888.31  -46.85  884.51 -37.434   873.2 -31.693  867.99
 -23.688  863.95   -8.11  861.27       0     861    8.81  861.19  18.471  864.53
   30.84     871  36.647  873.06  40.879  872.92  54.134  881.06  64.633  881.29
  80.217  886.05 106.037  898.87 136.516  916.12 159.941  927.94 187.238  928.56
#Mann= 5 ,-1 , 0
-224.508     .12       0 -23.688     .04       0  18.471     .12       0
  40.945     .06       0 160.892     .05       0
Bank Sta=-23.688,18.471
XS Rating Curve= 0 ,0
Exp/Cntr=0.3,0.1

Type RM Length L Ch R = 1 ,17486.88,495.993,518.791,531.972
Node Name=AG
XS GIS Cut Line= 3
592417.8430576734385478.45924799592453.8246981184385485.08560007
592545.8590592554385472.18341591
#Sta/Elev= 30
 -230.84  897.97-222.014  896.29 -212.73  892.59-185.991  886.94-169.062   880.6
-161.975  881.07-145.472  878.67 -133.99  879.39-119.029  877.21 -106.89  876.85
 -97.671  874.58 -89.075  873.89 -57.874  873.73 -30.479   866.7 -21.949  862.72
  -18.21  859.44       0   857.7    9.69  857.89  15.912  861.79  20.801  862.14
  22.638  863.28  30.479  866.17   40.42  873.56  50.033  874.12  56.299  875.76
   65.19  879.57 123.622  911.48 149.541  924.79 172.343  932.35 194.094  932.91
#Mann= 5 ,-1 , 0
 -230.84     .12       0 -21.949     .04       0  22.638     .12       0
  37.238     .06       0 171.424     .05       0
Bank Sta=-21.949,22.638
XS Rating Curve= 0 ,0
Exp/Cntr=0.3,0.1

Type RM Length L Ch R = 1 ,16968.09,424.814,418.618,420.472
Node Name=AF
XS GIS Cut Line= 3
592366.9719370454385597.10569745592524.7486109954385653.88993816
592578.8810916644385648.82111409
#Sta/Elev= 30
-343.471     896-325.722  890.12-313.517  891.87-301.969  890.98-281.365   879.1
-258.366  873.97 -242.52  873.23 -218.93  869.03 -53.281  867.53  -26.05  864.89
 -22.375  862.14 -14.895  859.94   -9.13  857.97       0   857.7   18.44  858.78
  28.675  861.27  35.433  864.59  42.881  870.16   53.74  871.98   87.73  873.88
  231.89  875.16 247.867  872.43 259.088  876.52 278.051  880.69 303.051  892.69
 325.033  900.98 327.658  903.34 358.432  919.94 370.472  921.64 385.039  921.99
#Mann= 6 ,-1 , 0
-343.471     .12       0 -14.895     .04       0  28.675     .12       0
   53.74     .08       0  231.89     .12       0 370.472     .05       0
Bank Sta=-14.895,28.675
XS Rating Curve= 0 ,0
Exp/Cntr=0.3,0.1

Type RM Length L Ch R = 1 ,16549.47,452.97,454.819,458.011
Node Name=AE
XS GIS Cut Line= 2
592321.056864477 4385706.1387548592570.7795075634385817.68946018
#Sta/Elev= 30
-273.983  901.96-258.727  890.45-248.852  887.19 -242.29  883.08-230.282  884.16
-209.416  881.68-198.196  874.74-180.643  867.63-172.375   865.9 -150.23  864.56
 -96.588  864.88 -51.608  861.93 -40.617  862.84 -31.824  860.17  -11.56  856.77
       0   856.5   23.35  857.58  25.033  858.98  30.052   859.2  53.445  870.49
 134.711  869.44  194.39  872.09 244.816  870.13  355.02  869.43 514.862  874.42
 548.458  874.22 554.462  875.22 582.087  888.91 600.066  890.83 623.327  891.98
#Mann= 5 ,-1 , 0
-273.983     .12       0 -31.824     .04       0  30.052     .12       0
  53.445     .08       0 600.066     .05       0
#XS Ineff= 2 , 0
       0                      65       0     872
Permanent Ineff=
       F       F
Bank Sta=-31.824,30.052
XS Rating Curve= 0 ,0
Exp/Cntr=0.3,0.1