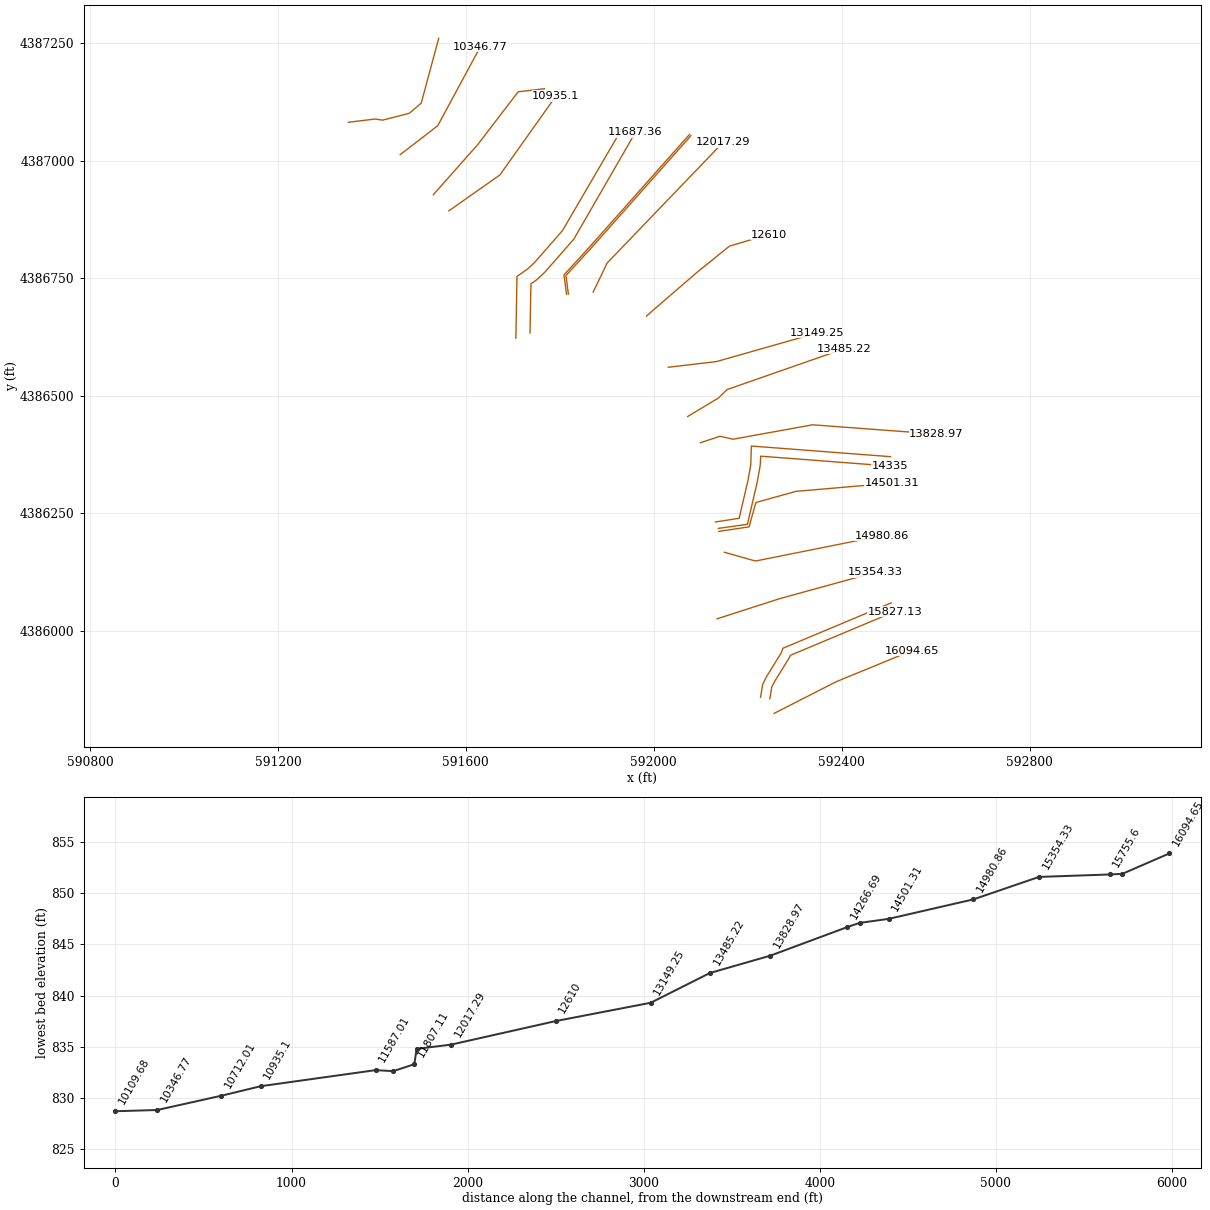
HEC-RAS study Deckers_Creek_Detail_Study.prj: Deckers_Creek_Detail_Study

--- Deckers_Creek_Detail_Study.g01 (geometry) --- (continued)

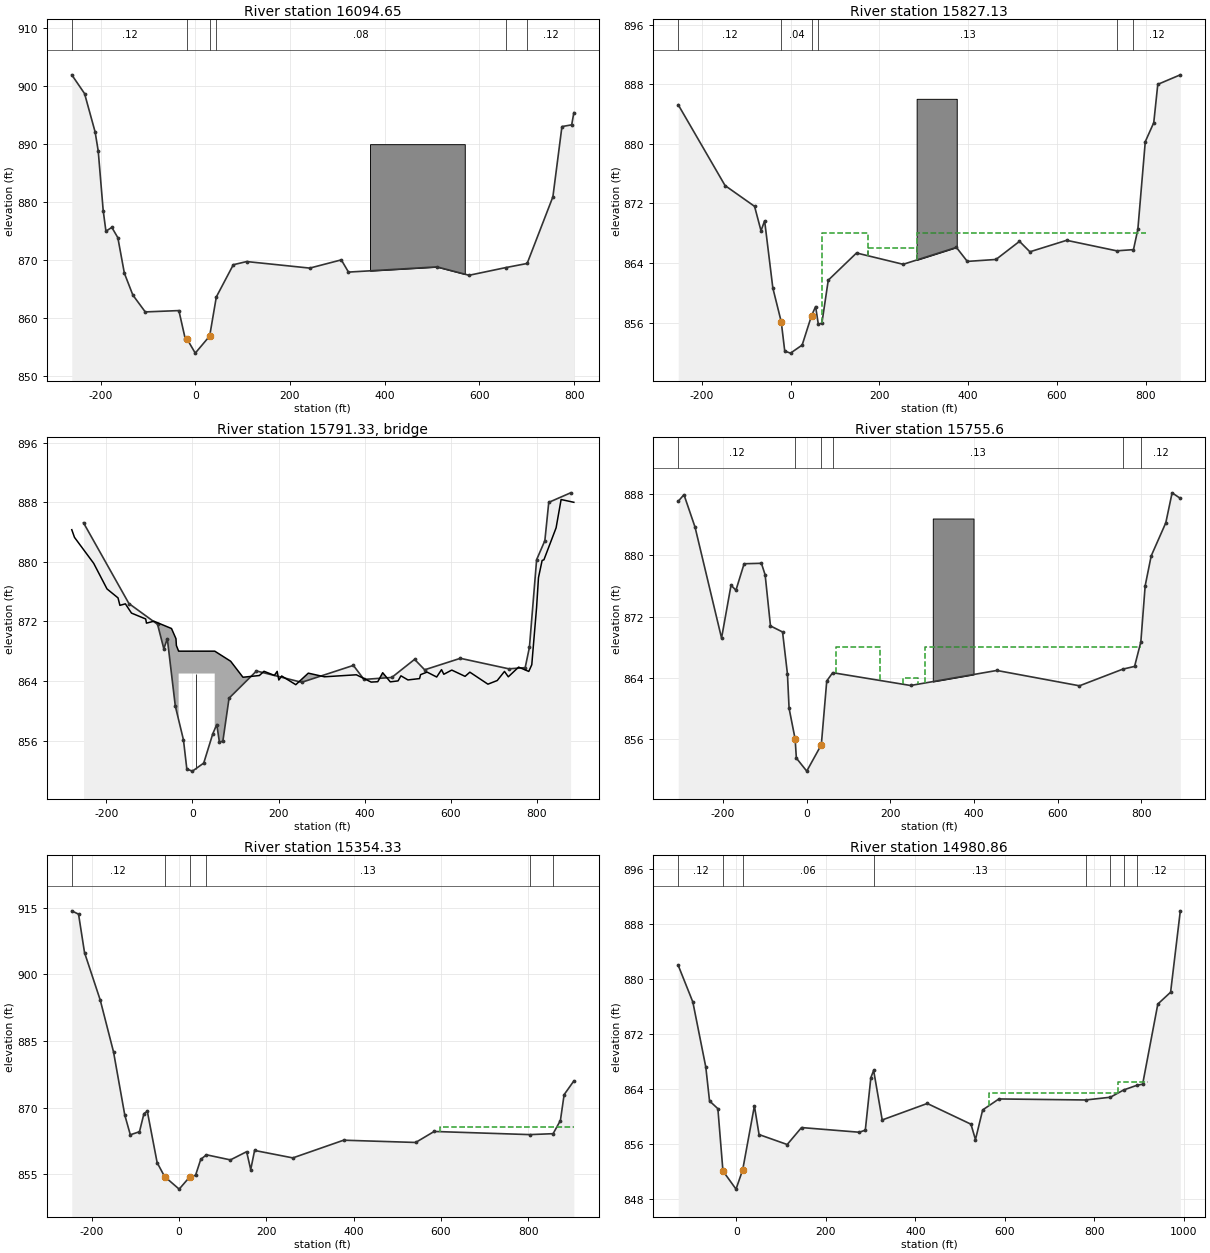
Type RM Length L Ch R = 1 ,16094.65,247.563,267.522,299.536
Node Name=AD
XS GIS Cut Line= 3
592256.2716236764385823.58734025592388.6188333124385891.06091709
592550.0744433074385957.36406191
#Sta/Elev= 30
-260.728  901.98-233.727  898.74-211.417  892.11-204.888  888.83 -194.39  878.54
-188.615  874.96-176.181  875.63-163.451  873.84-149.672  867.71-131.759  863.93
-105.577  861.02  -34.58  861.25 -21.293  856.42 -17.093   856.3       0   853.9
  30.381  856.85  44.488  863.61  80.315  869.17 108.497  869.72 241.732  868.59
 308.333  870.01 323.458   867.9 510.203   868.8 578.117  867.35  655.02  868.67
 700.689  869.39 755.052  880.91 774.147  893.04 794.718  893.34 799.278  895.44
#Mann= 6 ,-1 , 0
-260.728     .12       0 -17.093     .04       0  30.381     .12       0
  44.488     .08       0  655.02     .05       0 700.689     .12       0
#Block Obstruct= 1 ,-1
     369     569     890
Bank Sta=-17.093,30.381
XS Rating Curve= 0 ,0
Exp/Cntr=0.5,0.3

Type RM Length L Ch R = 1 ,15827.13,70.888,71.528,66.669
XS GIS Cut Line= 6
592247.1672475644385854.68608464592251.3521516164385879.78941295
592258.2833037014385893.08783711592289.3393760854385943.20305373
592290.7688881034385947.09534978592513.2606988534386040.40072693
#Sta/Elev= 30
-252.986  885.23-147.474  874.39 -81.004   871.6  -66.47  868.32 -58.333  869.66
 -39.797  860.63 -20.899  856.11  -12.98  852.17       0   851.9   26.22  852.98
  47.375  856.93  56.562  858.15  62.566  855.81  70.604  855.89  85.072  861.69
 148.753  865.34 253.839  863.82 373.753  866.09 398.392  864.21 462.959  864.47
 515.945   866.9  539.37   865.5 622.211  867.04 734.875  865.63 772.802  865.79
 782.644  868.51 799.377  880.28 818.504  882.83 827.559  887.97 878.314  889.25
#Mann= 6 ,-1 , 0
-252.986     .12       0 -20.899     .04       0  47.375     .12       0
  62.566     .13       0 734.875     .05       0 772.802     .12       0
#XS Ineff= 3 ,-1
      70     175     868     284     800     868     175     284     866
Permanent Ineff=
       F       F       F
#Block Obstruct= 1 ,-1
 284.219 374.541  886.03
Bank Sta=-20.899,47.375
XS Rating Curve= 0 ,0
Exp/Cntr=0.5,0.3

Type RM Length L Ch R = 3 ,15791.33,,,
BEGIN DESCRIPTION:
Carnegie Street - Field Recon ID Deck 9
Removed p/w as negative surcharges in floodway
END DESCRIPTION:
Bridge Culvert--1,0,-1,-1, 0
Deck Dist Width WeirC Skew NumUp NumDn MinLoCord MaxHiCord MaxSubmerge Is_Ogee
19.6,20.3,2.6,0, 60, 60, , , 0.98, 0, 0,0,,
-280.249-273.917-229.364-198.392-172.835-168.471-155.741-141.568-108.563-106.759
 -89.567 -48.622 -38.222 -37.303   -32.1     -32   51.75   51.85  88.714 117.323
 155.446 166.175 190.223 196.818 200.623 207.251 240.059 269.094 306.726 380.676
 415.059 430.479 441.863 459.514 477.559 484.219 500.492 527.493 529.856 545.013
  567.29  578.51 583.793 602.297 633.202 644.324 686.253 707.907 724.737 733.596
 757.579 781.135 788.123 799.311 803.675 812.172 816.306 844.587 856.234 885.827
   884.3  883.27  879.79  876.35  875.15  874.15  874.35  873.11  872.32  871.76
  872.02  871.04  869.67  868.76     868     868     868     868  866.65   864.5
  864.73   865.3  864.75  865.29  864.13  864.67   863.5  865.05  864.56  864.83
  863.85   863.9  865.11  863.88  864.01  864.69  864.14  864.32  864.85  865.19
  864.53  865.52   864.9  865.46  864.62  865.18  863.57  864.06  865.28  864.56
  865.86  865.28  866.18  873.87  877.87  880.18  880.26  884.55  888.35  887.98
                                                                                
                                             865     865
                                                                                
                                                                                
                                                                                
                                                                                
-280.249-273.917-229.364-198.392-172.835-168.471-155.741-141.568-108.563-106.759
 -89.567 -48.622 -38.222 -37.303   -37.1     -37   46.75   46.85  88.714 117.323
 155.446 166.175 190.223 196.818 200.623 207.251 240.059 269.094 306.726 380.676
 415.059 430.479 441.863 459.514 477.559 484.219 500.492 527.493 529.856 545.013
  567.29  578.51 583.793 602.297 633.202 644.324 686.253 707.907 724.737 733.596
 757.579 781.135 788.123 799.311 803.675 812.172 816.306 844.587 856.234 885.827
   884.3  883.27  879.79  876.35  875.15  874.15  874.35  873.11  872.32  871.76
  872.02  871.04  869.67  868.76     868     868     868     868  866.65   864.5
  864.73   865.3  864.75  865.29  864.13  864.67   863.5  865.05  864.56  864.83
  863.85   863.9  865.11  863.88  864.01  864.69  864.14  864.32  864.85  865.19
  864.53  865.52   864.9  865.46  864.62  865.18  863.57  864.06  865.28  864.56
  865.86  865.28  866.18  873.87  877.87  880.18  880.26  884.55  888.35  887.98
                                                                                
                                             865     865
                                                                                
                                                                                
                                                                                
                                                                                
Pier Skew, UpSta & Num, DnSta & Num=  ,8.5, 2 ,3.5, 2 , 0 , 0 , 0 ,,
     1.5     1.5
     845     865
     1.5     1.5
     845     865
BR Coef=-1 , 1 , 1 ,1.05, 0 ,,,0.8,-1,1.39,0,
WSPro=,,,, 1 ,,,, 0 ,,,, 0 ,,,,-1 ,-1 ,-1 , 0 , 0 , 0 , 0 , 0
BC Design=,, 0 ,, 0 ,,,,,,
BC Use User HTab Curves=0
BC User HTab FreeFlow(D)= 0

Type RM Length L Ch R = 1 ,15755.6 ,426.112,401.268,380.165
XS GIS Cut Line= 6
 592227.440591324385857.97487668592232.1467033784385886.21154903
592240.8792234864385902.96945324592271.2769278624385952.03920584
592275.0076799084385962.17075797592505.5279227574386058.84417516
#Sta/Elev= 30
-307.349  887.04-293.635   887.9-267.126  883.66 -203.74  869.19 -181.07  876.09
-169.357  875.43-149.803  878.89-108.399  878.95 -99.475  877.43 -86.745  870.78
 -57.841  869.99 -46.161  864.52 -42.224  860.03 -27.756  856.03  -24.83  853.54
       0  851.84  34.875  855.28  47.867   863.6  62.073  864.68 248.327  863.01
 454.659  864.97 652.329  862.97 755.873  865.14 784.121   865.5 799.081  868.69
 809.482  876.02 823.852  879.91 858.793  884.23 873.884  888.14 893.504  887.42
#Mann= 6 ,-1 , 0
-307.349     .12       0 -27.756     .04       0  34.875     .12       0
  62.073     .13       0 755.873     .05       0 799.081     .12       0
#XS Ineff= 3 ,-1
      70     175     868     284     800     868     230     265     864
Permanent Ineff=
       F       F       F
#Block Obstruct= 1 ,-1
 301.476 398.917  884.79
Bank Sta=-27.756,34.875
XS Rating Curve= 0 ,0
Exp/Cntr=0.5,0.3

Type RM Length L Ch R = 1 ,15354.33,392.237,373.474,316.094
Node Name=AC
XS GIS Cut Line= 3
592134.6228941734386024.82544674592269.7072078434386068.24420728
592471.0276103314386123.54711996
#Sta/Elev= 30
-246.063  914.34-230.512  913.58-216.831  904.93-180.774   894.2-150.394  882.54
-124.573  868.29-111.909  863.85 -90.945  864.54 -80.676  868.62 -72.999  869.17
 -50.427  857.57 -33.399  854.44       0   851.6  24.377  854.37  37.533  854.71
  49.442   858.3    62.5  859.34 117.454  858.19 154.659  860.04 163.976  855.99
 172.867  860.32 260.466  858.64  376.87  862.63 541.962  862.12  584.35   864.6
 803.642  863.89  856.89   864.1 873.622  867.07 882.152   872.9 904.429  875.99
#Mann= 6 ,-1 , 0
-246.063     .12       0 -33.399     .04       0  24.377     .12       0
    62.5     .13       0 803.642     .05       0  856.89     .12       0
#XS Ineff= 2 , 0
                           598.5          865.71
Permanent Ineff=
       F       F
Bank Sta=-33.399,24.377
XS Rating Curve= 0 ,0
Exp/Cntr=0.3,0.1

Type RM Length L Ch R = 1 ,14980.86,428.032,479.544,481.298
Node Name=AB
XS GIS Cut Line= 3
592150.5151663694386166.56659249592216.5470391854386147.86711226
592484.7954265014386201.54544093
#Sta/Elev= 30
-130.217     882 -97.539  876.66 -68.602  867.19 -60.236  862.25 -41.568  861.12
 -30.249  852.04      -1   849.4  13.944  852.22  40.092  861.53  50.525  857.35
 113.451   855.9  145.44  858.37 274.573  857.69 288.091  857.99 300.492  865.64
 306.726   866.7 325.853  859.48  426.64  861.88 524.377  858.86 534.416  856.62
 550.558  860.94 586.844  862.54 780.873  862.39 836.089  862.79 865.879  863.85
 895.013  864.52 908.235  864.69 942.224  876.37 970.768  878.09 992.487  889.95
#Mann= 8 ,-1 , 0
-130.217     .12       0 -30.249     .04       0  13.944     .06       0
 306.726     .13       0 780.873     .05       0 836.089     .12       0
 865.879     .05       0 895.013     .12       0
#XS Ineff= 3 ,-1
     320     565   861.4     565     850   863.4     854     920     865
Permanent Ineff=
       F       F       F
Bank Sta=-30.249,13.944
XS Rating Curve= 0 ,0
Exp/Cntr=0.3,0.1

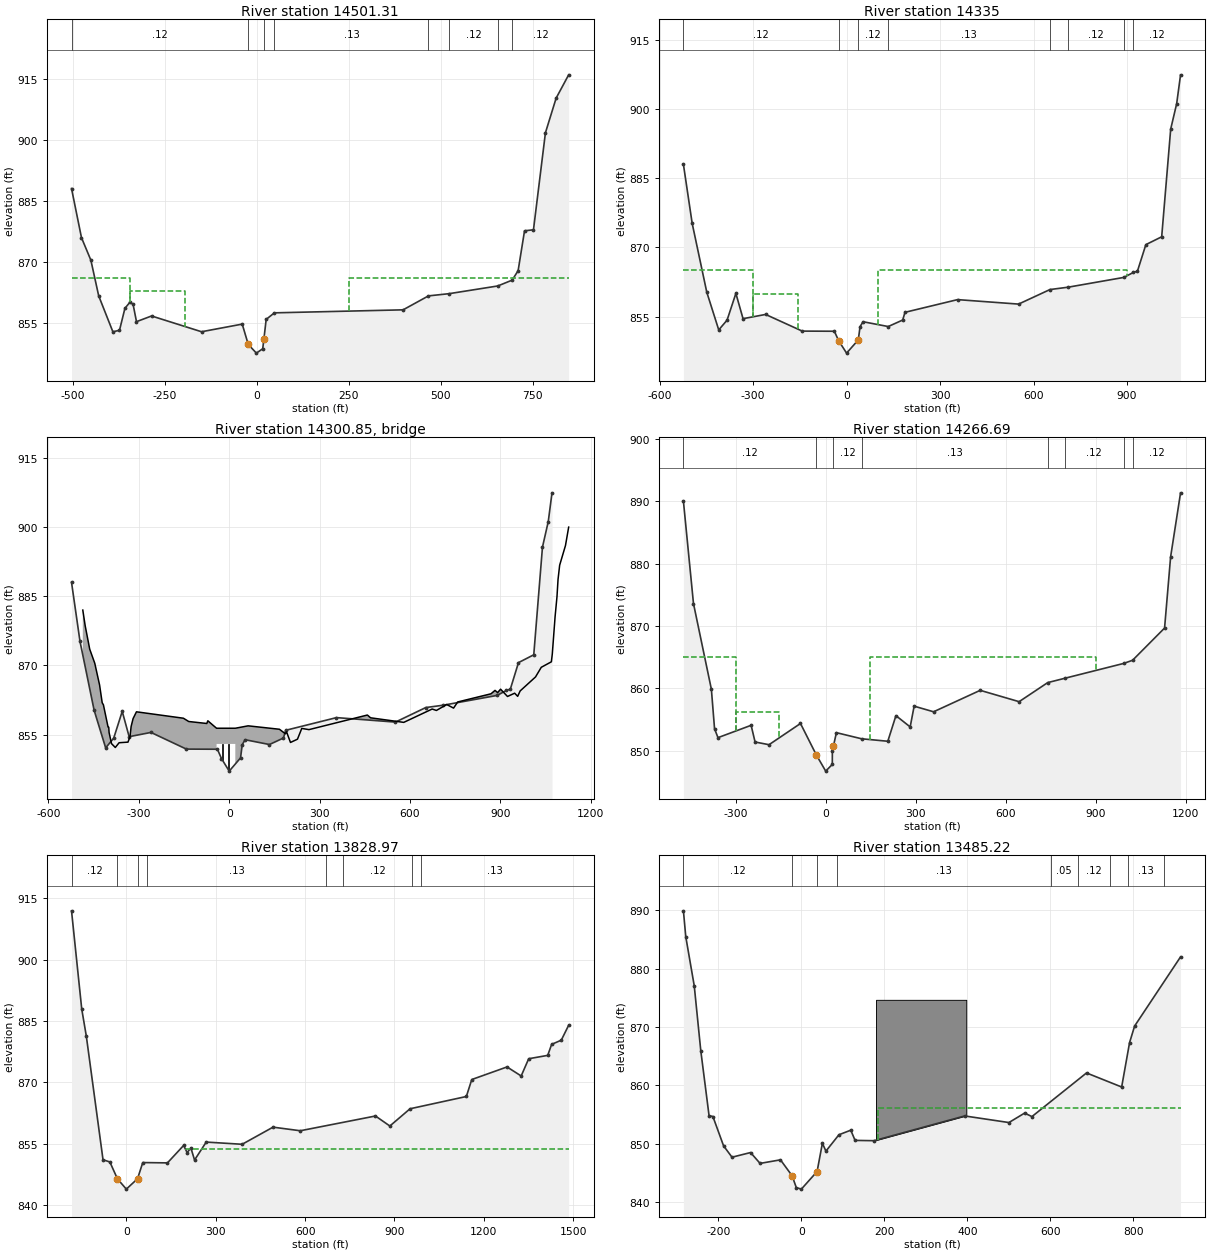
Type RM Length L Ch R = 1 ,14501.31,107.871,166.308,271.747
Node Name=AA
XS GIS Cut Line= 5
592138.7712222244386210.99119304592203.0047750184386220.59544116
592217.473631197 4386272.4144898 592302.683520254386296.16450609
592506.4636587694386313.74841831
#Sta/Elev= 30
-503.314  887.99-476.247   875.9-450.755  870.37-429.495  861.59-390.978  852.76
-372.966  853.11-358.235  858.52-344.193  860.07-335.991  859.48-326.772  855.24
-285.827  856.64-150.066  852.76 -39.501  854.64 -23.097  849.64      -1   847.5
   16.21  848.58  19.455  850.99  25.591   855.8  47.966  857.41 397.638  858.15
 466.601  861.58 522.966  862.13 654.823  864.02 693.865  865.45 710.203  867.78
 727.625  877.59 751.903  877.84 784.416  901.71  813.55  910.24 847.539  915.96
#Mann= 8 ,-1 , 0
-503.314     .12       0 -23.097     .04       0  19.455     .12       0
  47.966     .13       0 466.601     .05       0 522.966     .12       0
 654.823     .05       0 693.865     .12       0
#XS Ineff= 3 ,-1
     250     900     866    -550    -345     866    -345    -195   862.9
Permanent Ineff=
       F       F       F
Bank Sta=-23.097,19.455
XS Rating Curve= 0 ,0
Exp/Cntr=0.5,0.3

Type RM Length L Ch R = 1 ,14335   ,66.349,68.314,68.861
XS GIS Cut Line= 6
 592137.612982214386217.37370512592199.4873829754386226.04221723
592220.0034712284386314.34582632592226.5261913094386350.69627477
592227.8124473254386371.08434702592502.6902347224386350.08362676
#Sta/Elev= 30
-523.524  887.99-495.341  875.18-448.556   860.3-410.171  852.13-383.399  854.25
-355.184  860.04-332.218  854.56 -259.81  855.48 -142.29  851.87 -39.206  851.84
 -25.689  849.82       0   847.1  37.631  849.97  43.241  852.83  52.822   853.9
 133.596  852.86 180.085  854.27 187.402  855.94  356.07  858.69 551.837  857.72
 652.526  860.87 710.728  861.38   889.6   863.5 920.013  864.57 933.202  864.85
 960.269   870.61011.056   872.31039.928  895.621059.153  901.151071.588  907.38
#Mann= 8 ,-1 , 0
-523.524     .12       0 -25.689     .04       0  37.631     .12       0
 133.596     .13       0 652.526     .05       0 710.728     .12       0
   889.6     .05       0 920.013     .12       0
#XS Ineff= 3 ,-1
     100     900     865    -550    -300     865    -300    -155     860
Permanent Ineff=
       F       F       F
Bank Sta=-25.689,37.631
XS Rating Curve= 0 ,0
Exp/Cntr=0.5,0.3

Type RM Length L Ch R = 3 ,14300.85,,,
BEGIN DESCRIPTION:
CSX Transport Footbridge - Field Recon ID Deck 8
END DESCRIPTION:
Bridge Culvert--1,0,-1,-1, 0
Deck Dist Width WeirC Skew NumUp NumDn MinLoCord MaxHiCord MaxSubmerge Is_Ogee
27.7,9.83,2.6,0, 60, 60, , , 0.98, 0, 0,0,,
-486.089 -478.15-463.156-446.358-430.348-421.654-417.618-402.231-399.967-398.786
-390.814-378.215-365.551-336.122-329.462-325.656-319.094 -307.94  -152.1-134.514
 -74.475 -70.965   -42.1     -42   20.25   20.25  62.795 166.732 186.483  190.42
 203.346 226.575 240.846 264.764 458.629 469.291 579.429 673.753 687.828 721.982
 744.783 758.497 869.029 882.415 891.109 900.853 923.786 947.605 957.579 965.846
1016.8641035.9581069.4881072.5721081.8241088.1231091.6011097.0141116.3061126.903
  881.98  878.58  873.52  870.47  865.75   861.9  861.46  856.65  856.61  855.46
  853.06  852.22  853.25  853.38  854.55  856.78  858.49  859.95  858.56  857.85
  857.42     858  856.39  856.39  856.39  856.39  856.91  856.17  855.19  855.59
  853.31  854.02  856.35  856.09  859.25  858.65  857.66  860.55  860.24  861.53
  860.75  862.08  863.85  864.59  864.11  864.85  863.27  863.98   863.3  864.47
   867.5  869.59  870.78  872.47  880.56  884.89  888.61  891.71  895.96  899.95
                                                                                
                                                                                
                          852.99  852.99
                                                                                
                                                                                
                                                                                
-486.089 -478.15-463.156-446.358-430.348-421.654-417.618-402.231-399.967-398.786
-390.814-378.215-365.551-336.122-329.462-325.656-319.094 -307.94  -152.1-134.514
 -74.475 -70.965   -42.1     -42   20.25   20.25  62.795 166.732 186.483  190.42
 203.346 226.575 240.846 264.764 458.629 469.291 579.429 673.753 687.828 721.982
 744.783 758.497 869.029 882.415 891.109 900.853 923.786 947.605 957.579 965.846
1016.8641035.9581069.4881072.5721081.8241088.1231091.6011097.0141116.3061126.903
  881.98  878.58  873.52  870.47  865.75   861.9  861.46  856.65  856.61  855.46
  853.06  852.22  853.25  853.38  854.55  856.78  858.49  859.95  858.56  857.85
  857.42     858  856.39  856.39  856.39  856.39  856.91  856.17  855.19  855.59
  853.31  854.02  856.35  856.09  859.25  858.65  857.66  860.55  860.24  861.53
  860.75  862.08  863.85  864.59  864.11  864.85  863.27  863.98   863.3  864.47
   867.5  869.59  870.78  872.47  880.56  884.89  888.61  891.71  895.96  899.95
                                                                                
                                                                                
                          852.99  852.99
                                                                                
                                                                                
                                                                                
Pier Skew, UpSta & Num, DnSta & Num=  ,-22, 2 ,-22, 2 , 0 , 0 , 0 ,,
       3       3
     843     856
       3       3
     843     856
Pier Skew, UpSta & Num, DnSta & Num=  ,-1.25, 2 ,-1.25, 2 , 0 , 0 , 0 ,,
       3       3
     843     856
       3       3
     843     856
BR Coef=-1 , 1 , 1 ,1.25, 0 ,,,0.8,0,2,0,
WSPro=,,,, 1 ,,,, 0 ,,,, 0 ,,,,-1 ,-1 ,-1 , 0 , 0 , 0 , 0 , 0
BC Design=,, 0 ,, 0 ,,,,,,
BC Use User HTab Curves=0
BC User HTab FreeFlow(D)= 0

Type RM Length L Ch R = 1 ,14266.69,499.271,437.719,231.893
XS GIS Cut Line= 6
592131.4773581344386231.00740929592181.8699427574386238.86515339
592200.4779829874386318.72885037592206.656279063 4386353.1803948
592207.8114710784386392.67028329592504.2111867414386370.02364301
#Sta/Elev= 30
-474.049     890-440.486  873.57-380.873  859.83-370.341   853.5-358.924  852.07
-248.491  854.05-235.302  851.37-188.812  850.94 -84.022  854.34 -31.168  849.29
       0   846.7      22  847.78  22.146  849.98  25.656   850.7  35.597  852.87
 119.521  851.89  206.89  851.49 233.957   855.6  281.43  853.79 294.587  857.12
 359.416  856.22 514.731  859.66 644.291  857.84 739.633   860.9 797.867  861.61
 992.257  863.971022.277  864.481128.937  869.651149.081  881.081182.185  891.34
#Mann= 8 ,-1 , 0
-474.049     .12       0 -31.168     .04       0  25.656     .12       0
 119.521     .13       0 739.633     .05       0 797.867     .12       0
 992.257     .05       01022.277     .12       0
#XS Ineff= 3 ,-1
     148     900     865    -550    -300     865    -300    -155  856.18
Permanent Ineff=
       F       F       F
Bank Sta=-31.168,25.656
XS Rating Curve= 0 ,0
Exp/Cntr=0.5,0.3

Type RM Length L Ch R = 1 ,13828.97,263.423,343.754,384.018
Node Name=Z
XS GIS Cut Line= 5
 592099.567845744386399.71421137592141.0633182534386413.50031555
592168.9098465974386407.22448347 592338.268920694386437.86602785
592601.747187946 4386418.2247156
#Sta/Elev= 30
-183.957  911.98-149.705  887.96-134.285  881.33 -78.215  851.08 -55.315  850.55
 -29.823  846.41       0   843.9  37.631  846.44  55.184   850.4 138.058  850.32
 192.257  854.58 204.035  852.85 216.765  853.96  228.97  851.02 268.143  855.41
 388.747  854.87 492.388  859.06 583.858  858.18  836.22  861.79 884.482  859.34
 952.329  863.56 1141.24  866.561159.449  870.711277.723  873.791325.262  871.58
1350.492   875.81414.337  876.621427.461  879.311459.875  880.341484.646  883.99
#Mann= 8 ,-1 , 0
-183.957     .12       0 -29.823     .04       0  37.631     .12       0
  70.112     .13       0 669.521     .05       0 726.214     .12       0
 959.383     .05       0 989.239     .13       0
#XS Ineff= 2 , 0
                          200.49          853.71
Permanent Ineff=
       F       F
Bank Sta=-29.823,37.631
XS Rating Curve= 0 ,0
Exp/Cntr=0.3,0.1

Type RM Length L Ch R = 1 ,13485.22,330.978,335.965,249.96
Node Name=Y
XS GIS Cut Line= 4
592072.3613974044386455.52918806592137.3051342064386494.60150055
592156.3307504414386512.88035677 592404.596449514386599.56547784
#Sta/Elev= 30
-284.186  889.89-278.478  885.44-258.104  877.05-242.356  865.93-222.408   854.8
-213.123  854.64-187.434  849.62-167.126  847.67-122.375  848.47 -99.475  846.61
 -50.295  847.22 -22.375   844.5  -12.17  842.47       0   842.2  37.959  845.22
  50.689  850.06  59.219  848.71  90.617  851.52 119.094   852.3 129.495  850.55
 175.197   850.5 393.701  854.74 500.164  853.61 538.025  855.23 555.643  854.63
 687.172  862.11  771.85   859.7 790.912  867.31 803.084  870.15 913.779     882
#Mann= 9 ,-1 , 0
-284.186     .12       0 -22.375     .04       0  37.959     .12       0
  85.991     .13       0 600.394     .05       0 666.535     .12       0
 742.979     .05       0 787.402     .13       0 874.541     .12       0
#XS Ineff= 2 , 0
                          184.67          856.03
Permanent Ineff=
       F       F
#Block Obstruct= 1 ,-1
 179.987 397.375  874.64
Bank Sta=-22.375,37.959
XS Rating Curve= 0 ,0
Exp/Cntr=0.3,0.1

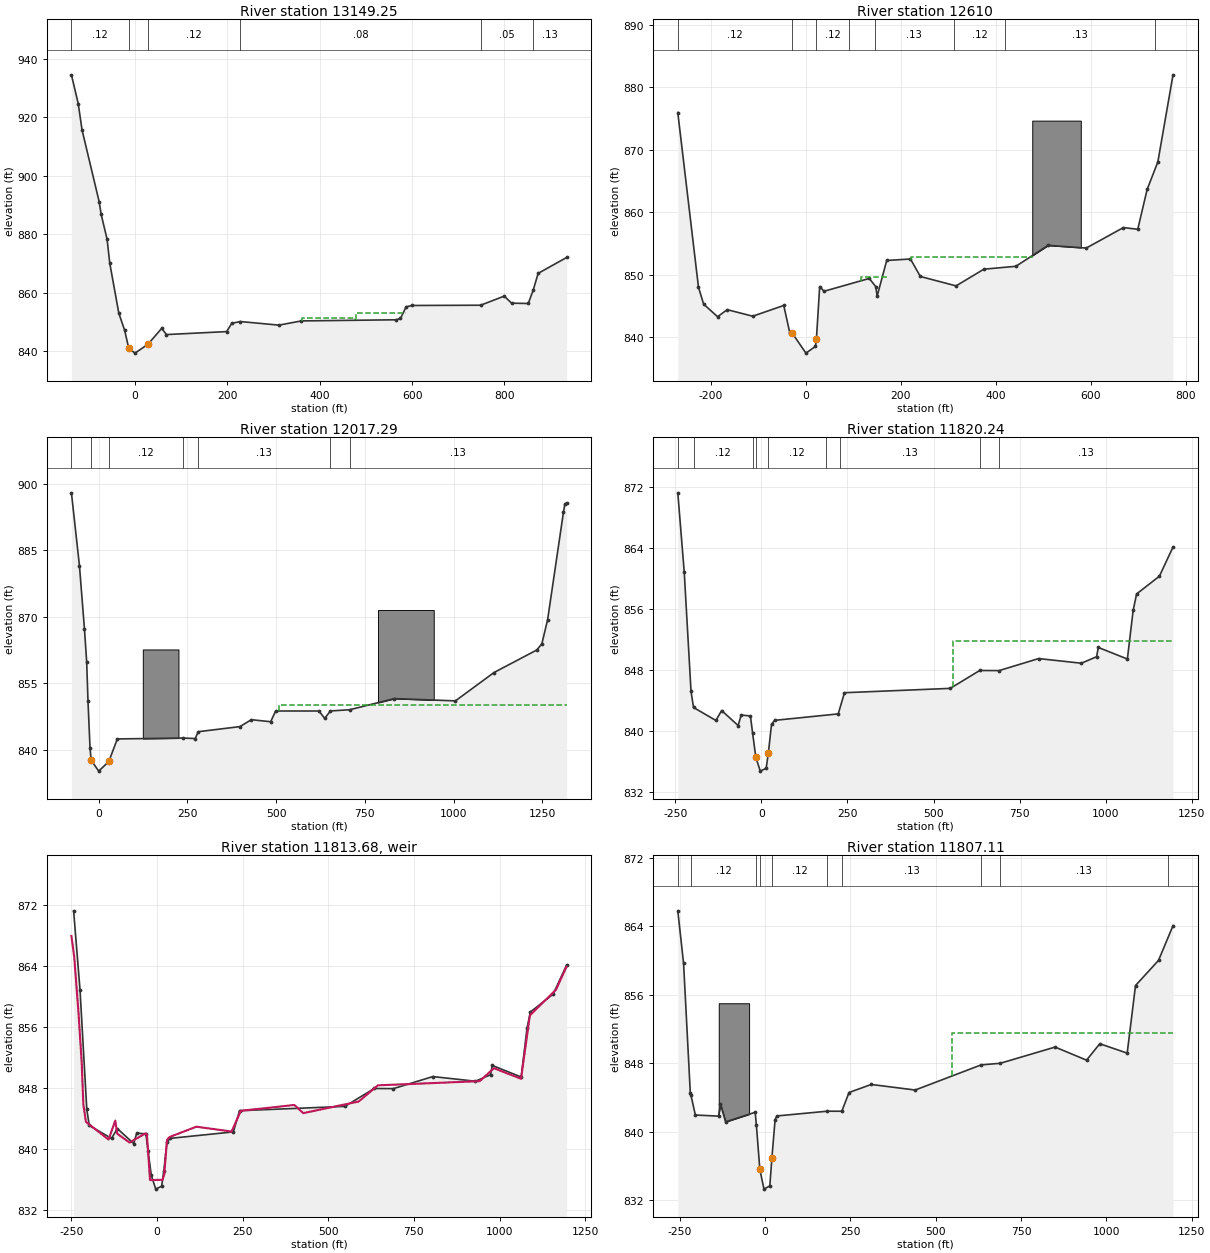
Type RM Length L Ch R = 1 ,13149.25,483.515,539.25,604.054
Node Name=X
XS GIS Cut Line= 3
592031.0305168934386560.41391736592133.1720461554386572.37426951
592348.6717448184386633.55982227
#Sta/Elev= 30
-137.762  934.44-123.097  924.63-114.731  915.57 -77.822  891.13 -73.392  886.76
 -60.564  878.23 -54.692  869.99 -35.138  852.93 -22.507  847.09 -13.747  841.01
   -.131  839.29   27.92  842.32  57.644  847.74  68.077  845.64 198.327  846.65
 209.482  849.48 227.854  850.09 311.581  848.86 360.105   850.3 565.026  850.69
 574.737  851.13 587.073  855.13 599.738  855.58  748.36  855.67 799.573  858.79
 815.354  856.37 851.444  856.26 862.139   860.8   872.9  866.56 934.613     872
#Mann= 6 ,-1 , 0
-137.762     .12       0 -13.747     .04       0   27.92     .12       0
 227.854     .08       0  748.36     .05       0 862.139     .13       0
#XS Ineff= 2 ,-1
  362.45  475.56  851.23  479.29  587.02  852.89
Permanent Ineff=
       F       F
Bank Sta=-13.747,27.92
XS Rating Curve= 0 ,0
Exp/Cntr=0.3,0.1

Type RM Length L Ch R = 1 ,12610   ,485.899,592.714,540.489
Node Name=W
XS GIS Cut Line= 5
591984.755780321 4386669.1147427591988.8279083714386673.16248675
592091.7984936444386762.13970385592161.2837505034386818.23509655
 592244.460623534386842.95437685
#Sta/Elev= 30
-269.849  875.96 -226.28  848.03 -215.42  845.33-186.089  843.32-165.748  844.45
-112.008   843.4 -46.686  845.12 -33.924  840.73 -29.692  840.79       0   837.5
   20.08  838.58  22.113  839.78   28.97  848.14  38.123  847.39 133.465  849.44
 147.113  848.13 149.967   846.6 170.144  852.31 220.112  852.55 241.043  849.75
 316.175  848.25 374.803  850.92 442.257  851.38 509.974  854.73 590.518   854.3
 668.602  857.57 698.885   857.3 718.602  863.66  741.24  868.08  773.13  881.99
#Mann= 8 ,-1 , 0
-269.849     .12       0 -29.692     .04       0  22.113     .12       0
  91.437     .12       0  145.21     .13       0 311.483     .12       0
 419.882     .13       0 734.416     .12       0
#XS Ineff= 2 ,-1
  115.82  175.53  849.65  221.53  477.98  852.92
Permanent Ineff=
       F       F
#Block Obstruct= 1 ,-1
 476.673 578.871  874.67
Bank Sta=-29.692,22.113
XS Rating Curve= 0 ,0
Exp/Cntr=0.3,0.1

Type RM Length L Ch R = 1 ,12017.29,204.929,197.038,157.18
Node Name=V
XS GIS Cut Line= 4
591871.1263389164386720.42477534591900.893107284 4386782.2686961
592141.1974302544387032.36624319592147.9822783384387039.42541128
#Sta/Elev= 30
  -76.87  897.96 -54.298  881.55 -40.092  867.19 -33.924  859.86 -30.184  850.98
 -24.442  840.33 -21.227  837.65       0   835.2  28.543  837.38  52.428  842.46
 236.516  842.66 271.916  842.55 280.381  844.09 397.999  845.24  430.02   846.8
 484.482  846.34 498.556  848.76 620.571  848.76 636.745  847.09 652.789  848.77
 706.824  849.04 833.005  851.561004.954  851.041113.812  857.441234.547  862.53
1248.655  863.941264.862  869.39 1309.35  893.571313.386  895.491318.373  895.63
#Mann= 7 ,-1 , 0
  -76.87     .12       0 -21.227     .04       0  28.543     .12       0
 236.516     .12       0 280.381     .13       0 652.789     .12       0
 706.824     .13       0
#XS Ineff= 2 , 0
       0                     507       0     850
Permanent Ineff=
       F       F
#Block Obstruct= 2 ,-1
 124.213 224.705  862.64 786.909 943.898  871.53
Bank Sta=-21.227,28.543
XS Rating Curve= 0 ,0
Exp/Cntr=0.5,0.3

Type RM Length L Ch R = 1 ,11820.24,13.148,13.135,13.268
XS GIS Cut Line= 4
591818.3867942654386716.32826329  591813.16557024386755.57431177
591866.4964268594386813.70881649592079.0548054864387053.13836345
#Sta/Elev= 30
-243.143   871.3-224.442  860.92-204.692  845.25-197.441843.1345-132.513  841.43
-115.682  842.73 -67.717  840.76 -58.891  842.14 -32.087  842.02 -25.886839.8191
 -16.437  836.61  -3.412  834.78  13.681  835.16  20.177   837.2  29.167   840.9
  37.894  841.44  223.13  842.29 241.142  845.07 548.655  845.64 634.318847.9862
 690.486847.9707 805.446  849.55 929.692  848.94 973.819  849.79  978.97  851.01
1063.353  849.491080.151  855.87 1090.19  858.031156.431  860.361195.997  864.19
#Mann= 9 ,-1 , 0
-243.143     .12       0-197.441     .12       0 -25.886     .12       0
 -16.437     .04       0  20.177     .12       0 186.417     .12       0
 229.232     .13       0 634.318     .12       0 690.486     .13       0
#XS Ineff= 2 , 0
                          556.28          851.88
Permanent Ineff=
       F       F
Bank Sta=-16.437,20.177
XS Rating Curve= 0 ,0
Exp/Cntr=0.5,0.3

Type RM Length L Ch R = 5 ,11813.68,,,
IW Pilot Flow=0
#Inline Weir SE= 30
-249.541     868-241.601  865.32 -229.56  858.37-219.488  851.34-214.731  845.89
-207.152   843.6-140.978  841.28-121.555  843.78-115.945  842.06 -79.856  840.89
 -33.038  842.11 -29.068   841.9 -20.144  835.97  16.732     836  21.555  836.77
  29.495  841.23   36.45  841.61 115.026  842.97 217.979  842.34 245.046  845.06
 401.345  845.82 427.133  844.75 589.173  846.28 644.915   848.4 942.388  848.95
 983.563  850.651062.828  849.261088.681  857.581164.698  860.941195.604  863.96
IW Dist,WD,Coef,Skew,MaxSub,Min_El,Is_Ogee,SpillHt,DesHd
1,2,2.6,0,0.98,, 0 ,,,0,0,

Type RM Length L Ch R = 1 ,11807.11,118.938,119.752,128.9
XS GIS Cut Line= 4
591814.4213462164386715.80095928591808.9532341484386756.90019179
591863.5246268224386816.38800852592076.0616694494387055.79317148
#Sta/Elev= 30
-255.971   865.8-239.009  859.65-219.226  844.46-217.224844.2238-204.528  841.94
-136.385  841.81-131.201  843.24-115.945  841.14 -29.232  842.26 -25.689840.7786
 -15.518  835.58  -3.412  833.28  13.681  833.66  19.783  836.93  29.134   841.4
  34.186  841.83 181.955842.3855 224.705842.3817 245.768  844.57 310.892  845.51
 439.698  844.86 632.808847.7952 688.944847.9855 849.705  849.88 941.863  848.35
 980.643  850.271060.925  849.171085.302  857.071152.723  860.01 1195.21  864.07
#Mann= 10 ,-1 , 0
-255.971     .12       0-217.224     .12       0 -25.689     .12       0
 -15.518     .04       0  19.783     .12       0 181.955     .12       0
 224.705     .13       0 632.808     .12       0 688.944     .13       0
1180.971      .2       0
#XS Ineff= 2 , 0
                          546.97          851.47
Permanent Ineff=
       F       F
#Block Obstruct= 1 ,-1
    -136     -47     855
Bank Sta=-15.518,19.783
XS Rating Curve= 0 ,0
Exp/Cntr=0.5,0.3

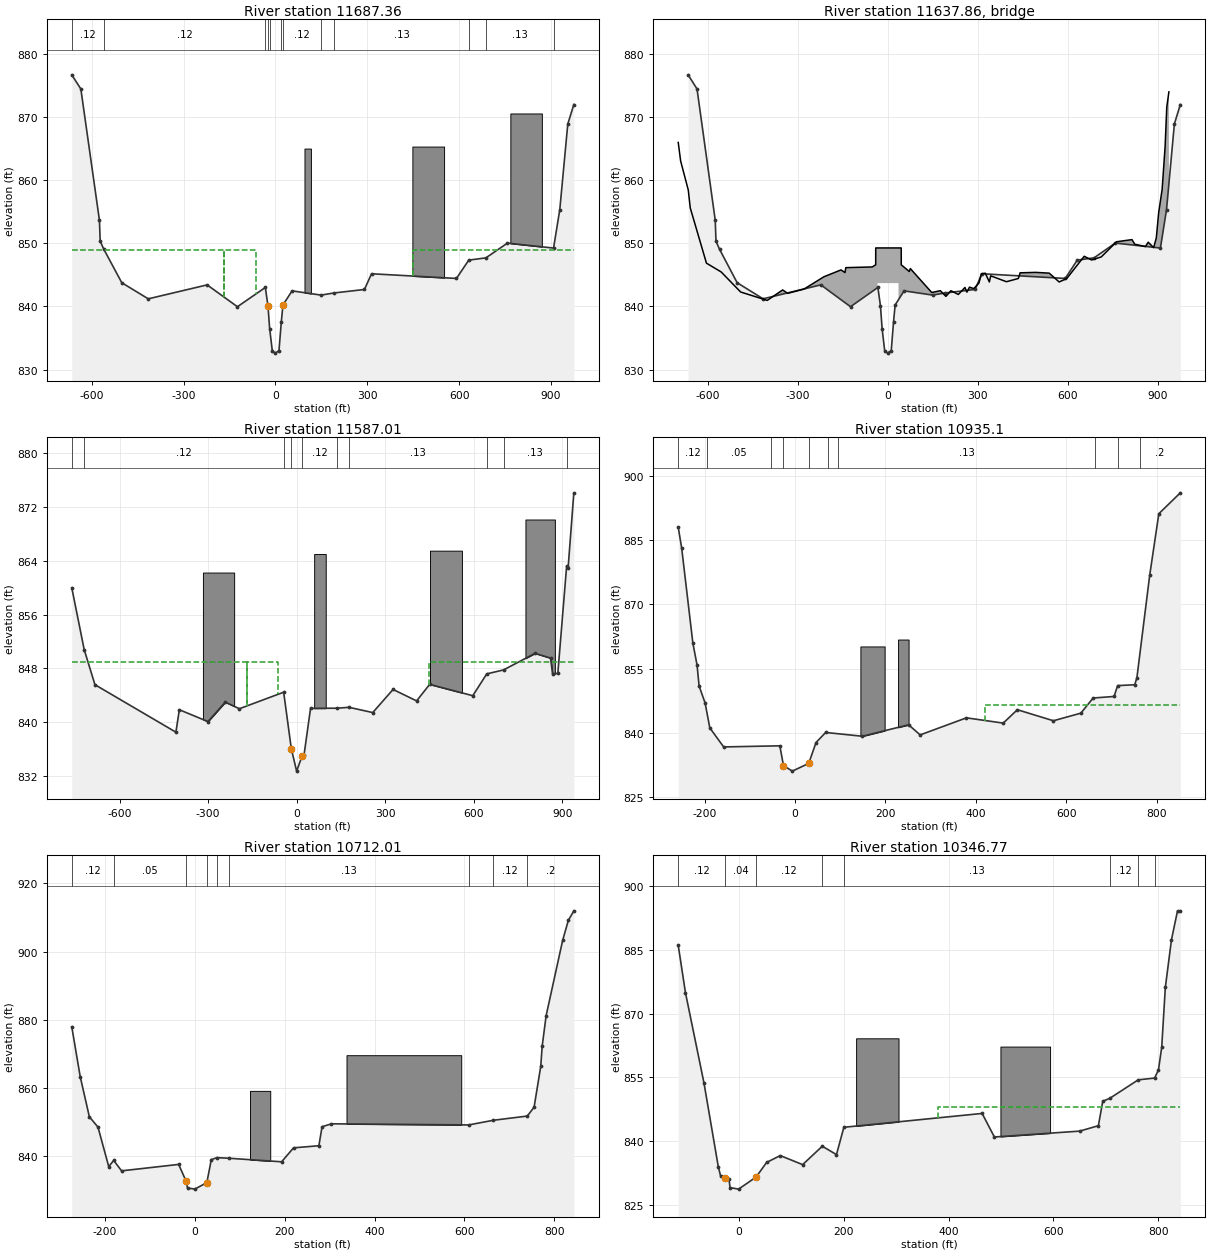
Type RM Length L Ch R = 1 ,11687.36,99.155,100.352,98.539
XS GIS Cut Line= 6
591736.7125852554386633.34951026591738.6389212794386737.88067155
591751.0778094334386746.68329566591768.3691136464386762.89255986
591830.0423464094386833.26173673591961.3105640314387060.75836354
#Sta/Elev= 30
-664.993  876.68-635.335  874.44-574.639  853.64-572.178  850.33  -560.4  849.06
 -501.64  843.75-415.157   841.2-222.835  843.41-123.983  839.95 -32.808     843
 -24.278  840.11 -18.734  836.49  -10.06  832.96       0   832.6   11.75  833.01
  19.455   837.6  24.738  840.23   54.56  842.46 149.409  841.79 191.568  842.13
 290.814  842.68 314.042  845.17 591.371  844.43 631.562  847.33 687.566  847.69
 758.005  850.03 908.497  849.24 928.904  855.34 954.954  868.88  974.77  871.98
#Mann= 12 ,-1 , 0
-664.993     .12       0  -560.4     .12       0 -32.808     .12       0
 -24.278     .04       0 -18.734     .04       0  19.455     .04       0
  24.738     .12       0 149.409     .12       0 191.568     .13       0
 631.562     .12       0 687.566     .13       0 908.497      .2       0
#XS Ineff= 4 ,-1
    -800    -167     849    -167     -64     849     450    1000     849
     315     450     840
Permanent Ineff=
       F       F       F       F
#Block Obstruct= 3 ,-1
 447.408 550.984  865.32 767.421 870.308  870.56      95     116     865
Bank Sta=-24.278,24.738
XS Rating Curve= 0 ,0
Exp/Cntr=0.5,0.3

Type RM Length L Ch R = 3 ,11637.86,,,
BEGIN DESCRIPTION:
Greenbag Road - Field Recon ID Deck 6
END DESCRIPTION:
Bridge Culvert--1,0,-1,-1, 0
Deck Dist Width WeirC Skew NumUp NumDn MinLoCord MaxHiCord MaxSubmerge Is_Ogee
27.9,9.8,2.6,0, 60, 60, , , 0.98, 0, 0,0,,
-697.933-689.961-664.567-657.874 -603.97-554.987-489.961-401.476-350.066-333.333
-278.609-212.861 -155.61 -142.29-139.633 -51.772   -40.1     -40     -34      36
      45    45.1  71.752  75.328 146.686  175.23 193.799 210.663 235.138 257.316
 263.878 272.375 286.778 303.806 311.844 325.066 338.583 343.143 395.538 435.105
 441.076 493.274 538.025 571.129 596.325  654.56 679.134 711.417 762.434 813.648
 823.228 858.432 867.848  885.86 894.816 902.559 914.272 924.081 929.626 936.745
  865.97  863.04  858.45   855.6  846.85  845.46  842.28  840.95  842.61  842.07
  842.75  844.69  845.78  845.36  846.14  846.25  846.59  849.26  849.26  849.26
  849.26  846.59  845.53  845.99   842.2  842.49  841.59  842.49  841.89     843
  842.26  843.05  842.82  843.69  845.15  845.26  843.87  844.84  843.91  844.42
  845.32  845.39  845.27  843.87  844.41  847.94  847.35  847.84  850.24  850.58
  849.84  849.48  850.17  849.31  850.86  854.81  858.56  865.29  871.56  873.98
                                                                                
                                                                  843.69  843.69
                                                                                
                                                                                
                                                                                
                                                                                
-697.933-689.961-664.567-657.874 -603.97-554.987-489.961-401.476-350.066-333.333
-278.609-212.861 -155.61 -142.29-139.633 -51.772   -40.1     -40     -34      36
      45    45.1  71.752  75.328 146.686  175.23 193.799 210.663 235.138 257.316
 263.878 272.375 286.778 303.806 311.844 325.066 338.583 343.143 395.538 435.105
 441.076 493.274 538.025 571.129 596.325  654.56 679.134 711.417 762.434 813.648
 823.228 858.432 867.848  885.86 894.816 902.559 914.272 924.081 929.626 936.745
  865.97  863.04  858.45   855.6  846.85  845.46  842.28  840.95  842.61  842.07
  842.75  844.69  845.78  845.36  846.14  846.25  846.59  849.26  849.26  849.26
  849.26  846.59  845.53  845.99   842.2  842.49  841.59  842.49  841.89     843
  842.26  843.05  842.82  843.69  845.15  845.26  843.87  844.84  843.91  844.42
  845.32  845.39  845.27  843.87  844.41  847.94  847.35  847.84  850.24  850.58
  849.84  849.48  850.17  849.31  850.86  854.81  858.56  865.29  871.56  873.98
                                                                                
                                                                  843.69  843.69
                                                                                
                                                                                
                                                                                
                                                                                
BR Coef=-1 , 1 , 0 ,, 0 ,,,0.8,0,0.3,0,
WSPro=,,,, 1 ,,,, 0 ,,,, 0 ,,,,-1 ,-1 ,-1 , 0 , 0 , 0 , 0 , 0
BC Design=,, 0 ,, 0 ,,,,,,
BC Use User HTab Curves=0
BC User HTab FreeFlow(D)= 0

Type RM Length L Ch R = 1 ,11587.01,682.21,651.905,595.855
XS GIS Cut Line= 6
591706.5739608834386622.42547813591708.9239689124386753.60835175
591732.0674331984386769.98220795591746.5271453774386783.53666412
 591805.899138114386851.41257696 591931.327387664387066.39106761
#Sta/Elev= 30
-761.844     860-719.685  850.78-683.333  845.57-409.022   838.5-397.375  841.84
-300.394  840.08-241.667  842.98-194.062  841.99  -43.93  844.45 -17.946  836.01
       0   832.7  18.766  834.98  25.098  835.11  47.146  842.05 136.385  842.07
 177.723   842.2  257.94  841.42 326.608  844.86 406.463  843.16 450.755  845.62
 596.818  843.93 644.094  847.18  701.05  847.77  807.71  850.24 860.367  849.53
 866.995  847.17 884.941  847.25 914.829  863.25 919.816  862.98 939.206  874.14
#Mann= 10 ,-1 , 0
-761.844     .12       0-719.685     .12       0  -43.93     .12       0
 -17.946     .04       0  18.766     .12       0 136.385     .12       0
 177.723     .13       0 644.094     .12       0  701.05     .13       0
 914.829      .2       0
#XS Ineff= 4 ,-1
   -1000    -167     849    -167     -64     849     450    1000     849
     318     450     840
Permanent Ineff=
       F       F       F       F
#Block Obstruct= 4 ,-1
-317.487 -211.68  862.27 451.804 560.007  865.53  775.23 874.902  870.17
    59.4    98.6  865.03
Bank Sta=-17.946,18.766
XS Rating Curve= 0 ,0
Exp/Cntr=0.5,0.3

Type RM Length L Ch R = 1 ,10935.1 ,206.621,223.09,252.828
Node Name=U
XS GIS Cut Line= 3
591564.0738631224386893.47802548591672.5338964624386969.65973842
591791.847857937 4387137.7508445
#Sta/Elev= 30
 -258.53  887.96-250.919  883.11-226.214  861.02-216.864  855.83-212.369  850.98
-199.081  847.01-188.648  841.21-158.005  836.77 -33.694  837.03 -25.656  832.43
  -6.102  831.13  30.282  832.93  46.424   837.8  67.684  840.14 148.885  839.26
  251.28  841.93 276.837  839.57 379.232  843.55 460.728  842.32 491.929  845.44
 571.785  842.87 632.415  844.64 659.744  848.17 705.971  848.53 713.878  851.06
 751.739  851.26 756.529   852.9 784.843  876.78 805.052  891.12 852.592  895.99
#Mann= 10 ,-1 , 0
 -258.53     .12       0-195.276     .05       0 -53.412     .12       0
 -25.656     .04       0  30.282     .12       0  72.572     .12       0
  95.243     .13       0 664.797     .12       0 714.075     .13       0
 762.664      .2       0
#XS Ineff= 2 , 0
                          420.75          846.55
Permanent Ineff=
       F       F
#Block Obstruct= 2 ,-1
 144.587 198.228  860.19 227.986 251.247   861.8
Bank Sta=-25.656,30.282
XS Rating Curve= 0 ,0
Exp/Cntr=0.3,0.1

Type RM Length L Ch R = 1 ,10712.01,353.295,365.239,334.615
Node Name=T
XS GIS Cut Line= 4
591530.865902711 4386927.6674419591625.2594158784387034.21333122
591711.5757289454387146.82474061591767.5431056364387153.24687669
#Sta/Elev= 30
-273.786   877.9 -255.02  863.27-234.678  851.47-215.453  848.42-191.535  836.82
-180.512  838.63-162.927  835.57 -35.925  837.46 -19.948  832.72  -16.21  830.56
       0   830.2  26.772  832.11  36.778  838.87  49.344  839.45  76.247  839.27
 193.241  838.23 219.751  842.33 276.148  842.95 283.235  848.53 304.232  849.39
 609.449  849.06 664.337  850.43 740.026  851.67 755.118  854.29 769.915  866.27
  773.13  872.25 781.955  881.21 818.668  903.29 831.299  909.15  843.57  911.97
#Mann= 9 ,-1 , 0
-273.786     .12       0-180.512     .05       0 -19.948     .04       0
  26.772     .12       0  49.344     .12       0  76.247     .13       0
 609.449     .12       0 664.337     .12       0 740.026      .2       0
#Block Obstruct= 2 ,-1
 122.867 167.913  859.07 337.631 592.979  869.55
Bank Sta=-19.948,26.772
XS Rating Curve= 0 ,0
Exp/Cntr=0.3,0.1

Type RM Length L Ch R = 1 ,10346.77,254.106,237.095,201.907
Node Name=S
XS GIS Cut Line= 3
591460.2864138394387012.86513895591540.2293588274387074.55361171
591630.7793439464387242.26676579
#Sta/Elev= 30
-114.928  885.99-101.181   874.9 -65.978  853.77 -38.648  834.09 -34.219  831.87
 -25.459  831.47 -18.274  831.21  -16.21  829.16       0   828.8  33.333  831.62
  53.478  835.07  79.429  836.67  122.08  834.55 159.547  838.87 186.549   836.9
 200.656  843.31 464.075  846.56 487.434  841.03 649.869  842.41 685.564  843.68
 693.898  849.41 707.349  850.11  761.45  854.44 792.684  854.86     800  856.75
 806.234  862.07 813.123  876.12 824.869  887.34 836.352   894.1 841.667     894
#Mann= 8 ,-1 , 0
-114.928     .12       0 -25.459     .04       0  33.333     .12       0
 159.547     .12       0 200.656     .13       0 707.349     .12       0
  761.45     .12       0 792.684      .2       0
#XS Ineff= 2 , 0
                          379.55          847.96
Permanent Ineff=
       F       F
#Block Obstruct= 2 ,-1
 223.983  304.79  864.19  498.95  593.57  862.25
Bank Sta=-25.459,33.333
XS Rating Curve= 0 ,0
Exp/Cntr=0.5,0.3

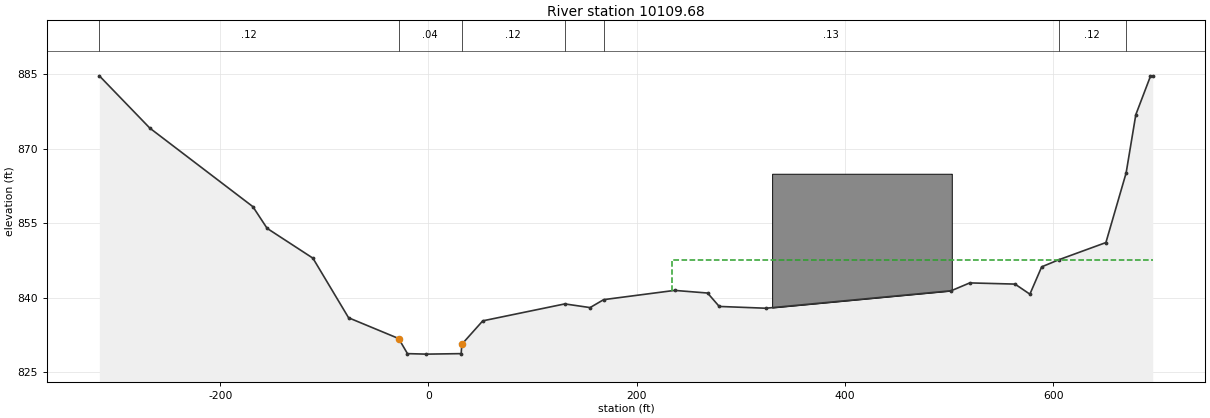
Type RM Length L Ch R = 1 ,10109.68,118.148,92.248,92.905
XS GIS Cut Line= 6
591350.1134044774387081.87795581591407.0988131824387088.80301189
591422.7472453754387086.37680386 591479.787518084387101.03463604
591505.1438303934387122.73639631591542.3263828534387260.53952601
#Sta/Elev= 30
-316.043  884.71-267.487  874.17-168.602  858.37-154.921     854-110.958     848
 -76.706     836 -28.642  831.82  -20.17  828.78      -2  828.68    31.4  828.78
  32.021  830.66  52.133  835.38 130.906  838.79 155.184  838.05 168.241  839.65
 236.352  841.51 268.012  840.98 279.199  838.28 324.049  837.92 501.936  841.44
 519.783  843.02 563.222  842.78 577.493  840.75 588.812  846.25  605.02  847.66
 650.492  851.14 669.915  865.16 679.232   876.9 693.307  884.65 695.472  884.68
#Mann= 7 ,-1 , 0
-316.043     .12       0 -28.642     .04       0  32.021     .12       0
 130.906     .12       0 168.241     .13       0  605.02     .12       0
 669.915      .2       0
#XS Ineff= 2 , 0
       0                  233.39       0  847.63
Permanent Ineff=
       F       F
#Block Obstruct= 1 ,-1
     330   502.5     865
Bank Sta=-28.642,32.021
XS Rating Curve= 0 ,0
Exp/Cntr=0.5,0.3