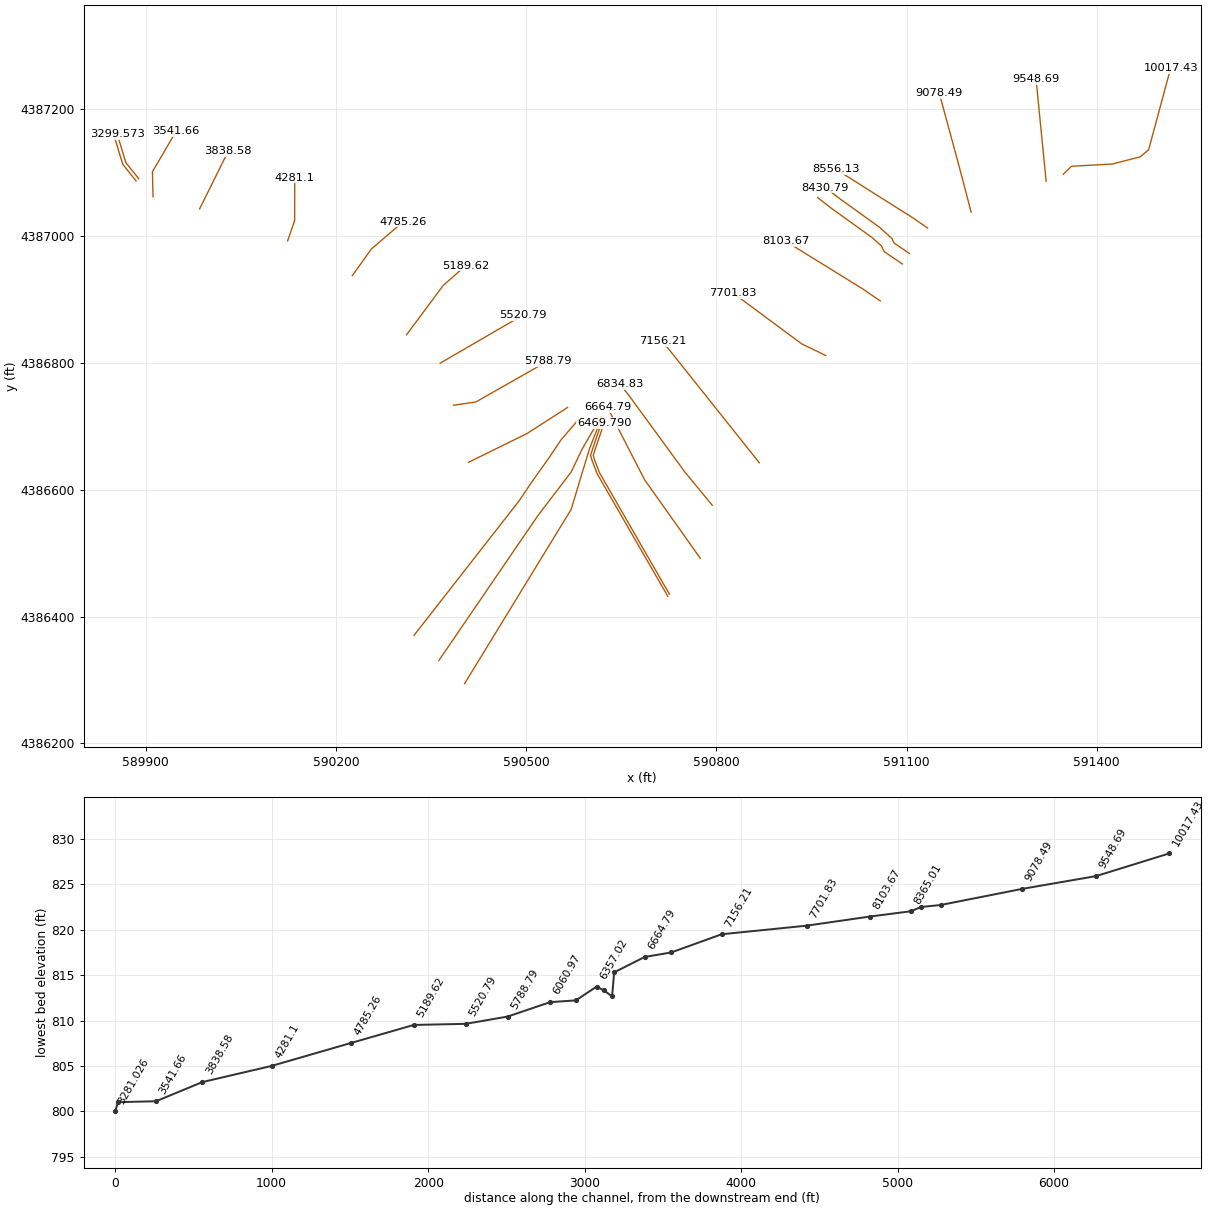
HEC-RAS study Deckers_Creek_Detail_Study.prj: Deckers_Creek_Detail_Study

--- Deckers_Creek_Detail_Study.g01 (geometry) --- (continued)

Type RM Length L Ch R = 2 ,10070.8 ,,,
BEGIN DESCRIPTION:
East Brockway Avenue /White Avenue - Field Recon ID Deck 5
END DESCRIPTION:
Bridge Culvert--1,0,-1,-1, 0
Deck Dist Width WeirC Skew NumUp NumDn MinLoCord MaxHiCord MaxSubmerge Is_Ogee
16,44,2.6,0, 60, 60, , , 0.98, 0, 0,0,,
-289.173-187.861-152.362-136.056-117.552 -90.289 -78.346 -51.804   -35.1     -35
      39    39.1  48.589  60.105  90.879   95.44  101.87 106.365 112.336 135.958
 147.408 153.182 162.598 181.201 185.564 193.668 199.541 213.255 222.867 228.806
  257.94 267.782 269.357 292.585  301.05 315.256 363.386 461.122 491.601 500.787
 507.087 513.091  523.13  528.51 548.983 555.676 559.777  567.06 569.291  593.34
  596.49 604.462  609.35 622.146 626.181 633.596 644.423 651.017 657.054 664.567
     862   847.6     842     840     838  835.95  835.15  834.26  834.38  836.21
  836.21  834.38  834.34  834.65  836.99  837.66  837.57  838.43  838.65  838.94
  838.14  838.23  838.85  839.14  839.76  839.35  839.86  839.99  840.57  840.13
  839.78  838.49  837.48  837.13  836.22  837.37  838.23  841.58  841.48  842.94
  842.45  842.74  842.28  842.72  842.13  840.36  841.39  846.06  846.83   848.6
  849.51  849.85  850.59  851.05  850.59  855.36  864.97   872.3  877.15  879.98
                                                                                
                                                                                
                                                                                
                                                                                
                                                                                
                                                                                
-289.173-187.861-152.362-136.056-117.552 -90.289 -78.346 -51.804   -35.1     -35
      39    39.1  48.589  60.105  90.879   95.44  101.87 106.365 112.336 135.958
 147.408 153.182 162.598 181.201 185.564 193.668 199.541 213.255 222.867 228.806
  257.94 267.782 269.357 292.585  301.05 315.256 363.386 461.122 491.601 500.787
 507.087 513.091  523.13  528.51 548.983 555.676 559.777  567.06 569.291  593.34
  596.49 604.462  609.35 622.146 626.181 633.596 644.423 651.017 657.054 664.567
     862   847.6     842     840     838  835.95  835.15  834.26  834.38  836.21
  836.21  834.38  834.34  834.65  836.99  837.66  837.57  838.43  838.65  838.94
  838.14  838.23  838.85  839.14  839.76  839.35  839.86  839.99  840.57  840.13
  839.78  838.49  837.48  837.13  836.22  837.37  838.23  841.58  841.48  842.94
  842.45  842.74  842.28  842.72  842.13  840.36  841.39  846.06  846.83   848.6
  849.51  849.85  850.59  851.05  850.59  855.36  864.97   872.3  877.15  879.98
                                                                                
                                                                                
                                                                                
                                                                                
                                                                                
                                                                                
BR Coef=-1 , 0 , 0 ,, 0 ,,,0.8,-1,,0,
WSPro=,,,, 1 ,,,, 0 ,,,, 0 ,,,,-1 ,-1 ,-1 , 0 , 0 , 0 , 0 , 0
Multiple Barrel Culv=5,4.5,14,44,0.024,0.5,1,41,1,828.88,828.68, 2,Culvert #1  , 0 ,16
     -13     -17       2      -1
Culvert Bottom n=0.024
Multiple Barrel Culv=1,3.5,,44,0.013,0.5,1,1,1,828.88,828.68, 4,Culvert #2  , 0 ,16
      12      12      18      18      24      24      30      30
Culvert Bottom n=0.013
BC Design=,, 0 ,, 0 ,,,,,,
BC Use User HTab Curves=0
BC User HTab FreeFlow(D)= 0

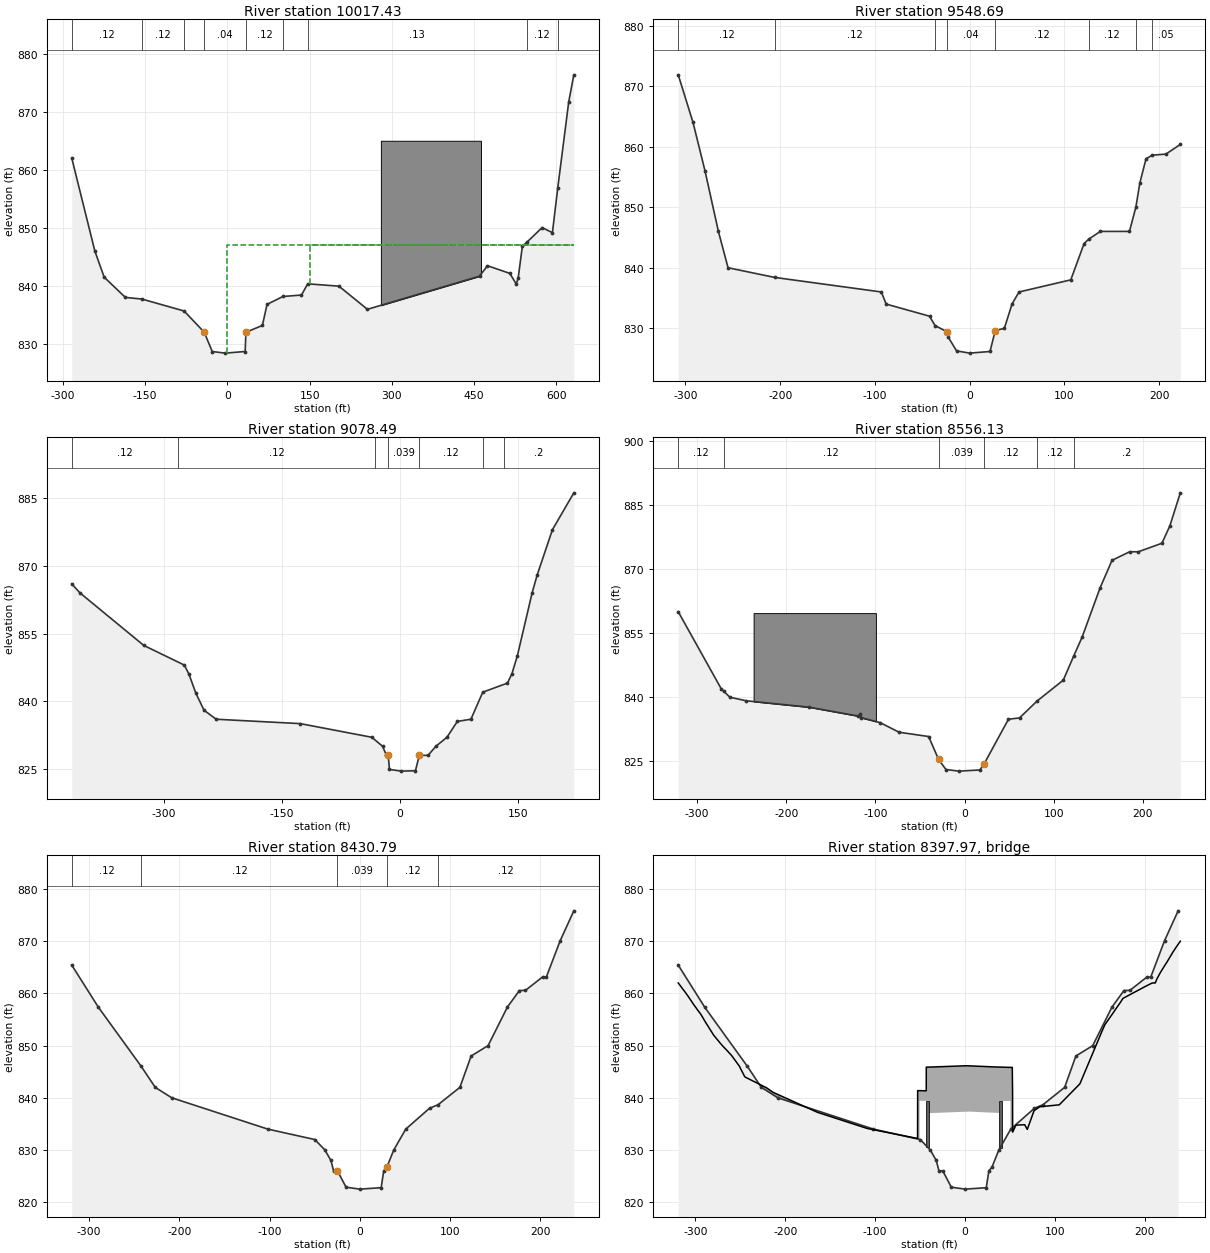
Type RM Length L Ch R = 1 ,10017.43,345.963,468.744,589.118
XS GIS Cut Line= 6
591347.275716442  4387097.526388591360.2144766024387110.05062015
591424.426693396 4387113.5802042591468.7507099434387124.97058034
591481.7687181044387136.11406848591516.5372545344387264.96827007
#Sta/Elev= 30
-283.727     862-241.667     846-224.639  841.49-185.958     838-155.971  837.72
 -78.839  835.66 -42.159     832  -27.56  828.68      -4   828.4   32.48  828.68
  33.891     832  63.944  833.17  72.408   836.8 101.411  838.16 135.236  838.41
 146.555  840.34 203.478  839.94 255.446  835.95 459.875  841.66 474.442  843.46
  515.19  842.14 526.936   840.3 530.512   841.4 538.058  846.84  546.26  847.51
 574.016  850.03 592.848  849.16 602.461  856.78 622.605  871.72 631.923  876.36
#Mann= 9 ,-1 , 0
-283.727     .12       0-155.971     .12       0 -78.839     .12       0
 -42.159     .04       0  33.891     .12       0 101.411     .12       0
 146.555     .13       0  546.26     .12       0 602.461      .2       0
#XS Ineff= 2 , 0
       0    -120     847     150       0  847.08
Permanent Ineff=
       F       F
#Block Obstruct= 1 ,-1
     280   462.5     865
Bank Sta=-42.159,33.891
XS Rating Curve= 0 ,0
Exp/Cntr=0.5,0.3

Type RM Length L Ch R = 1 ,9548.69 ,450.654,470.201,480.195
Node Name=R
XS GIS Cut Line= 2
591320.1088921064387086.54444386 591304.213571914387247.29291785
#Sta/Elev= 30
-307.644  871.86 -292.06     864-279.396     856-265.256     846-255.052     840
-205.807   838.4 -93.241     836 -88.189     834 -42.421     832 -36.516  830.44
 -23.655  829.41  -22.54  828.51  -13.86  826.27       0   825.9   21.46  826.17
  26.936  829.61  36.614     830  44.652     834    52.1     836 106.693     838
 120.768     844 125.787  844.74 137.861     846 168.635     846 175.394     850
 179.593     854 186.122     858 192.684  858.59 207.119  858.77  222.31  860.36
#Mann= 8 ,-1 , 0
-307.644     .12       0-205.807     .12       0 -36.516     .12       0
 -23.655     .04       0  26.936     .12       0 125.787     .12       0
 175.394      .2       0 192.684     .05       0
Bank Sta=-23.655,26.936
XS Rating Curve= 0 ,0
Exp/Cntr=0.3,0.1

Type RM Length L Ch R = 1 ,9078.49 ,448.207,522.358,555.752
Node Name=Q
XS GIS Cut Line= 3
591201.8617306454387037.63013926591183.3908504174387108.10294813
591151.6154500244387225.29245358
#Sta/Elev= 30
-416.535     866-406.135     864-325.131  852.36-273.622     848-267.848  846.03
-259.055   841.8-248.655     838-233.169     836-126.444  835.03 -35.597     832
 -21.916     830  -17.06     828 -14.797     828  -13.25  824.87       2   824.5
   19.77  824.58  24.672     828  35.761     828  45.702     830  59.744     832
  72.966  835.52   90.19     836 105.249     842 136.483     844 142.093     846
 149.081     850 167.881     864 174.377     868 193.668     878 220.866  886.18
#Mann= 7 ,-1 , 0
-416.535     .12       0-281.398     .12       0 -31.824     .12       0
 -14.797    .039       0  24.672     .12       0 105.184     .12       0
 132.743      .2       0
Bank Sta=-14.797,24.672
XS Rating Curve= 0 ,0
Exp/Cntr=0.3,0.1

Type RM Length L Ch R = 1 ,8556.13 ,130.851,125.341,122.633
Node Name=P
XS GIS Cut Line= 3
591133.1628577964387012.68530695591108.8184814954387029.42187516
 590988.663272014387105.21344409
#Sta/Elev= 30
-321.096  859.99-272.966     842-270.177  841.41-263.222     840-244.783  839.16
-174.311  837.67-119.029  835.58-117.126     836-115.715   835.2 -94.816  834.07
 -73.425  831.81 -40.289  830.81 -29.134  825.44 -20.833  823.09  -6.266  822.72
  17.224  822.99  22.113  824.49  49.213  834.85  61.647  835.16  81.266   839.1
 110.728     844 122.375  849.63 131.726     854 151.936  865.54 165.354     872
 185.105     874 194.915     874 221.325     876 230.118     880 241.929  887.78
#Mann= 6 ,-1 , 0
-321.096     .12       0-270.177     .12       0 -29.134    .039       0
  22.113     .12       0  81.266     .12       0 122.375      .2       0
#Block Obstruct= 1 ,-1
-236.581 -99.442  859.66
#XS Lid=3
     -48  836.46  834.52     -42  836.46  834.52     -38  836.46  834.52
Bank Sta=-29.134,22.113
XS Rating Curve= 0 ,0
Exp/Cntr=0.5,0.3

Type RM Length L Ch R = 1 ,8430.79 ,65.821,65.781,65.617
XS GIS Cut Line= 6
591104.5604254424386972.46694645591080.2343371424386989.09073866
591077.0491771024386995.92435474591057.7400968644387013.50826696
590992.6043360594387060.38955554590972.0486238054387076.44946774
#Sta/Elev= 30
-319.029  865.42-289.469  857.33-242.028     846-226.608     842-208.301     840
-101.936     834 -49.803     832 -38.681     830 -32.021     828 -29.035     826
  -24.77     826  -15.25  822.87       0   822.5   23.61  822.77  26.509     826
  29.954   826.7  37.598     830  50.886     834  77.231     838  86.581  838.66
 110.827     842 123.294     848  142.06     850  163.55  857.41 176.804  860.55
 183.432  860.58 202.756   863.2 206.496  863.09 221.949  870.11 237.041  875.82
#Mann= 5 ,-1 , 0
-319.029     .12       0-242.028     .12       0  -24.77    .039       0
  29.954     .12       0  86.581     .12       0
#XS Lid=3
     -56  838.95  836.95     -42  838.95  836.97     -34  838.95     837
Bank Sta=-24.77,29.954
XS Rating Curve= 0 ,0
Exp/Cntr=0.5,0.3

Type RM Length L Ch R = 3 ,8397.97 ,,,
BEGIN DESCRIPTION:
Footbridge - Survey ID  Dec 3
END DESCRIPTION:
Bridge Culvert--1,0,-1,-1, 0
Deck Dist Width WeirC Skew NumUp NumDn MinLoCord MaxHiCord MaxSubmerge Is_Ogee
28,9.5,2.6,0, 106, 106, , , , 0, 0,0,,
-319.029-313.878-313.025-312.861-311.745-311.614-310.335-310.138-310.105-310.072
-308.465-307.185-305.938-305.184-302.789 -302.69-302.428-299.541-299.081-297.539
-296.883 -296.03-294.882 -293.93-293.406-292.323-291.535 -290.65-290.059-286.942
-285.991-285.007-284.285-279.626-272.671 -269.98-266.109 -265.65-265.092 -264.37
 -263.32-261.844-260.663-260.203-260.138-259.941 -259.81-259.219-255.741-250.787
-250.295-244.948-222.769-222.211-221.555-213.353-185.138-163.944-108.793 -52.817
  -52.69 -50.591 -43.143  -43.11  -39.96  -39.93   2.001   4.396   37.67  37.797
  50.558   52.56  52.869  52.969  56.562  66.371  69.259  76.804  83.169 104.823
 127.789 153.051 155.545 157.841 163.681 168.504 171.719 173.196 174.738 175.623
 200.427 208.268 209.088 210.269 210.728 211.286 211.581 212.238 213.484  217.29
 222.605 224.606 231.398 231.594 234.318 239.468
     862  860.81  860.62  860.59  860.33   860.3     860  859.96  859.95  859.94
  859.55  859.23  858.91  858.72  858.09  858.07     858  857.31  857.21  856.83
  856.68  856.49  856.23     856  855.85  855.54  855.32  855.05  854.87     854
  853.75  853.47  853.27     852  850.54     850   849.3  849.22  849.12  848.98
  848.79   848.5  848.29   848.2  848.18  848.15  848.12     848  847.17     846
  845.79     844  842.08  842.04     842  841.03  838.84   837.2  834.12   832.2
  841.37  841.37  841.34  845.87  845.88  845.88  846.14  846.12  845.88  845.89
  845.82  845.82  841.33  833.42  834.76  834.84  833.94  837.55  838.28  838.65
  842.68  853.04     854  854.57     856  857.22     858  858.38  858.79  859.04
  861.32     862     862     862     862     862     862  862.26  862.78     864
  865.47     866  867.96     868  868.72     870
                                                                                
                                                                                
                                                                                
                                                                                
                                                                                
                                                                                
          839.42  839.41  839.41  839.42  837.06  837.34  837.36  837.09  839.39
  839.39
                                                                                
                                                                                
                                                
-319.029-313.878-313.025-312.861-311.745-311.614-310.335-310.138-310.105-310.072
-308.465-307.185-305.938-305.184-302.789 -302.69-302.428-299.541-299.081-297.539
-296.883 -296.03-294.882 -293.93-293.406-292.323-291.535 -290.65-290.059-286.942
-285.991-285.007-284.285-279.626-272.671 -269.98-266.109 -265.65-265.092 -264.37
 -263.32-261.844-260.663-260.203-260.138-259.941 -259.81-259.219-255.741-250.787
-250.295-244.948-222.769-222.211-221.555-213.353-185.138-163.944-108.793 -52.817
  -52.69 -50.591 -43.143  -43.11  -39.96  -39.93   2.001   4.396   37.67  37.797
  50.558   52.56  52.869  52.969  56.562  66.371  69.259  76.804  83.169 104.823
 127.789 153.051 155.545 157.841 163.681 168.504 171.719 173.196 174.738 175.623
 200.427 208.268 209.088 210.269 210.728 211.286 211.581 212.238 213.484  217.29
 222.605 224.606 231.398 231.594 234.318 239.468
     862  860.81  860.62  860.59  860.33   860.3     860  859.96  859.95  859.94
  859.55  859.23  858.91  858.72  858.09  858.07     858  857.31  857.21  856.83
  856.68  856.49  856.23     856  855.85  855.54  855.32  855.05  854.87     854
  853.75  853.47  853.27     852  850.54     850   849.3  849.22  849.12  848.98
  848.79   848.5  848.29   848.2  848.18  848.15  848.12     848  847.17     846
  845.79     844  842.08  842.04     842  841.03  838.84   837.2  834.12   832.2
  841.37  841.37  841.34  845.87  845.88  845.88  846.14  846.12  845.88  845.89
  845.82  845.82  841.33  833.42  834.76  834.84  833.94  837.55  838.28  838.65
  842.68  853.04     854  854.57     856  857.22     858  858.38  858.79  859.04
  861.32     862     862     862     862     862     862  862.26  862.78     864
  865.47     866  867.96     868  868.72     870
                                                                                
                                                                                
                                                                                
                                                                                
                                                                                
                                                                                
          839.42  839.41  839.41  839.42  837.04  837.34  837.36  836.97  839.39
  839.39
                                                                                
                                                                                
                                                
Pier Skew, UpSta & Num, DnSta & Num=  ,-41.43, 2 ,-41.43, 2 , 0 , 0 , 0 ,,
       3       3
     815     840
       3       3
     815     840
Pier Skew, UpSta & Num, DnSta & Num=  ,39.17, 2 ,39.17, 2 , 0 , 0 , 0 ,,
       3       3
     815     840
       3       3
     815     840
BR Coef= 1 , 1 , 1 ,0.9, 0 ,,,0.8,0,1.2,0,
WSPro=,,,, 1 ,,,, 0 ,,,, 0 ,,,,-1 ,-1 ,-1 , 0 , 0 , 0 , 0 , 0
BC Design=,, 0 ,, 0 ,,,,,,
BC Use User HTab Curves=0
BC User HTab FreeFlow(D)= 0

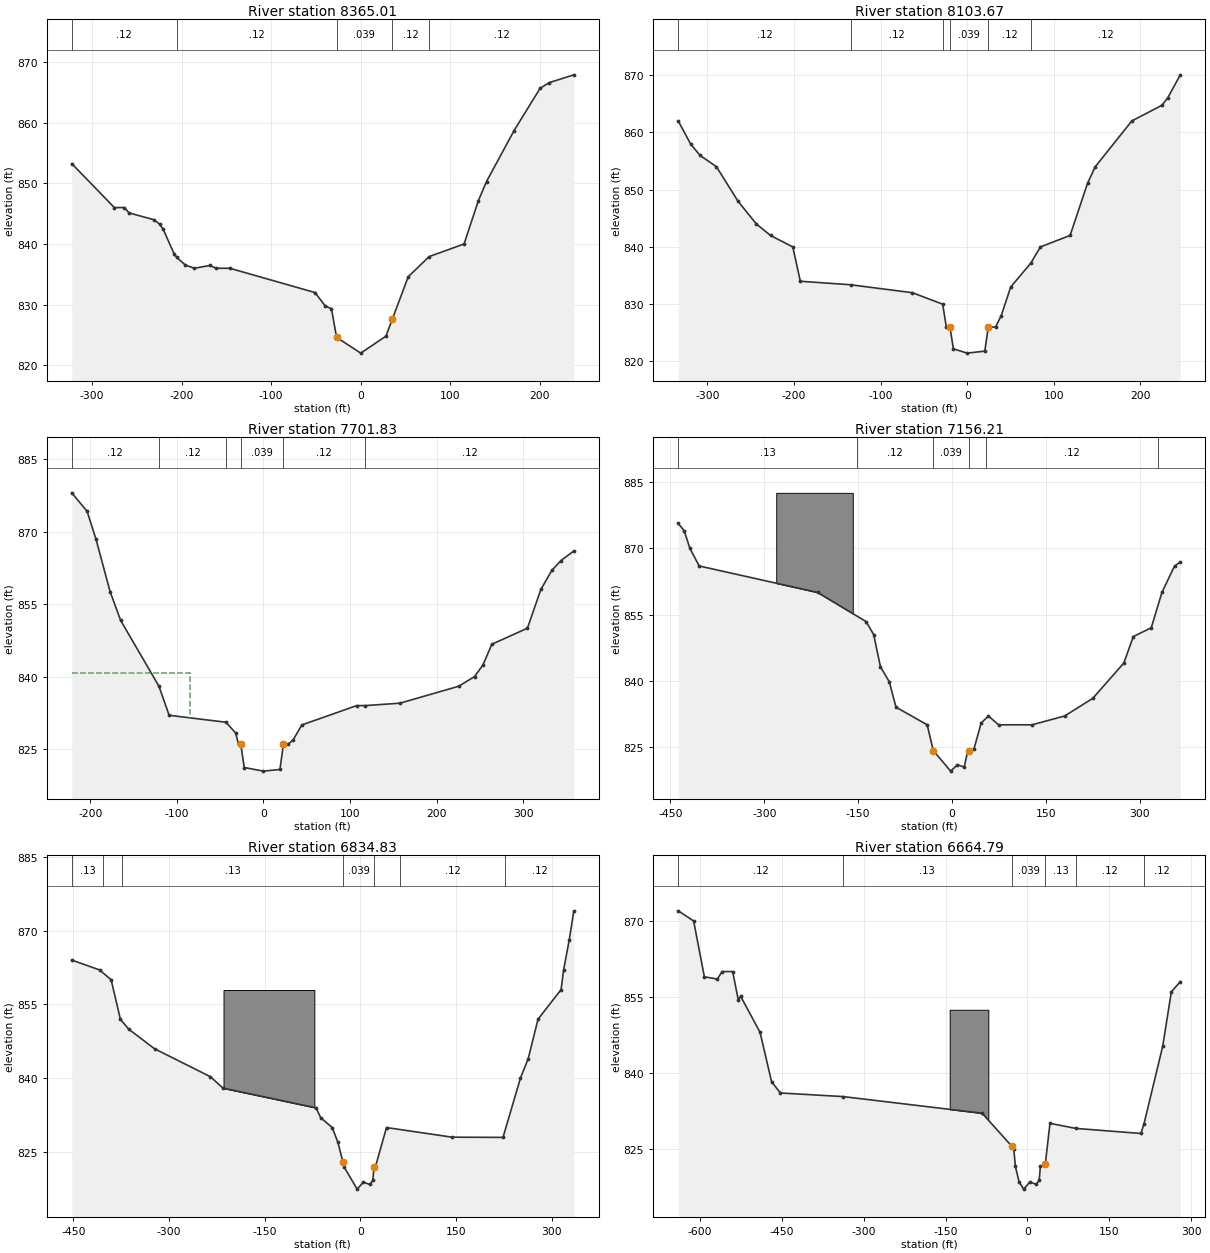
Type RM Length L Ch R = 1 ,8365.01 ,254.294,261.333,263.892
XS GIS Cut Line= 6
591093.2736813034386955.95288225591064.4243609464386975.67344249
591060.340040896 4386984.4333946591045.1183287084386997.98480277
590980.6897039124387044.31745134590959.7347036534387060.68825954
#Sta/Elev= 30
-322.703  853.23-275.164     846-263.812     846-258.825  845.12-231.037     844
-224.573  843.27-220.538  842.41-208.038  838.27-205.446   837.8-195.833  836.54
-185.728     836-168.701  836.46-161.056     836-146.063     836 -50.886     832
 -39.534  829.79 -32.579  829.35  -26.87  824.63    .164  822.03  28.281  824.82
  35.335  827.59  53.215  834.61  76.608  837.93 115.584     840 131.594  847.15
  140.65  850.28 171.457  858.68 200.525  865.63 210.794  866.57 238.222  867.85
#Mann= 5 ,-1 , 0
-322.703     .12       0-205.446     .12       0  -26.87    .039       0
  35.335     .12       0  76.608     .12       0
#XS Lid=2
    35.5  838.92  836.94      49  838.92  836.94
Bank Sta=-26.87,35.335
XS Rating Curve= 0 ,0
Exp/Cntr=0.5,0.3

Type RM Length L Ch R = 1 ,8103.67 ,407.965,401.847,395.89
Node Name=O
XS GIS Cut Line= 3
591058.5935368744386897.58672953591032.4416965514386915.62784175
590909.1836230284386991.86746669
#Sta/Elev= 30
-333.661     862-319.455     858-308.629     856-289.534     854-264.731     848
-243.438     844  -227.1     842-201.411     840-192.684     834-134.711  833.39
 -63.255     832 -28.314     830 -24.081     826 -19.948     826  -15.94   822.2
       0  821.45    20.3   821.8  24.311     826  32.677     826  39.304     828
  50.164  832.99  73.425  837.16  84.514     840 118.799     842 139.009  851.14
 147.867     854 190.092     862 224.639  864.71  231.43     866 246.063  870.05
#Mann= 6 ,-1 , 0
-333.661     .12       0-134.711     .12       0 -28.314     .12       0
 -19.948    .039       0  24.311     .12       0  73.425     .12       0
Bank Sta=-19.948,24.311
XS Rating Curve= 0 ,0
Exp/Cntr=0.3,0.1

Type RM Length L Ch R = 1 ,7701.83 ,567.537,545.616,532.867
Node Name=N
XS GIS Cut Line= 3
590972.6490798124386811.55388046590934.8173033454386829.86321669
590826.5980620074386909.98904168
#Sta/Elev= 30
-221.227     878 -203.51  874.17-193.274  868.41-177.001  857.59-164.862  851.64
-120.571     838-108.825     832 -43.241  830.56 -32.054  828.34 -28.707     826
 -26.115     826   -22.1   821.2       0  820.45    19.1   820.8   23.13     826
  28.478     826  34.318   826.9  44.423     830  107.71     834 117.487     834
  157.71   834.5 225.459     838 243.799     840 253.346  842.36 263.812  846.69
 304.823     850 320.374  858.03 333.169     862 343.635     864 358.432  865.98
#Mann= 6 ,-1 , 0
-221.227     .12       0-120.571     .12       0 -43.241     .12       0
 -26.115    .039       0   23.13     .12       0 117.487     .12       0
#XS Ineff= 2 , 0
          -85.29  840.76
Permanent Ineff=
       F       F
Bank Sta=-26.115,23.13
XS Rating Curve= 0 ,0
Exp/Cntr=0.3,0.1

Type RM Length L Ch R = 1 ,7156.21 ,323.708,321.379,317.014
Node Name=M
XS GIS Cut Line= 2
590867.7765425164386642.44779037590715.2820526314386833.77684874
#Sta/Elev= 30
  -437.5  875.64-428.018     874-418.832     870-404.035     866  -214.6     860
-137.303  853.41-125.033  850.46-114.206  843.15-100.098  839.76  -89.37     834
 -39.501     830 -29.724  824.16      -2   819.5    8.84  820.92    19.7  820.44
  25.328     824  27.264   824.1  35.236   824.5  46.916  830.43  58.497     832
  74.639     830 128.182     830 180.381     832 225.295     836 274.934     844
 290.092     850 318.799     852 335.827     860 356.037     866 365.223  866.89
#Mann= 6 ,-1 , 0
  -437.5     .13       0-151.312     .12       0 -29.724    .039       0
  27.264     .12       0  54.659     .12       0  329.56     .12       0
#Block Obstruct= 1 ,-1
-280.807-158.465  882.58
Bank Sta=-29.724,27.264
XS Rating Curve= 0 ,0
Exp/Cntr=0.3,0.1

Type RM Length L Ch R = 1 ,6834.83 ,176.442,170.042,153.332
Node Name=L
XS GIS Cut Line= 4
590793.5485975994386575.47408555590750.9436530724386627.17121419
590661.128235962 4386750.0086637590647.884675798 4386766.0899119
#Sta/Elev= 30
-452.526     864-408.825     862-390.781     860-376.312     852-363.484     850
-322.736     846-234.974  840.31-215.354     838 -69.423     834 -62.139     832
 -44.062     830 -35.203  827.01 -27.329  822.99 -25.492     822      -5   817.5
    4.86  818.92   14.73  818.44   19.51  819.26  21.522     822  23.589     822
  41.043     830 143.766  828.05 223.753     828 251.115  840.04  263.32     844
 278.675     852 314.797     858 318.766     862 327.559  868.05 334.842     874
#Mann= 7 ,-1 , 0
-452.526     .13       0-402.953     .12       0 -373.13     .13       0
 -27.329    .039       0  21.522     .13       0  62.467     .12       0
 227.395     .12       0
#Block Obstruct= 1 ,-1
-214.567  -72.08  857.92
Bank Sta=-27.329,21.522
XS Rating Curve= 0 ,0
Exp/Cntr=0.3,0.1

Type RM Length L Ch R = 1 ,6664.79 ,189.6,195,169.695
Node Name=K
XS GIS Cut Line= 4
590774.6205173654386491.90402051590686.8960282814386615.62843804
590642.968251738 4386701.0394951590628.3744275574386729.98025546
#Sta/Elev= 30
-639.304     872-611.089     870 -591.47  858.96-567.881  858.52-558.858     860
-539.665     860-529.364  854.36-525.131  855.12-489.567     848-468.438  838.22
-452.297     836-337.697  835.29 -82.972     832 -29.134  825.53 -25.066  824.85
 -22.146   821.5  -15.43  818.42      -7     817    4.43  818.42   15.89  817.94
   21.43  818.76  23.622   821.5  32.644     822  41.142     830  88.451     829
 207.644     828 213.255   829.9 247.441  845.21  263.32     856 279.724     858
#Mann= 6 ,-1 , 0
-639.304     .12       0-337.697     .13       0 -29.134    .039       0
  32.644     .13       0  88.451     .12       0 213.255     .12       0
#Block Obstruct= 1 ,-1
-142.454 -71.686  852.45
Bank Sta=-29.134,32.644
XS Rating Curve= 0 ,0
Exp/Cntr=0.5,0.3

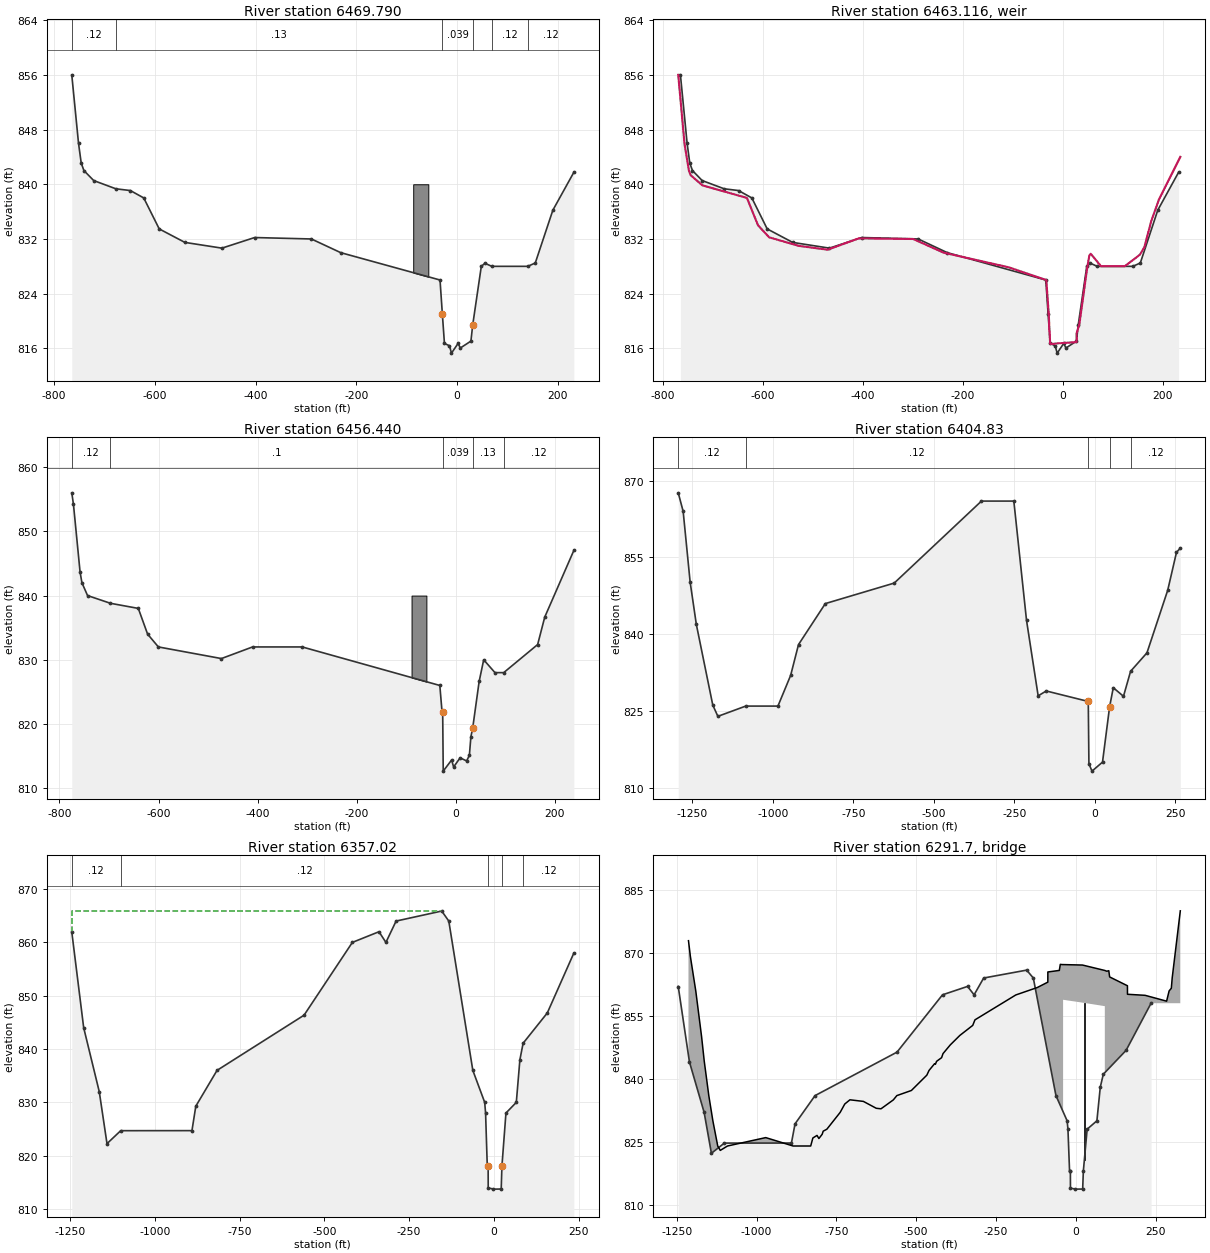
Type RM Length L Ch R = 1 ,6469.790,13.344,13.35,18.422
XS GIS Cut Line= 6
590725.9317647634386435.30265981590615.3929953974386627.38457419
590613.9848193794386631.36831024590608.1997153084386646.36447042
590605.8314192794386654.14601452590622.8697394894386705.15429515
#Sta/Elev= 30
-764.895     856-751.509     846-746.129  843.09-740.748     842-721.325  840.54
-677.329839.3372-648.556  839.08-621.982     838 -591.24  833.47-540.354   831.5
-466.798  830.66-401.903  832.21 -289.14     832-230.906     830  -33.76     826
 -29.134  821.02     -25  816.73 -15.123  816.39  -10.99  815.31   2.068  816.73
   6.596  816.06  27.589  817.07  31.037  819.38  48.196     828  55.479  828.45
  68.996     828 140.486     828 155.348  828.49 190.256  836.21 231.923  841.75
#Mann= 6 ,-1 , 0
-764.895     .12       0-677.329     .13       0 -29.134    .039       0
  31.037     .13       0  68.996     .12       0 140.486     .12       0
#Block Obstruct= 1 ,-1
     -87     -57     840
Bank Sta=-29.134,31.037
XS Rating Curve= 0 ,0
Exp/Cntr=0.5,0.3

Type RM Length L Ch R = 5 ,6463.116,,,
IW Pilot Flow=0
#Inline Weir SE= 30
-769.259     856-756.627  845.88  -747.9     842 -744.39  841.32-720.932  839.84
-631.759     838-609.613     834 -587.27  832.24-527.887  830.99-470.341  830.43
-408.169  832.09-299.442     832-238.255     830-108.104  827.86 -32.808     826
  -27.92  821.03 -25.066  816.65    27.8  816.93  27.822  818.23  33.366  819.51
  49.377  827.94  53.412   829.6  56.135  829.84  76.837     828 123.983     828
 154.659  829.71 163.353   830.8 177.133  834.59 192.651  837.78 235.367     844
IW Dist,WD,Coef,Skew,MaxSub,Min_El,Is_Ogee,SpillHt,DesHd
1,2,2.6,0,0.98,, 0 ,,,0,0,

Type RM Length L Ch R = 1 ,6456.440,121.34,51.612,17.864
XS GIS Cut Line= 6
590723.4842207334386431.85232377590611.7445393524386625.70512617
590610.2327313334386629.98147022590604.4140992614386645.05992641
590601.6343232274386654.20392652590619.0749794424386706.41921517
#Sta/Elev= 30
-775.197     856 -771.85  854.25-758.432  843.67-754.692     842-743.307     840
-697.113838.7985-640.814     838 -622.08     834-600.295     832-472.966  830.19
-410.072     832 -309.81     832  -31.89     826 -27.526     822 -26.115  821.87
     -25  812.66  -8.123  814.39   -3.99  813.31   9.068  814.73  22.224  814.25
    27.8  815.11   30.84     818  34.613  819.43  47.539  826.63  56.726     830
  79.462     828  97.146     828  165.65  832.37  180.02  836.65  238.78  847.03
#Mann= 5 ,-1 , 0
-775.197     .12       0-697.113      .1       0 -26.115    .039       0
  34.613     .13       0  97.146     .12       0
#Block Obstruct= 1 ,-1
     -89     -59     840
Bank Sta=-26.115,34.613
XS Rating Curve= 0 ,0
Exp/Cntr=0.5,0.3

Type RM Length L Ch R = 1 ,6404.83 ,63.341,47.803,47.493
Node Name=J
XS GIS Cut Line= 5
590402.9504407714386294.04005007590570.9287708474386568.64656546
590599.7567552044386663.99105464 590614.816923394386702.63969512
590618.5994914374386713.95387126
#Sta/Elev= 30
-1293.11  867.61-1277.85     864 -1256.2  850.21 -1236.9  841.92-1185.92   826.2
-1170.07     824-1083.66     826-983.727     826-944.193     832-919.882     838
-836.614     846-622.835     850  -352.1     866 -251.64     866-212.205  842.71
-176.148     828-150.984  828.95 -21.129  826.91 -20.604  826.89 -18.602  814.73
   -8.99  813.31  23.589  815.07  45.604  825.86  56.988  829.59  88.648  827.91
 110.728  832.79 161.516  836.39 225.919   848.6  253.15     856 265.026  856.82
#Mann= 5 ,-1 , 0
-1293.11     .12       0-1083.66     .12       0 -21.129    .039       0
  45.604     .13       0 110.728     .12       0
#XS Ineff= 2 , 0
         -254.21  865.92
Permanent Ineff=
       F       F
Bank Sta=-21.129,45.604
XS Rating Curve= 0 ,0
Exp/Cntr=0.5,0.3

Type RM Length L Ch R = 1 ,6357.02 ,141.414,132.633,129.152
XS GIS Cut Line= 5
 590362.348032274386330.49717852590518.2258021964386558.60035734
590570.9653468484386627.68327819 590588.137779064386663.61005464
590612.5217793614386705.55053515
#Sta/Elev= 30
 -1245.4  861.98-1210.26     844-1164.27     832-1141.47  822.26-1101.01  824.69
-890.781   824.7-879.429  829.28-816.765     836-560.039  846.35-417.487     860
-338.976     862-318.504     860-288.484     864-153.806  865.88-132.972     864
 -62.073     836 -27.034     830 -24.442     828 -19.423     818 -16.864     818
  -16.64  813.97  -1.312  813.73   21.68  813.75  23.753     818  35.663     828
   66.24     830  76.804     838  86.319  841.09 157.677  846.77 235.991     858
#Mann= 5 ,-1 , 0
 -1245.4     .12       0-1101.01     .12       0 -16.864    .039       0
  23.753     .13       0  86.319     .12       0
#XS Ineff= 2 , 0
         -154.41  865.92
Permanent Ineff=
       F       F
Bank Sta=-16.864,23.753
XS Rating Curve= 0 ,0
Exp/Cntr=0.5,0.3

Type RM Length L Ch R = 3 ,6291.7  ,,,
BEGIN DESCRIPTION:
Rogers Street - Survey ID  Dec 2
END DESCRIPTION:
Bridge Culvert--1,0,-1,-1, 0
Deck Dist Width WeirC Skew NumUp NumDn MinLoCord MaxHiCord MaxSubmerge Is_Ogee
42,36.7,2.6,0, 60, 60, , , , 0, 0,0,,
-1213.32-1207.31-1190.35-1172.17-1163.91-1149.63 -1136.9-1121.65-1113.71-1091.07
-971.293-885.597-830.413-823.622-810.597 -804.79-794.455 -791.24-779.757-738.156
-723.655-707.513-665.321    -625-610.105-571.522-560.531-514.961-466.568-459.613
-442.454-439.731-436.024-420.341-415.879-393.176-362.992-322.769-315.781-187.795
-120.735 -87.533 -87.434 -51.476 -48.425 -42.356 -39.665  21.161  91.035  97.146
  103.51 106.135 161.909 162.041  217.29 284.613 292.487 299.409   302.1 327.559
  872.89  869.12  860.87     850   844.2     836     830     824  822.95     824
     826     824     824  825.91  826.52  825.78  826.79  827.53     828     832
     834     835  834.62  832.98  832.86  834.98     836  837.22  840.87     842
  843.58  843.46  844.16  845.03     846  848.07  850.34  852.72  854.04  859.97
  861.73  863.02  865.44  865.81  867.25   867.2   867.2  867.09   865.8  865.62
  865.74  864.26  862.16  860.13  859.88  858.49  860.93  861.57     864     880
                                                                                
                                                                                
                                                                                
                                                                                
                                                  858.82  858.14   857.3
                                                                                
-1213.32-1207.31-1190.35-1172.17-1163.91-1149.63 -1136.9-1121.65-1113.71-1091.07
-971.293-885.597-830.413-823.622-810.597 -804.79-794.455 -791.24-779.757-738.156
-723.655-707.513-665.321    -625-610.105-571.522-560.531-514.961-466.568-459.613
-442.454-439.731-436.024-420.341-415.879-393.176-322.769-315.781-187.795-120.735
 -87.533 -87.434 -51.476 -48.425 -42.356 -39.665  21.161  69.488  91.035  97.146
  103.51 106.135 161.909 162.041  217.29 284.613 292.487 299.409   302.1 327.559
  872.89  869.12  860.87     850   844.2     836     830     824  822.95     824
     826     824     824  825.91  826.52  825.78  826.79  827.53     828     832
     834     835  834.62  832.98  832.86  834.98     836  837.22  840.87     842
  843.58  843.46  844.16  845.03     846  848.07  852.72  854.04  859.97  861.73
  863.02  865.44  865.81  867.25   867.2   867.2  867.09   866.2   865.8  865.62
  865.74  864.26  862.16  860.13  859.88  858.49  860.93  861.57     864     880
                                                                                
                                                                                
                                                                                
                                                                                
                                          858.65  858.61  857.58  858.53
                                                                                
Pier Skew, UpSta & Num, DnSta & Num=  ,27.03, 4 ,27.03, 4 , 0 , 0 , 0 ,,
       4       4     3.5     3.5
     800  821.28  821.29     900
       4       4     3.5     3.5
     800  821.28  821.29     900
BR Coef= 1 , 1 , 1 ,0.9, 0 ,,,0.8,-1,1.33,0,
WSPro=,,,, 1 ,,,, 0 ,,,, 0 ,,,,-1 ,-1 ,-1 , 0 , 0 , 0 , 0 , 0
BC Design=,, 0 ,, 0 ,,,,,,
BC Use User HTab Curves=0
BC User HTab FreeFlow(D)= 0

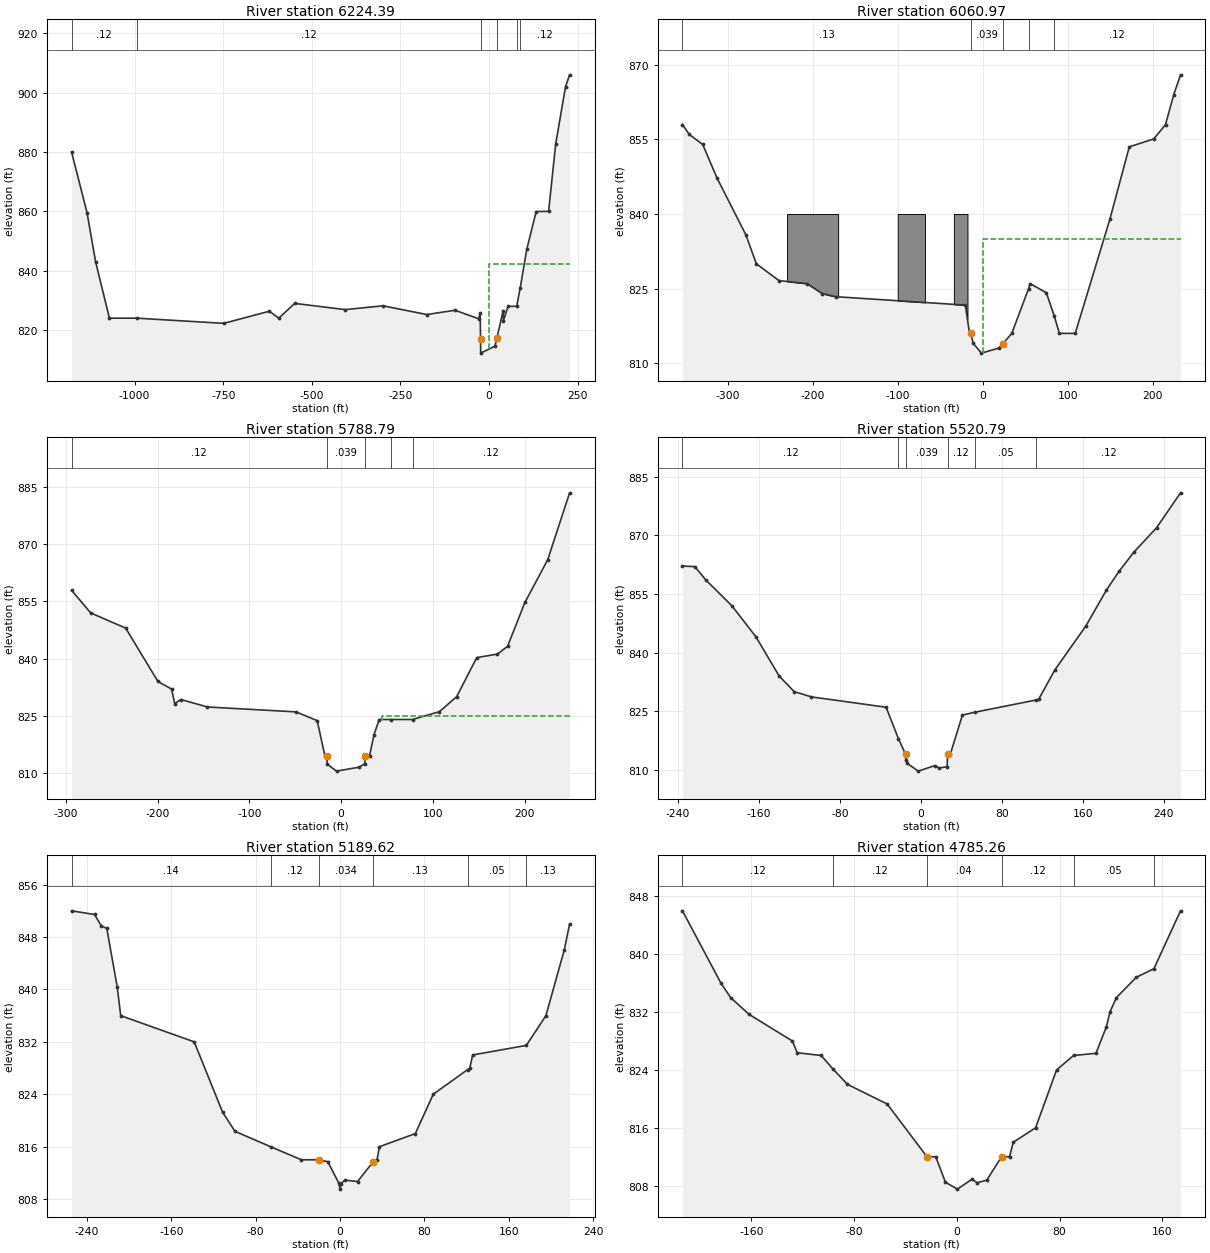
Type RM Length L Ch R = 1 ,6224.39 ,214.476,163.421,153.334
XS GIS Cut Line= 6
590323.1751357854386370.16689901590488.7729778324386582.12482163
590509.8072260924386613.28452601590535.0690504044386648.82725445
590555.0273546514386678.39285482590582.6788109934386710.71079922
#Sta/Elev= 30
-1178.01     880-1134.35  859.55-1110.26  843.04-1071.22     824-993.537     824
-748.688  822.25-619.718  826.34-593.209     824-548.327  828.98-405.676  826.88
-299.278  828.17-175.984  825.23 -95.702  826.66 -29.134  823.79 -24.902  825.75
  -23.93 816.846 -23.425  812.22  16.798  814.58  21.929 817.222  40.125  826.58
  40.814  823.13  53.675     828  78.051     828  87.894   834.1 106.529  847.18
 133.104  859.93 168.143     860 188.123  882.66 215.912     902 227.428     906
#Mann= 6 ,-1 , 0
-1178.01     .12       0-993.537     .12       0  -23.93    .039       0
  21.929     .13       0  78.051     .05       0  87.894     .12       0
#XS Ineff= 2 , 0
       0 -128.15  842.09               0
Permanent Ineff=
       F       F
Bank Sta=-23.93,21.929
XS Rating Curve= 0 ,0
Exp/Cntr=0.5,0.3

Type RM Length L Ch R = 1 ,6060.97 ,294.716,272.182,270.944
BEGIN DESCRIPTION:
Slightly adjusted  n to resolve drawdown
END DESCRIPTION:
Node Name=I
XS GIS Cut Line= 3
590409.5615528534386643.30123039590501.3612179874386688.50307094
590565.3661707794386729.62973545
#Sta/Elev= 30
-352.953     858-344.948     856-329.167     854-312.402  847.26-278.445  835.83
-266.142     830-239.567  826.62 -206.43     826-188.681     824-173.097  823.38
 -20.538  821.69 -15.551     816 -14.206     816 -11.216  813.98  -1.576  812.03
  18.824  813.04   23.71  813.93  34.088     816  53.773  824.97  55.676     826
  74.705  824.17  83.891  819.55  90.026     816 108.629     816 149.311  838.92
 172.178  853.52 200.984  855.11 214.764     858 224.409     864 232.382     868
#Mann= 5 ,-1 , 0
-352.953     .13       0 -14.206    .039       0   23.71     .13       0
  53.773      .1       0  83.891     .12       0
#XS Ineff= 2 , 0
       0    -162     835      56       0  825.85
Permanent Ineff=
       F       F
#Block Obstruct= 3 ,-1
    -100     -68     840    -230    -170     840     -34     -18     840
Bank Sta=-14.206,23.71
XS Rating Curve= 0 ,0
Exp/Cntr=0.3,0.1

Type RM Length L Ch R = 1 ,5788.79 ,267.983,267.995,269.718
Node Name=H
XS GIS Cut Line= 3
590385.503688556 4386733.1471275590420.8056249924386738.35311156
590533.6883063874386802.49217635
#Sta/Elev= 30
 -293.93  857.95 -273.13     852-234.908     848-199.803     834-184.908     832
 -181.43  828.17-174.738  829.25-145.768  827.29 -49.147     826 -26.115   823.7
 -17.717  814.42 -15.945  814.34  -15.04  812.24   -5.06  810.44   19.87  811.49
   25.92  812.44  26.017  814.33  30.971  814.47  35.794     820   41.47     824
   54.56     824  77.789     824 107.152  826.06 125.951     830 147.835  840.26
  170.44  841.19  181.43  843.22 200.328  854.74 225.262     866 249.081  883.54
#Mann= 5 ,-1 , 0
 -293.93     .12       0 -15.945    .039       0  26.017     .12       0
   54.56     .05       0  77.789     .12       0
#XS Ineff= 2 , 0
       0                      45       0     825
Permanent Ineff=
       F       F
Bank Sta=-15.945,26.017
XS Rating Curve= 0 ,0
Exp/Cntr=0.4,0.2

Type RM Length L Ch R = 1 ,5520.79 ,313.201,331.174,344.977
Node Name=G
XS GIS Cut Line= 2
590364.4724882964386799.48684832590494.1770818994386874.82731325
#Sta/Elev= 30
-235.597  862.16 -223.36     862-212.828  858.67-186.844     852-162.927     844
-140.059     834 -125.23     830-108.136  828.65 -34.383     826 -22.146  817.89
  -15.19     814  -14.95   812.4  -13.55  811.65   -2.65  809.64   13.49  811.03
    17.7  810.46   25.91  810.74  26.312     814  29.101     814   41.01     824
  53.412  824.73 113.976  827.86 116.273     828 132.316  835.53 163.091  846.84
 183.333     856 195.735  860.78 210.335  865.67 233.005     872 256.529   880.9
#Mann= 6 ,-1 , 0
-235.597     .12       0 -22.146     .12       0  -15.19    .039       0
  26.312     .12       0  53.412     .05       0 113.976     .12       0
Bank Sta=-15.19,26.312
XS Rating Curve= 0 ,0
Exp/Cntr=0.4,0.2

Type RM Length L Ch R = 1 ,5189.62 ,425.633,404.358,391.296
BEGIN DESCRIPTION:
Slightly lowered main channel n to resolve a drawdown
END DESCRIPTION:
Node Name=F
XS GIS Cut Line= 3
590311.6201676424386844.49666487590369.2517523554386922.07740983
590404.8036247944386953.32855422
#Sta/Elev= 30
-254.692     852-232.907  851.44-226.509   849.7-221.293  849.32-211.352  840.34
-208.071     836-138.386     832-111.385  821.24 -99.672  818.34  -66.01     816
 -36.713     814 -20.096     814 -11.634   813.7   -1.09  810.39    -.14  809.52
     .71  810.35    4.64   810.9   16.52  810.68   31.15  813.64  34.974     814
  37.369     816  71.358     818  88.353     824 120.997  827.77 122.933  827.96
 125.755     830  176.64  831.46  195.21     836 212.566     846 217.684  849.99
#Mann= 6 ,-1 , 0
-254.692     .14       0  -66.01     .12       0 -20.096    .034       0
   31.15     .13       0 120.997     .05       0  176.64     .13       0
Bank Sta=-20.096,31.15
XS Rating Curve= 0 ,0
Exp/Cntr=0.4,0.2

Type RM Length L Ch R = 1 ,4785.26 ,467.518,504.163,537.171
Node Name=J
XS GIS Cut Line= 3
590225.9835585844386937.68317002590256.1160869574386979.71204254
590306.6580235814387022.88391508
#Sta/Elev= 30
-213.583     846-183.629     836 -176.05     834-161.778  831.69-128.018     828
-124.245  826.38 -105.61     826 -96.358  824.12 -85.105     822 -54.199  819.29
 -23.261     812 -16.404     812   -8.88  808.48    .469  807.52   11.84  808.89
   15.78   808.4   23.29  808.76  34.908     812  41.076     812   43.93     814
  61.352     816   77.69     824  90.945     826 108.333   826.3 116.535     830
 119.193     832 124.245     834 139.764  836.81 153.478     838  174.18     846
#Mann= 6 ,-1 , 0
-213.583     .12       0 -96.358     .12       0 -23.261     .04       0
  34.908     .12       0  90.945     .05       0 153.478     .12       0
Bank Sta=-23.261,34.908
XS Rating Curve= 0 ,0
Exp/Cntr=0.3,0.1

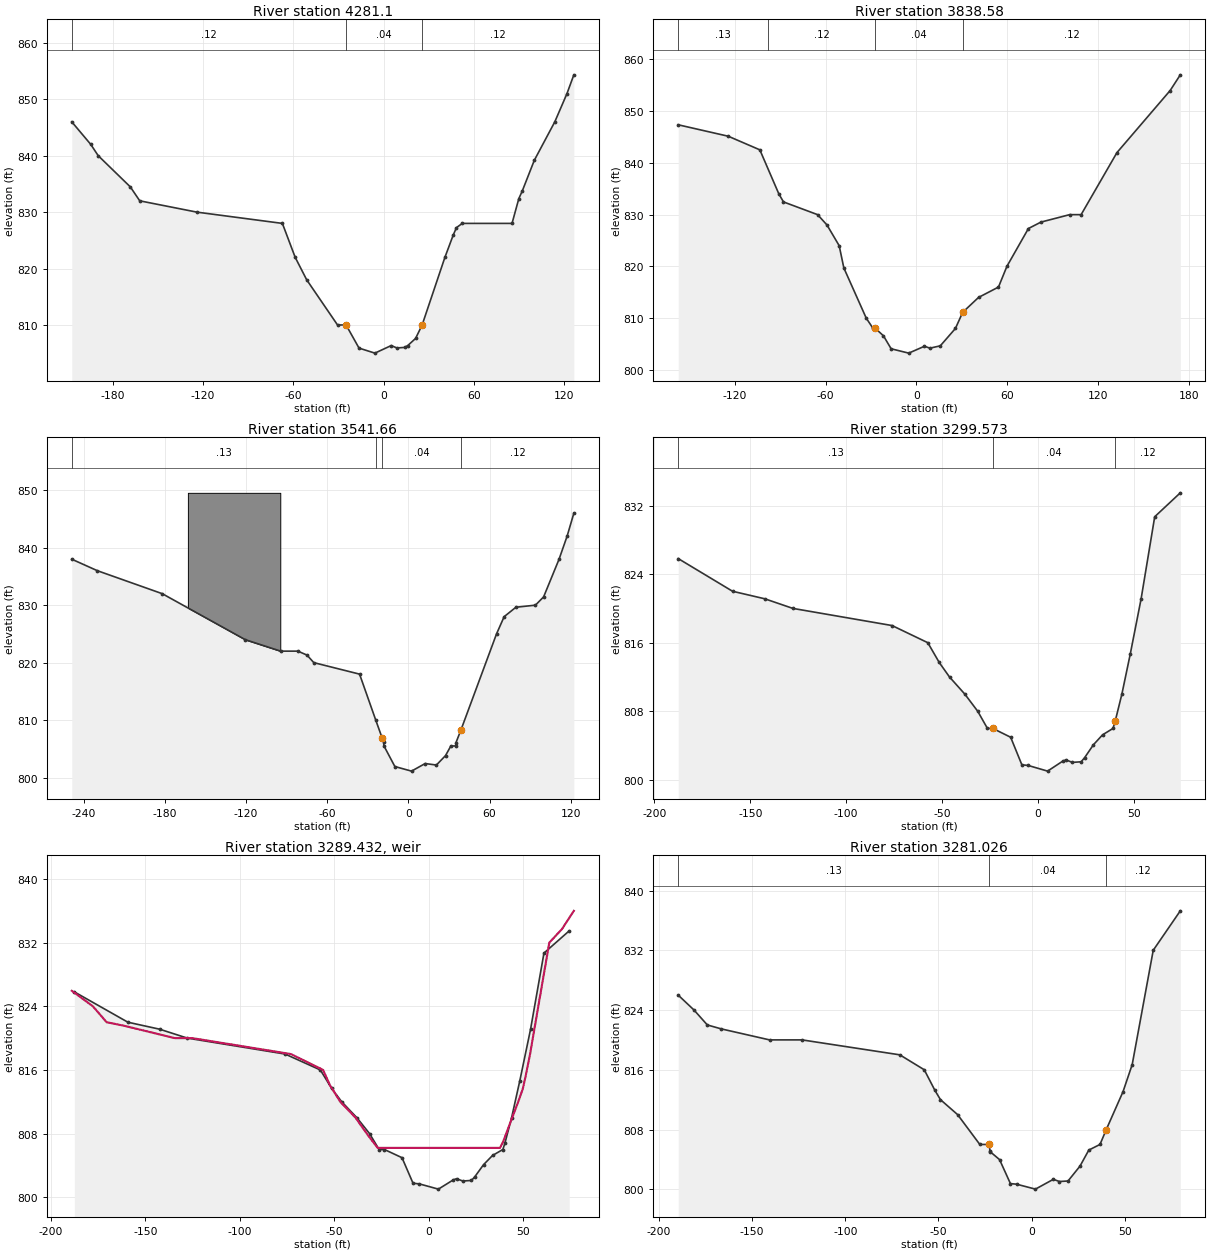
Type RM Length L Ch R = 1 ,4281.1  ,468.109,442.516,427.464
Node Name=I
XS GIS Cut Line= 3
590123.921277323 4386992.3399067 590135.01599746 4387024.6182271
590135.1348694614387092.25944393
#Sta/Elev= 30
-207.349     846-194.718     842-189.764     840-168.406  834.47-162.139     832
-124.213     830  -67.29     828 -58.793     822 -51.115     818  -30.61     810
 -24.934     810  -16.32   805.9   -5.76  805.01    5.08  806.35    8.84  805.93
   14.03  806.02      16  806.33   21.28  807.61  25.656     810  40.814     822
  46.424     826  48.491  827.25  52.329     828  85.433     828  89.961   832.4
  92.224  833.73 100.262  839.19 113.878     846 121.982  851.01 126.542  854.33
#Mann= 3 ,-1 , 0
-207.349     .12       0 -24.934     .04       0  25.656     .12       0
Bank Sta=-24.934,25.656
XS Rating Curve= 0 ,0
Exp/Cntr=0.3,0.1

Type RM Length L Ch R = 1 ,3838.58 ,300.624,296.924,294.52
Node Name=H
XS GIS Cut Line= 2
589985.1610756084387042.86965132590030.0123961624387133.34343644
#Sta/Elev= 30
-157.185  847.37 -124.18  845.16-103.346  842.53 -90.781     834  -87.73  832.46
 -65.223     830 -59.022     828 -50.984     824   -47.9  819.69 -33.136     810
 -28.609     808 -27.067     808  -21.75  806.57   -16.7  804.07   -5.09  803.23
    5.29  804.56    8.89  804.19   15.74  804.64  25.722     808  30.512  811.12
  40.978     814  54.134     816  59.678     820  73.885  827.32  82.152  828.56
 101.115     830 108.661     830 132.316     842 167.421     854 174.114  857.03
#Mann= 4 ,-1 , 0
-157.185     .13       0 -98.196     .12       0 -27.067     .04       0
  30.512     .12       0
Bank Sta=-27.067,30.512
XS Rating Curve= 0 ,0
Exp/Cntr=0.3,0.1

Type RM Length L Ch R = 1 ,3541.66 ,210.524,242.085,270.085
Node Name=G
XS GIS Cut Line= 3
  589911.68903474387061.89526756589910.7319626884387101.40039605
589947.9328031484387164.90852483
#Sta/Elev= 30
-248.786     838-229.888     836-181.923     832-120.571     824  -94.39     822
 -81.627     822 -74.902  821.31 -69.882     820 -36.056     818 -24.081     810
 -19.324  806.86 -18.307  806.19 -18.012   805.5-9.95999  801.92    2.36  801.12
   12.43  802.44   20.74802.1801   27.48  803.82   31.43   805.5  35.105   805.5
  35.203  806.07  38.976  808.34   65.19     825  70.833     828  79.528  829.64
   93.93     830     100  831.44 111.417     838 117.356     842 122.343     846
#Mann= 4 ,-1 , 0
-248.786     .13       0 -24.081     .12       0 -19.324     .04       0
  38.976     .12       0
#Block Obstruct= 1 ,-1
-162.959 -94.652  849.55
Bank Sta=-19.324,38.976
XS Rating Curve= 0 ,0
Exp/Cntr=0.5,0.3

Type RM Length L Ch R = 1 ,3299.573,18.682,18.546,18.476
XS GIS Cut Line= 3
589889.1704104214387090.30262791589868.8676821714387115.61017222
589855.1791140014387160.95831678
#Sta/Elev= 30
-187.566  825.81-159.252     822-142.421  821.12-127.789     820  -76.05     818
 -57.415     816 -51.444  813.69 -46.096     812 -38.091     810 -31.365     808
 -26.312     806 -23.491     806  -14.19  804.97   -8.36  801.76   -5.04  801.68
    5.06  801.02   12.86  802.17   14.65  802.33   17.97  802.04   22.56  802.11
   24.31  802.57   28.98   804.1  33.709  805.25  39.173     806  40.289  806.82
  43.799     810  48.163  814.66  53.839  821.12  60.925  830.69  74.278  833.48
#Mann= 3 ,-1 , 0
-187.566     .13       0 -23.491     .04       0  40.289     .12       0
Bank Sta=-23.491,40.289
XS Rating Curve= 0 ,0
Exp/Cntr=0.5,0.3

Type RM Length L Ch R = 5 ,3289.432,,,
IW Pilot Flow=0
#Inline Weir SE= 23
-188.944  825.95-177.756     824-170.505     822-160.663  821.52-134.449     820
-125.197     820 -73.031     818 -57.382  816.18 -55.938     816 -52.297  814.07
  -46.85     812  -38.78     810 -32.021  807.73 -27.067   806.2  37.664   806.2
  39.272  806.96   47.31     812  49.672  813.58  51.247  815.26  53.576     818
  63.747     832  70.505  833.72  76.739     836
IW Dist,WD,Coef,Skew,MaxSub,Min_El,Is_Ogee,SpillHt,DesHd
1,2,2.6,0,0.98,, 0 ,,,0,0,

Type RM Length L Ch R = 1 ,3281.026,175.546,199.276,226.721
XS GIS Cut Line= 3
589884.8849223694387087.01383587589863.8567701094387113.22663619
589849.8298739354387159.68730077
#Sta/Elev= 30
-189.665  825.99-181.201     824-174.049     822-166.503  821.47 -140.65     820
-123.196     820 -70.735     818 -57.612     816  -51.87  813.23 -48.917     812
 -39.731     810 -27.789     806 -22.802     806  -22.31  805.14  -22.08     805
  -17.19  803.97  -11.36  800.76   -8.04  800.68    2.06  800.02   11.65  801.33
   14.97  801.04   19.56  801.11   25.98   803.1  30.709  805.25  36.713     806
  40.092     808  49.081  813.07  54.003   816.7  65.289     832  79.823  837.28
#Mann= 3 ,-1 , 0
-189.665     .13       0 -22.802     .04       0  40.092     .12       0
Bank Sta=-22.802,40.092
XS Rating Curve= 0 ,0
Exp/Cntr=0.5,0.3