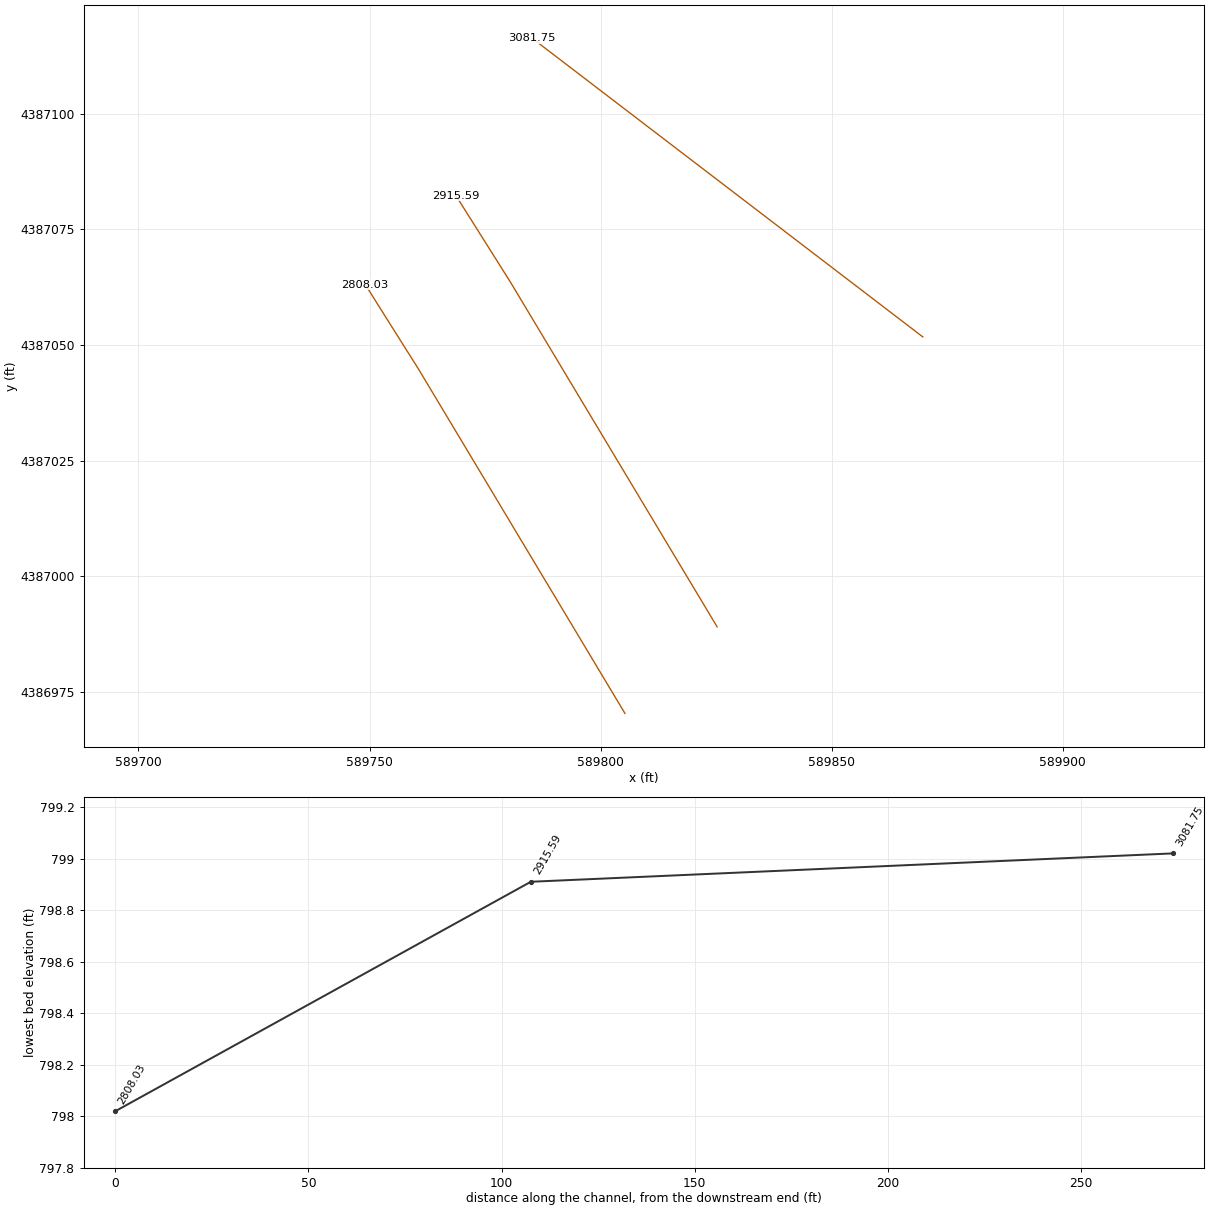
HEC-RAS study Deckers_Creek_Detail_Study.prj: Deckers_Creek_Detail_Study

--- Deckers_Creek_Detail_Study.g01 (geometry) --- (continued)

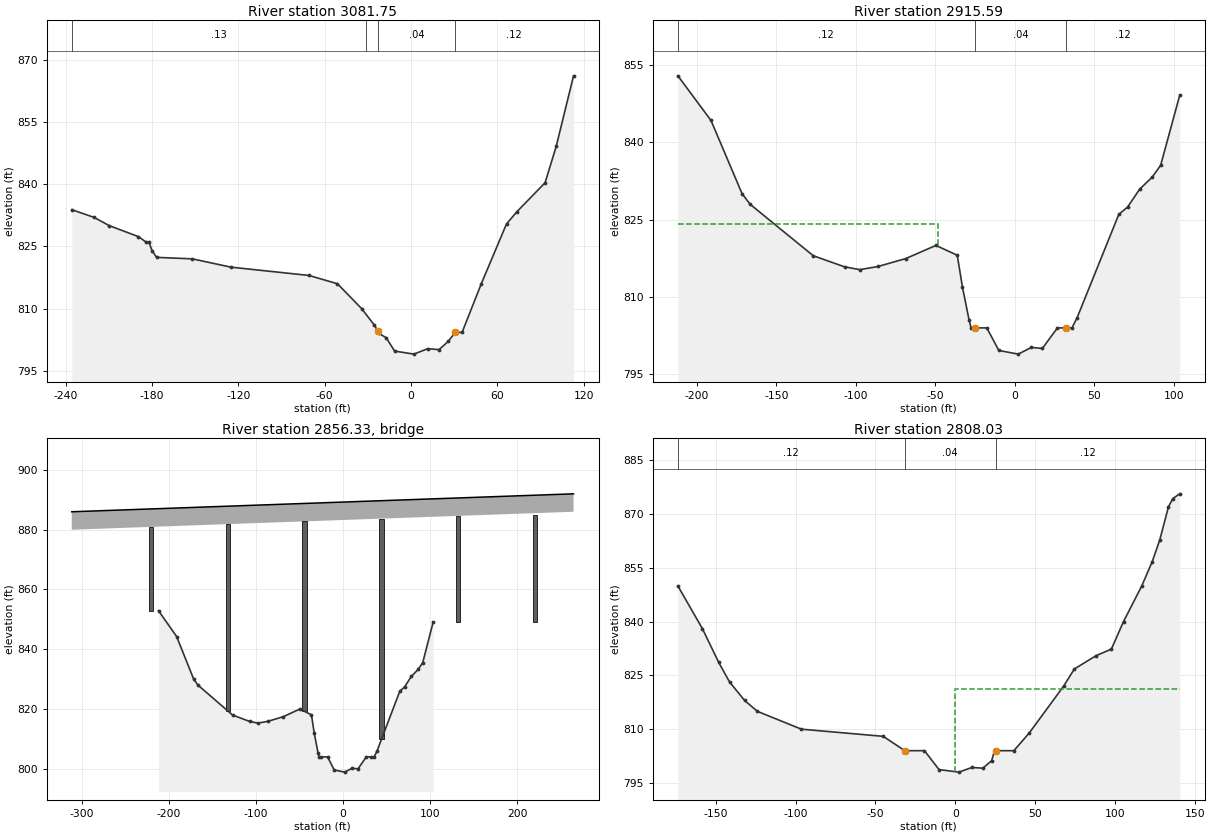
Type RM Length L Ch R = 1 ,3081.75 ,178.67,166.162,148.208
Node Name=F
XS GIS Cut Line= 2
589869.7028341814387051.76981143589785.2031291374387116.30206823
#Sta/Elev= 30
-235.794  833.86-220.243     832-209.646     830-189.403  827.36-183.924     826
-182.119     826-179.987     824-176.837  822.36-151.936     822-125.164     820
 -70.932     818 -51.115     816 -34.285     810 -25.394     806  -23.13  804.63
  -22.08     804  -17.19  802.97  -11.36  799.76    2.06  799.02   11.65  800.33
   19.56  800.11   25.98   802.1  30.709  804.25  35.564  804.28  48.917     816
  66.437  830.43  73.753  833.41  93.241  840.36 100.984  849.12 113.025  866.15
#Mann= 4 ,-1 , 0
-235.794     .13       0 -31.266     .12       0  -23.13     .04       0
  30.709     .12       0
Bank Sta=-23.13,30.709
XS Rating Curve= 0 ,0
Exp/Cntr=0.5,0.3

Type RM Length L Ch R = 1 ,2915.59 ,118.957,107.563,108.635
XS GIS Cut Line= 3
589825.1959376314386989.10293066589780.5335930794387063.52289958
589768.7225929334387082.24981181
#Sta/Elev= 30
 -211.96   852.9-191.161  844.25-171.549     830 -166.48  827.97-126.851     818
-107.182  815.85 -97.565   815.3 -86.151  815.91 -68.654  817.45  -49.68     820
 -36.268  818.09 -33.024  811.93 -28.795  805.47 -27.578     804  -25.26     804
   -17.7     804 -10.154  799.63    2.04  798.91  10.357  800.21  17.217  800.01
  26.737     804  32.154     804  35.863     804  39.136     806  65.294     826
  70.885  827.46  78.475  830.92  86.296  833.24  91.626  835.54  103.59  849.09
#Mann= 3 ,-1 , 0
 -211.96     .12       0  -25.26     .04       0  32.154     .12       0
#XS Ineff= 2 , 0
         -48.421  824.08
Permanent Ineff=
       F       F
Bank Sta=-25.26,32.154
XS Rating Curve= 0 ,0
Skew Angle= 28
Exp/Cntr=0.5,0.3

Type RM Length L Ch R = 3 ,2856.33 ,,,
BEGIN DESCRIPTION:
WV-7 / Walnut Street - Field Recon ID Deck 3
100 ft pier spacing assumed
END DESCRIPTION:
Bridge Culvert--1,0,-1,-1, 0
Deck Dist Width WeirC Skew NumUp NumDn MinLoCord MaxHiCord MaxSubmerge Is_Ogee
33,46,2.6,28, 2, 2, , , 0.98, 0, 0,0,,
 -311.68 264.884
     886     892
     880     886
 -311.68 264.884
     886     892
     880     886
Pier Skew, UpSta & Num, DnSta & Num=  ,-220.737, 2 ,-220.737, 2 , 0 , 0 , 0 ,,
       5       5
     780     885
       5       5
     780     885
Pier Skew, UpSta & Num, DnSta & Num=  ,-132.442, 2 ,-132.442, 2 , 0 , 0 , 0 ,,
       5       5
     780     885
       5       5
     780     885
Pier Skew, UpSta & Num, DnSta & Num=  ,-44.147, 2 ,-44.147, 2 , 0 , 0 , 0 ,,
       5       5
     780     885
       5       5
     780     885
Pier Skew, UpSta & Num, DnSta & Num=  ,44.147, 2 ,44.147, 2 , 0 , 0 , 0 ,,
       5       5
     780     885
       5       5
     780     885
Pier Skew, UpSta & Num, DnSta & Num=  ,132.442, 2 ,132.442, 2 , 0 , 0 , 0 ,,
       5       5
     780     885
       5       5
     780     885
Pier Skew, UpSta & Num, DnSta & Num=  ,220.737, 2 ,220.737, 2 , 0 , 0 , 0 ,,
       5       5
     780     885
       5       5
     780     885
BR Coef=-1 , 1 , 1 ,1.25, 0 ,,,0.8,-1,2,0,
WSPro=,,,, 1 ,,,, 0 ,,,, 0 ,,,,-1 ,-1 ,-1 , 0 , 0 , 0 , 0 , 0
BC Design=,, 0 ,, 0 ,,,,,,
BC Use User HTab Curves=0
BC User HTab FreeFlow(D)= 0

Type RM Length L Ch R = 1 ,2808.03 ,262.316,276.7,282.947
XS GIS Cut Line= 3
589805.2498253844386970.40345043589760.7276888344387044.59481934
 589749.059944694387063.09617957
#Sta/Elev= 30
-173.663  849.94-158.282     838-148.172  828.67-141.364  823.19-131.892     818
-123.868  814.96 -96.377     810 -45.161     808 -31.663     804 -19.351     804
 -10.242  798.73   2.181  798.02  10.392  799.32  17.182  799.12  22.683  801.21
  24.478     804  25.173     804  36.587     804  46.117  808.88  67.727     822
  74.448  826.79  88.005  830.49  97.622  832.33 105.212  840.02 116.683     850
 123.144  856.69 127.865  862.72  133.34     872 135.977  874.28 140.351  875.64
#Mann= 3 ,-1 , 0
-173.663     .12       0 -31.663     .04       0  25.173     .12       0
#XS Ineff= 2 , 0
       0 -41.692   821.2               0
Permanent Ineff=
       F       F
Bank Sta=-31.663,25.173
XS Rating Curve= 0 ,0
Skew Angle= 28
Exp/Cntr=0.5,0.3