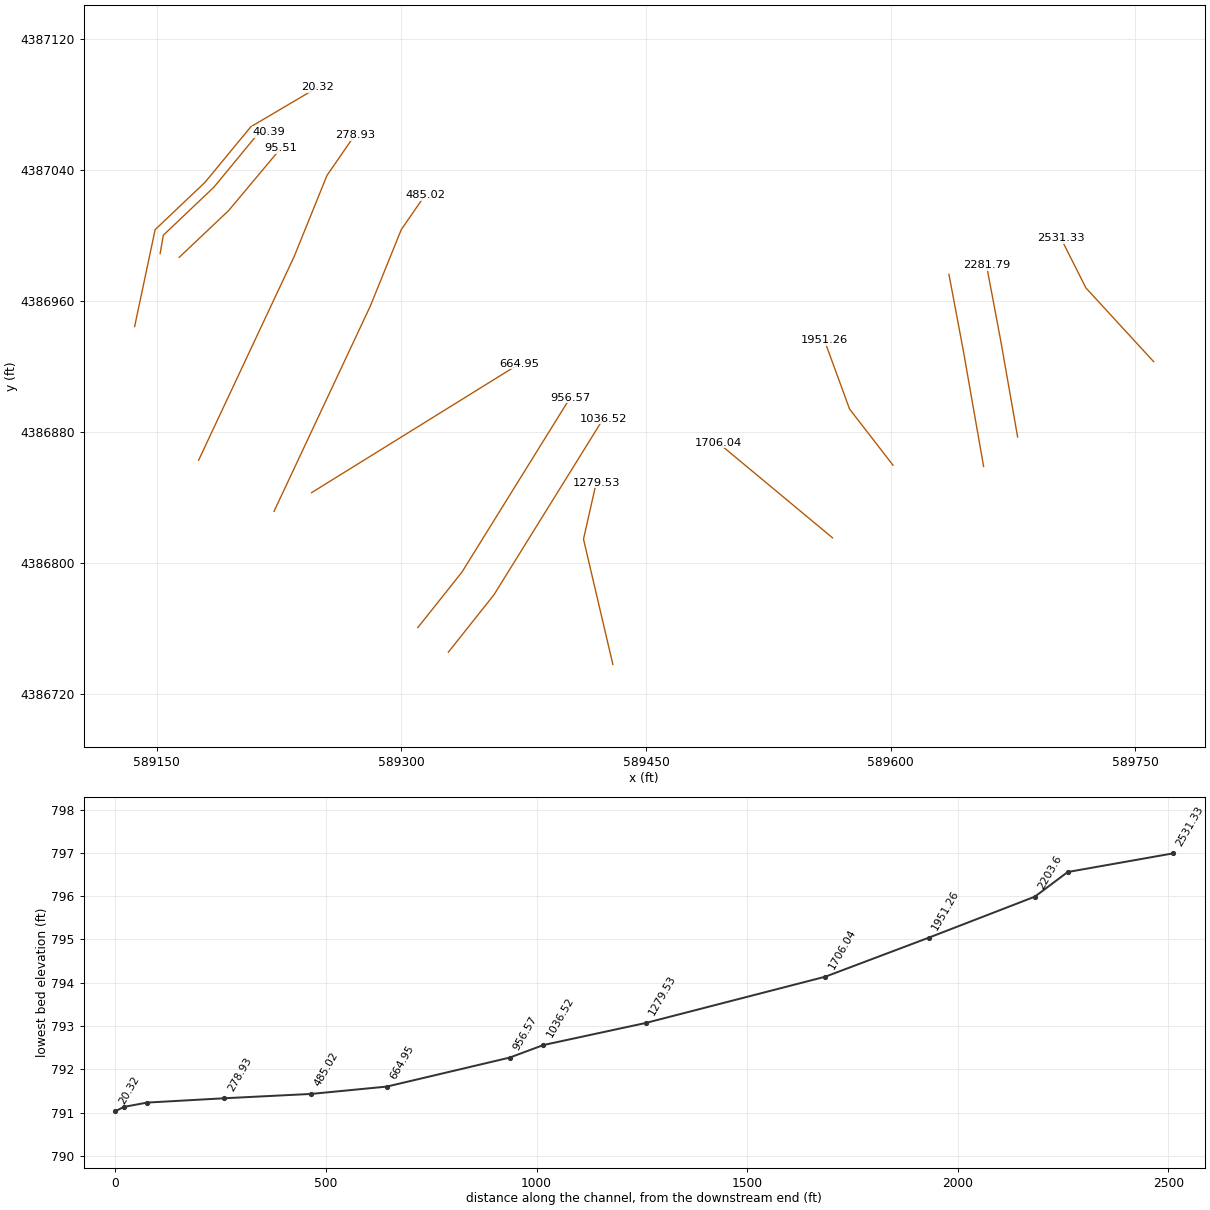
HEC-RAS study Deckers_Creek_Detail_Study.prj: Deckers_Creek_Detail_Study

--- Deckers_Creek_Detail_Study.g01 (geometry) --- (continued)

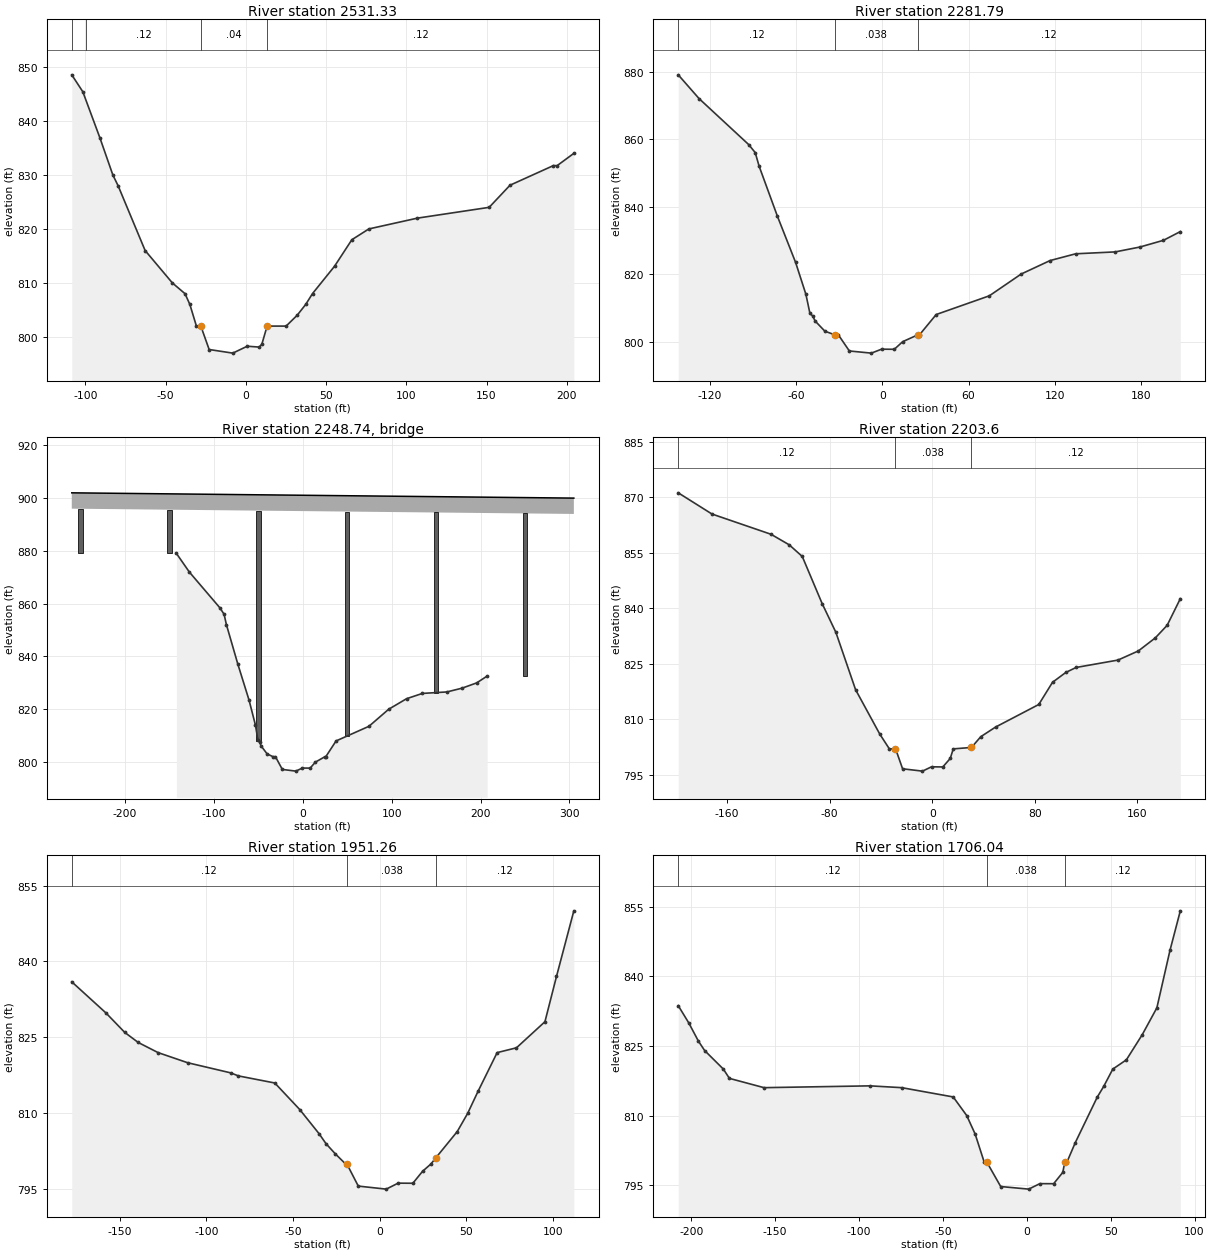
Type RM Length L Ch R = 1 ,2531.33 ,271.234,249.538,225.809
Node Name=E
XS GIS Cut Line= 3
589761.3311928424386923.03143384589719.814384328 4386968.0534424
589704.4250321384386998.48772278
#Sta/Elev= 30
-108.432  848.55-101.542  845.41 -90.945  836.91 -82.841     830  -79.56     828
  -62.73     816 -45.768     810 -37.861     808 -34.843     806 -30.774     802
 -28.018     802  -22.84  797.66   -8.11  796.99.9099998  798.27    8.35  798.11
    9.99  798.63  13.287     802  25.131     802  31.988     804  37.303     806
  41.568  808.02  55.282  813.08  66.076     818  76.673     820 106.923     822
  151.64     824 164.633   828.1 191.699  831.74 193.963  831.72 204.396     834
#Mann= 4 ,-1 , 0
-108.432     .13       0 -99.475     .12       0 -28.018     .04       0
  13.287     .12       0
Bank Sta=-28.018,13.287
XS Rating Curve= 0 ,0
Exp/Cntr=0.5,0.3

Type RM Length L Ch R = 1 ,2281.79 ,78.22,78.187,79.181
XS GIS Cut Line= 3
589677.9165758114386876.98224927589667.7911196864386934.54982599
589658.8452395754386981.83954657
#Sta/Elev= 30
-142.224  879.04-127.723     872 -93.209  858.39 -88.615     856 -85.925     852
 -73.097  837.07 -60.499  823.46 -53.314     814 -50.492  808.31 -48.622  807.61
 -46.883  806.08 -40.092  803.06 -33.301     802 -30.741     802  -23.05   797.2
   -7.73  796.56-.599999  797.73    8.26   797.7   14.11  799.96  24.738     802
   25.82     802  37.434     808  74.409  813.54  96.621     820 116.765     824
  134.58     826 162.106  826.56 179.265     828 195.735     830 207.448  832.58
#Mann= 3 ,-1 , 0
-142.224     .12       0 -33.301    .038       0  24.738     .12       0
Bank Sta=-33.301,24.738
XS Rating Curve= 0 ,0
Exp/Cntr=0.5,0.3

Type RM Length L Ch R = 3 ,2248.74 ,,,
BEGIN DESCRIPTION:
Pleasant Street - Field Recon ID Deck 4
100 ft pier spacing assumed
END DESCRIPTION:
Bridge Culvert--1,0,-1,-1, 0
Deck Dist Width WeirC Skew NumUp NumDn MinLoCord MaxHiCord MaxSubmerge Is_Ogee
7.5,45,2.6,0, 2, 2, , , 0.98, 0, 0,0,,
    -260     305
     902     900
     896     894
    -260     305
     902     900
     896     894
Pier Skew, UpSta & Num, DnSta & Num=  ,-250, 2 ,-250, 2 , 0 , 0 , 0 ,,
       5       5
     780     900
       5       5
     780     900
Pier Skew, UpSta & Num, DnSta & Num=  ,-150, 2 ,-150, 2 , 0 , 0 , 0 ,,
       5       5
     780     900
       5       5
     780     900
Pier Skew, UpSta & Num, DnSta & Num=  ,-50, 2 ,-50, 2 , 0 , 0 , 0 ,,
       5       5
     780     900
       5       5
     780     900
Pier Skew, UpSta & Num, DnSta & Num=  ,50, 2 ,50, 2 , 0 , 0 , 0 ,,
       5       5
     780     900
       5       5
     780     900
Pier Skew, UpSta & Num, DnSta & Num=  ,150, 2 ,150, 2 , 0 , 0 , 0 ,,
       5       5
     780     900
       5       5
     780     900
Pier Skew, UpSta & Num, DnSta & Num=  ,250, 2 ,250, 2 , 0 , 0 , 0 ,,
       5       5
     780     900
       5       5
     780     900
BR Coef=-1 , 1 , 1 ,1.25, 0 ,,,0.8,-1,2,0,
WSPro=,,,, 1 ,,,, 0 ,,,, 0 ,,,,-1 ,-1 ,-1 , 0 , 0 , 0 , 0 , 0
BC Design=,, 0 ,, 0 ,,,,,,
BC Use User HTab Curves=0
BC User HTab FreeFlow(D)= 0

Type RM Length L Ch R = 1 ,2203.6  ,246.327,252.341,263.655
XS GIS Cut Line= 3
589657.0682555534386858.93504105589644.6232713994386929.68826592
 589635.79626329 4386976.3500985
#Sta/Elev= 30
-198.064   871.2-171.752  865.47-125.722     860-111.483  857.14-101.345     854
  -85.86  841.28 -75.131  833.49 -59.777     818 -40.912     806 -33.432     802
 -29.364     802 -28.576     802  -23.12  796.62   -7.61  795.99    -.55  797.16
    8.23  797.12   14.03  799.41  16.404     802   30.61  802.39  37.828  805.29
  49.344  807.89  83.071     814  93.799     820 104.134  822.65 112.139     824
 144.816     826 160.761  828.48  173.95     832 183.169  835.39 193.438   842.6
#Mann= 3 ,-1 , 0
-198.064     .12       0 -29.364    .038       0   30.61     .12       0
Bank Sta=-29.364,30.61
XS Rating Curve= 0 ,0
Exp/Cntr=0.5,0.3

Type RM Length L Ch R = 1 ,1951.26 ,233.051,245.225,267.275
Node Name=D
XS GIS Cut Line= 3
589601.4910228664386859.73361706589574.8393105374386894.05104948
589559.419478346  4386936.092114
#Sta/Elev= 30
-177.526  835.98-157.776  829.82-147.014     826-139.206     824-127.756     822
-110.696     820 -85.892     818 -81.463   817.4 -60.466     816 -46.096  810.76
 -34.974     806 -30.906     804 -25.558     802 -19.619     800 -18.898     800
  -12.34  795.64    3.78  795.04   10.62  796.22   19.13   796.2   24.75  798.57
  29.528     800  32.513  801.28  44.718  806.41  50.722     810   56.66  814.32
  67.717     822  78.871  822.95  95.276   828.1 101.936  837.04 111.942     850
#Mann= 3 ,-1 , 0
-177.526     .12       0 -18.898    .038       0  32.513     .12       0
Bank Sta=-18.898,32.513
XS Rating Curve= 0 ,0
Exp/Cntr=0.3,0.1

Type RM Length L Ch R = 1 ,1706.04 ,457.346,426.509,403.491
Node Name=C
XS GIS Cut Line= 2
589564.3999104084386815.35473651589494.1221735394386873.53191323
#Sta/Elev= 30
-207.808  833.67-201.608     830-195.735     826 -192.06     824-180.906     820
-177.297     818 -156.66     816 -93.471  816.39 -74.541     816 -43.865     814
 -35.827     810 -30.774     806 -25.427     800 -23.885     800  -15.55   794.7
    1.15  794.14    7.78  795.32   16.03  795.31   21.49  797.76  22.671     800
  23.983     800  28.937  804.17  42.028  813.97  45.866  816.27   51.28     820
  59.383     822  68.832  827.41  77.559   833.2  85.367  845.57  91.535   854.1
#Mann= 3 ,-1 , 0
-207.808     .12       0 -23.885    .038       0  22.671     .12       0
Bank Sta=-23.885,22.671
XS Rating Curve= 0 ,0
Exp/Cntr=0.3,0.1

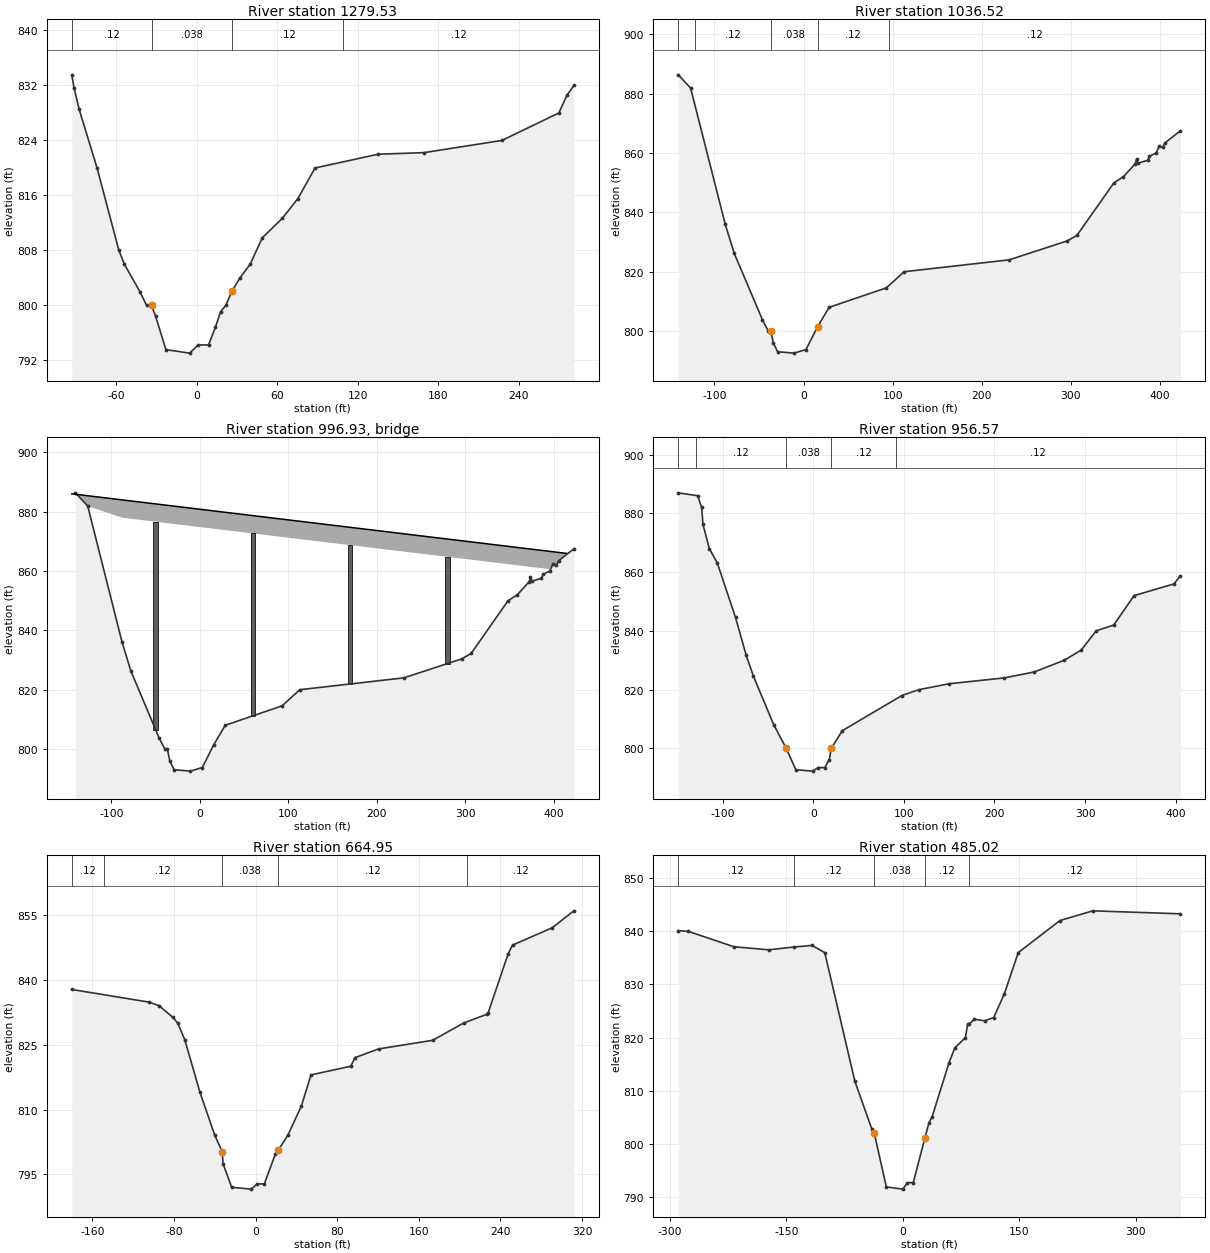
Type RM Length L Ch R = 1 ,1279.53 ,278.188,243.01,217.203
Node Name=B
XS GIS Cut Line= 3
589429.6630687424386738.00868756 589411.64938852 4386814.5653045
589419.5010366174386849.13267293
#Sta/Elev= 30
  -93.11  833.55 -91.339   831.6 -87.566  828.51 -74.245     820 -57.972     808
 -53.871     806  -42.29     802 -37.303     800 -33.629     800  -30.62  798.44
  -22.92  793.58   -5.21  793.07    1.07  794.26    8.87  794.26   14.03  796.86
    17.8  799.09  21.654     800  26.378  802.09  32.185     804  39.895     806
  48.885  809.84  63.878  812.68  75.492  815.56  88.255     820 135.236     822
 169.357  822.23 227.461     824 270.013     828 276.083  830.58 281.201     832
#Mann= 4 ,-1 , 0
  -93.11     .12       0 -33.629    .038       0  26.378     .12       0
 109.416     .12       0
Bank Sta=-33.629,26.378
XS Rating Curve= 0 ,0
Exp/Cntr=0.5,0.3

Type RM Length L Ch R = 1 ,1036.52 ,80.64,79.943,82.557
XS GIS Cut Line= 3
589328.7620754954386745.50981565589356.7213798414386780.52828808
 589423.826148674386888.20193741
#Sta/Elev= 30
-140.584  886.36-126.706   881.9 -87.861     836 -77.789  826.22 -46.161  803.83
 -39.567     800 -36.647     800  -34.04  796.09  -29.13  793.04  -10.84  792.56
    2.77  793.77  15.682  801.41  28.707     808  92.913  814.56 112.927     820
 230.676     824 296.063  830.41 306.627  832.21 348.327     850 358.858     852
 372.342  856.45 373.622     858 375.098  856.56 386.089  857.55 387.959   858.9
 395.604     860 398.917  862.27 402.953  861.92 405.676  863.48 422.703  867.48
#Mann= 5 ,-1 , 0
-140.584     .12       0-121.457     .12       0 -36.647    .038       0
  15.682     .12       0  95.965     .12       0
Bank Sta=-36.647,15.682
XS Rating Curve= 0 ,0
Exp/Cntr=0.5,0.3

Type RM Length L Ch R = 3 ,996.93  ,,,
BEGIN DESCRIPTION:
High Street - Field Recon ID Deck 2B
Pier spacing apprximate
END DESCRIPTION:
Bridge Culvert--1,0,-1,-1, 0
Deck Dist Width WeirC Skew NumUp NumDn MinLoCord MaxHiCord MaxSubmerge Is_Ogee
19.6,45,2.6,0, 4, 4, , , 0.98, 0, 0,0,,
-144.718    -144     413 413.944
     886     886     866     866
             880     860
-144.718    -144     413 413.944
     886     886     866     866
             880     860
Pier Skew, UpSta & Num, DnSta & Num=  ,-50, 2 ,-50, 2 , 0 , 0 , 0 ,,
       5       5
     780     890
       5       5
     780     890
Pier Skew, UpSta & Num, DnSta & Num=  ,60, 2 ,60, 2 , 0 , 0 , 0 ,,
       5       5
     780     890
       5       5
     780     890
Pier Skew, UpSta & Num, DnSta & Num=  ,170, 2 ,170, 2 , 0 , 0 , 0 ,,
       5       5
     780     890
       5       5
     780     890
Pier Skew, UpSta & Num, DnSta & Num=  ,280, 2 ,280, 2 , 0 , 0 , 0 ,,
       5       5
     780     890
       5       5
     780     890
BR Coef=-1 , 1 , 1 ,0.9, 0 ,,,0.8,-1,1.2,0,
WSPro=,,,, 1 ,,,, 0 ,,,, 0 ,,,,-1 ,-1 ,-1 , 0 , 0 , 0 , 0 , 0
BC Design=,, 0 ,, 0 ,,,,,,
BC Use User HTab Curves=0
BC User HTab FreeFlow(D)= 0

Type RM Length L Ch R = 1 ,956.57  ,306.276,291.625,279.778
XS GIS Cut Line= 3
589310.0046832644386760.48463983589337.0922595984386794.40888025
589403.4594124194386900.89685757
#Sta/Elev= 30
-148.983  886.98-127.657     886-123.097     882-121.719  876.29-114.698     868
-105.807  863.06 -85.761  844.57 -74.016  831.73 -66.043   824.6 -43.537     808
 -29.724     800   -19.2  792.74    -.71  792.27    5.29  793.47   12.74  793.48
   17.67  796.19  19.948     800  31.923     806  97.802     818 116.699     820
 149.869     822 210.892     824 243.668     826 276.936     830 295.571  833.42
 312.303     840  331.66     842 354.068     852  398.13     856 405.085  858.71
#Mann= 5 ,-1 , 0
-148.983     .12       0-128.937     .12       0 -29.724    .038       0
  19.948     .12       0  91.765     .12       0
Bank Sta=-29.724,19.948
XS Rating Curve= 0 ,0
Exp/Cntr=0.5,0.3

Type RM Length L Ch R = 1 ,664.95  ,157.731,179.927,199.168
Node Name=A
XS GIS Cut Line= 2
589244.8902584594386842.96961685589372.5100200364386921.79394583
#Sta/Elev= 30
-180.151  837.74-104.528  834.83 -94.652     834  -80.84  831.27 -76.083  829.92
 -69.193     826  -54.56     814 -39.895     804  -32.71  800.26  -31.79  797.45
  -23.45  792.03   -4.27   791.6    1.48   792.8    8.63  792.82   19.52   799.8
  22.146  800.59  31.529     804  44.882   810.8  54.331     818  93.241     820
  97.572     822 120.505     824  173.72     826  203.97     830  226.64     832
 227.822  832.24 247.605     846 251.903     848 290.748     852 311.975  855.92
#Mann= 5 ,-1 , 0
-180.151     .12       0-148.458     .12       0  -32.71    .038       0
  22.146     .12       0 207.612     .12       0
Bank Sta=-32.71,22.146
XS Rating Curve= 0 ,0
Exp/Cntr=0.5,0.3

Type RM Length L Ch R = 1 ,485.02  ,205.516,206.093,212.352
XS GIS Cut Line= 4
589221.8534741744386831.55790471589280.8718989044386956.89776226
589299.8700831384387003.65103484 589314.56144332 4387024.8742591
#Sta/Elev= 30
-289.048  840.15 -275.84     840 -217.44  837.11 -172.52  836.53-140.237  837.06
-116.829  837.36-100.402     836 -61.709  811.76 -39.624  802.67 -36.674  801.94
 -21.157  791.84       0  791.43   6.043  792.64  13.554  792.67  28.282 800.978
  33.784  803.98  37.699  805.04  59.212  815.12  66.823     818  80.634     820
  83.552  822.62  85.688  822.56  92.187  823.45 105.455  823.15  117.04  823.77
 130.789  828.25 148.571     836 202.336  842.05  244.67  843.88 357.256  843.32
#Mann= 5 ,-1 , 0
-289.048     .12       0-140.237     .12       0 -36.674    .038       0
  28.282     .12       0  85.688     .12       0
Bank Sta=-36.674,28.282
XS Rating Curve= 0 ,0
Skew Angle= 23.5
Exp/Cntr=0.5,0.3

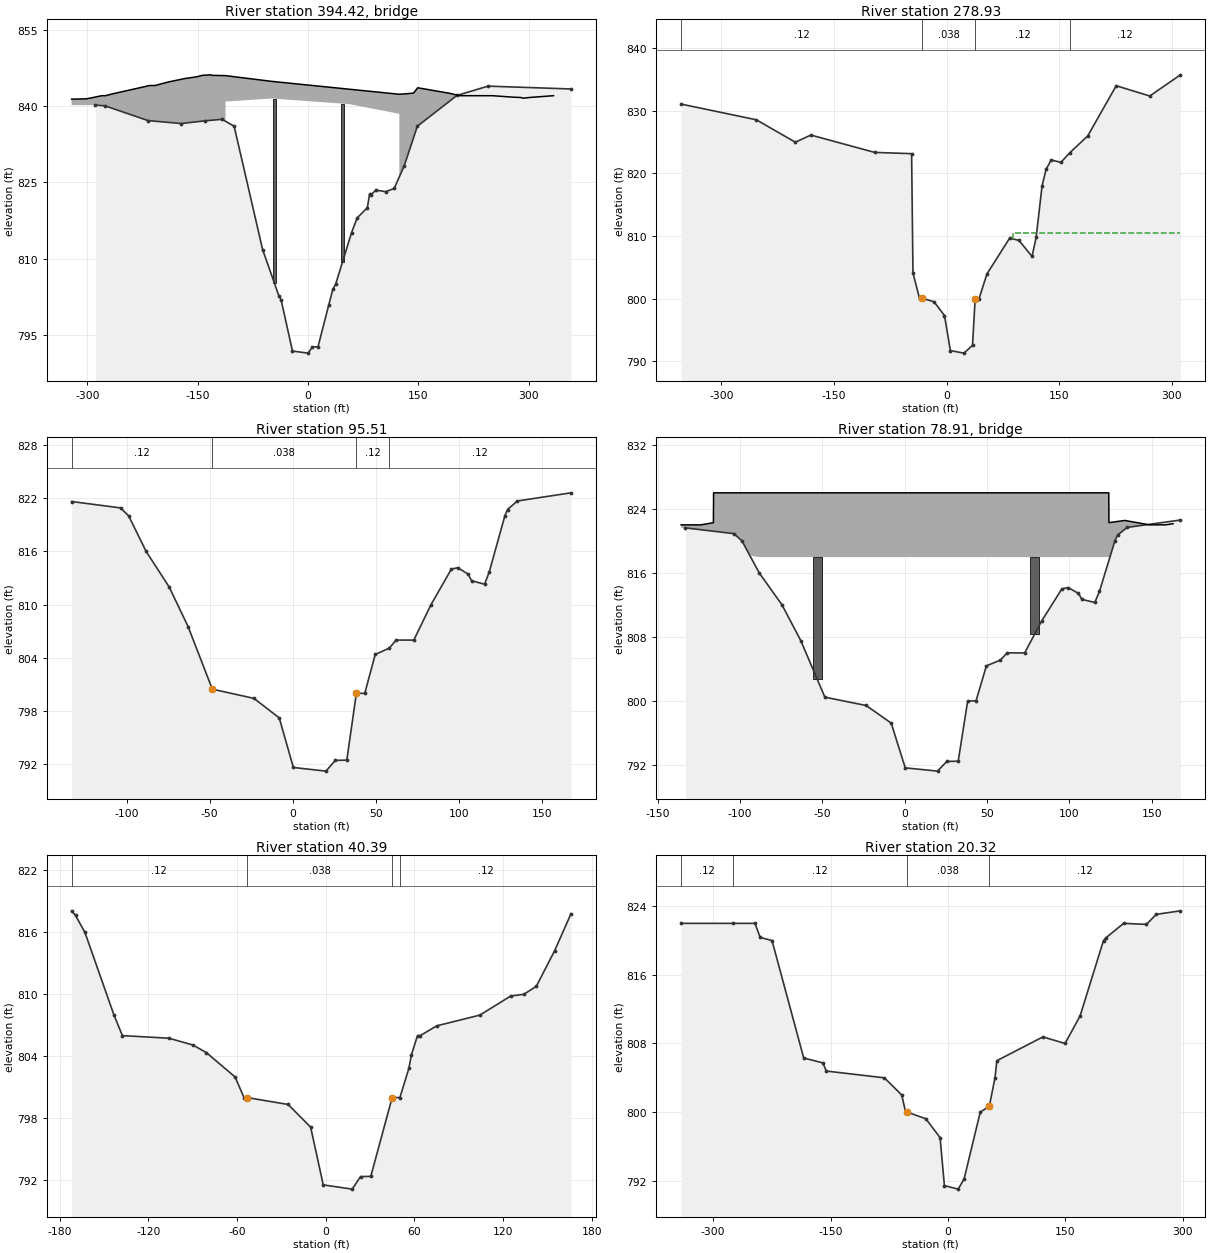
Type RM Length L Ch R = 3 ,394.42  ,,,
BEGIN DESCRIPTION:
University Avenue - Survey ID  Dec_1X
END DESCRIPTION:
Bridge Culvert--1,0,-1,-1, 0
Deck Dist Width WeirC Skew NumUp NumDn MinLoCord MaxHiCord MaxSubmerge Is_Ogee
50,75,2.6,23.5, 61, 61, , , 0.98, 0, 0,0,,
-321.242-300.753-300.542-289.259-280.354-279.962 -279.48-278.969-278.367-276.803
-275.329-271.387-267.747-215.244-212.416-208.053-188.979-168.098-152.543 -151.94
-143.516-132.083-130.609-112.156 -49.389  56.169 124.078 143.276 149.053 187.173
 187.895 188.557 189.219 189.851 190.452  193.07 193.581  196.47 196.831  200.02
 200.442 204.112 205.286 206.278  206.97 219.306 226.197 226.798 231.702 232.364
 237.238   237.9 242.714 243.467 248.189 250.296 279.872 288.747  293.11 300.993
 333.608
  841.32  841.39   841.4  841.73     842     842     842     842     842     842
     842  842.14  842.29     844     844     844  844.72  845.35  845.69  845.69
     846   846.1     846 845.942 844.814 843.272  842.28   842.5  843.56   842.6
  842.59  842.57  842.56  842.55  842.54  842.45  842.43  842.33  842.32  842.21
   842.2  842.08  842.03     842     842     842     842     842     842     842
     842     842     842     842     842     842   841.7  841.65  841.51  841.65
     842
                                                                                
                                                                                
                          840.85  841.45  840.34  838.44
                                                                                
                                                                                
                                                                                
        
-321.242-300.753-300.542-289.259-280.354-279.962 -279.48-278.969-278.367-276.803
-275.329-271.387-267.747-215.244-212.416-208.053-188.979-168.098-152.543 -151.94
-143.516-132.083-130.609-112.156 -49.389  56.169 124.078 143.276 149.053 187.173
 187.895 188.557 189.219 189.851 190.452  193.07 193.581  196.47 196.831  200.02
 200.442 204.112 205.286 206.278  206.97 219.306 226.197 226.798 231.702 232.364
 237.238   237.9 242.714 243.467 248.189 250.296 279.872 288.747  293.11 300.993
 333.608
  841.32  841.39   841.4  841.73     842     842     842     842     842     842
     842  842.14  842.29     844     844     844  844.72  845.35  845.69  845.69
     846   846.1     846 845.942 844.814 843.272  842.28   842.5  843.56   842.6
  842.59  842.57  842.56  842.55  842.54  842.45  842.43  842.33  842.32  842.21
   842.2  842.08  842.03     842     842     842     842     842     842     842
     842     842     842     842     842     842   841.7  841.65  841.51  841.65
     842
                                                                                
                                                                                
                          840.85  841.45  840.34  838.44
                                                                                
                                                                                
                                                                                
        
Pier Skew, UpSta & Num, DnSta & Num=  ,-45.761, 4 ,-45.761, 4 , 0 , 0 , 0 ,,
       4       4       3       3
     785   812.1   812.2     845
       4       4       3       3
     785   812.1   812.2     845
Pier Skew, UpSta & Num, DnSta & Num=  ,47.045, 4 ,47.045, 4 , 0 , 0 , 0 ,,
       4       4       3       3
     785   812.1   812.2     845
       4       4       3       3
     785   812.1   812.2     845
BR Coef=-1 , 1 , 1 ,0.9, 0 ,,,0.8,-1,1.2,0,
WSPro=,,,, 1 ,,,, 0 ,,,, 0 ,,,,-1 ,-1 ,-1 , 0 , 0 , 0 , 0 , 0
BR D #Sta/Elev= 30
-353.526  832.07-342.904  830.65-253.486  828.57-201.464  824.99-180.795  826.13
 -97.663     824 -81.025     820 -35.985     800 -32.584  800.09 -16.828  799.53
   -2.87  797.33   4.943  791.74  22.927  791.33  34.445  792.57   37.97     800
  43.115     800  53.555  803.94  83.853  809.68  96.339  809.32   113.7  806.75
 119.176  809.79 127.028     818 132.445  820.67 139.274  822.16 152.121  821.77
 164.126  823.32 187.925     826 225.775     834 270.455  832.36 311.313  835.74
BR D #Mann= 4
-353.526     .12 -32.584    .035   37.97     .12 164.126     .12
BC Design=,, 0 ,, 0 ,,,,,,
BC Use User HTab Curves=0
BC User HTab FreeFlow(D)= 0

Type RM Length L Ch R = 1 ,278.93  ,198.896,183.416,170.954
XS GIS Cut Line= 4
589175.584833602 4386862.7724731589234.1765383264386987.20707464
589254.3329625764387036.81022725589271.3438507864387061.38625155
#Sta/Elev= 30
-353.526  831.07-253.486  828.57-201.464  824.99-180.795  826.13 -95.828  823.36
 -46.651  823.16  -44.83  804.12 -35.985     800 -32.584  800.09 -16.828  799.53
   -2.87  797.33   4.943  791.74  22.927  791.33  34.445  792.57   37.97     800
  43.115     800  53.555  803.94  83.853  809.68  96.339  809.32   113.7  806.75
 119.176  809.79 127.028     818 132.445  820.67 139.274  822.16 152.121  821.77
 164.126  823.32 187.925     826 225.775     834 270.455  832.36 311.313  835.74
#Mann= 4 ,-1 , 0
-353.526     .12       0 -32.584    .038       0   37.97     .12       0
 164.126     .12       0
#XS Ineff= 2 , 0
                          88.331          810.42
Permanent Ineff=
       F       F
Bank Sta=-32.584,37.97
XS Rating Curve= 0 ,0
Skew Angle= 23.5
Exp/Cntr=0.5,0.3

Type RM Length L Ch R = 1 ,95.51   ,54.791,55.123,57.579
XS GIS Cut Line= 3
589163.7006814554386986.75597063 589194.009993834387015.32487498
589226.1694422274387053.58946746
#Sta/Elev= 30
-133.136  821.62-103.675   820.9 -98.786     820 -88.287     816 -74.442     812
 -63.025  807.53 -48.425  800.47  -23.35  799.43   -8.13  797.23     .39  791.64
      20  791.23    25.6  792.44   32.56  792.47   38.32     800  43.373     800
  49.672  804.38  58.169   805.1  62.238     806    72.9     806  83.268     810
  95.505     814  99.344  814.16 105.577  813.44 107.677  812.69 115.518   812.3
  118.34  813.69 127.723     820 129.331  820.72 135.236  821.68  167.52   822.6
#Mann= 4 ,-1 , 0
-133.136     .12       0 -48.425    .038       0   38.32     .12       0
  58.169     .12       0
Bank Sta=-48.425,38.32
XS Rating Curve= 0 ,0
Exp/Cntr=0.5,0.3

Type RM Length L Ch R = 3 ,78.91   ,,,
BEGIN DESCRIPTION:
High Street - Field Recon ID Deck 1
END DESCRIPTION:
Bridge Culvert--1,0,-1,-1, 0
Deck Dist Width WeirC Skew NumUp NumDn MinLoCord MaxHiCord MaxSubmerge Is_Ogee
12,10,2.6,0, 28, 30, , , 0.98, 0, 0,0,,
-135.696-130.217-127.493-124.508-123.589  -116.1    -116     -94     124   124.1
 133.465 133.629 133.661 133.694 133.727 148.655 148.819 150.131 150.295 151.608
  152.92 153.051 154.364 154.495 156.234 156.332 158.432 163.025
     822     822     822     822     822  822.27     826     826     826  822.27
  822.54  822.55  822.55  822.55  822.55     822     822     822     822     822
     822     822     822     822     822     822     822  822.14
                                                          817.97  817.97
                                                                                
                                                                
    -192-135.696-130.217-127.493-124.508-123.589  -116.1    -116     -96     122
   122.1 133.465 133.629 133.661 133.694 133.727 148.655 148.819 150.131 150.295
 151.608  152.92 153.051 154.364 154.495 156.234 156.332 158.432 163.025     190
     822     822     822     822     822     822  822.27     826     826     826
  822.27  822.54  822.55  822.55  822.55  822.55     822     822     822     822
     822     822     822     822     822     822     822     822  822.14  822.14
                                                                  817.97  817.97
                                                                                
                                                                                
Pier Skew, UpSta & Num, DnSta & Num=  ,-53, 2 ,-53, 2 , 0 , 0 , 0 ,,
    5.67    5.67
     790     820
    5.67    5.67
     790     820
Pier Skew, UpSta & Num, DnSta & Num=  ,79, 2 ,79, 2 , 0 , 0 , 0 ,,
    5.67    5.67
     790     820
    5.67    5.67
     790     820
BR Coef=-1 , 0 , 1 ,1.25, 0 ,,,0.8,-1,2,0,
WSPro=,,,, 1 ,,,, 0 ,,,, 0 ,,,,-1 ,-1 ,-1 , 0 , 0 , 0 , 0 , 0
BC Design=,, 0 ,, 0 ,,,,,,
BC Use User HTab Curves=0
BC User HTab FreeFlow(D)= 0

Type RM Length L Ch R = 1 ,40.39   ,19.909,20.071,22.298
XS GIS Cut Line= 5
589151.9933133114386989.07549866589153.934889335 4387000.2708028
589184.9787697184387029.62609116589211.6000020474387061.78249156
589218.5738261344387063.32173158
#Sta/Elev= 30
 -171.85  818.09-169.226  817.65-162.861     816-143.209     808  -137.5     806
-106.004  805.75 -89.764  805.09 -80.643  804.35 -61.286     802 -55.217     800
  -53.15     800  -25.35  799.33  -10.13  797.13   -1.61  791.54      18  791.13
    23.6  792.34   30.56  792.37  45.013     800  50.262     800  56.332  802.83
  58.038  804.14  62.172     806  63.976     806   75.23  806.95 104.364  807.99
 125.262  809.84 134.088     810 142.552  810.78 154.921  814.22 165.978   817.8
#Mann= 4 ,-1 , 0
 -171.85     .12       0  -53.15    .038       0  45.013     .12       0
  50.262     .12       0
Bank Sta=-53.15,45.013
XS Rating Curve= 0 ,0
Exp/Cntr=0.5,0.3

Type RM Length L Ch R = 1 ,20.32   ,29.866,20.32,54.206
XS GIS Cut Line= 5
589136.3326891174386944.41010611589148.9148332734387003.65103484
589179.565521652 4387032.6344672589207.6254099984387066.52822762
589248.6575865054387090.64705191
#Sta/Elev= 30
-340.814     822-274.147     822-246.489     822-239.928  820.36 -224.77     820
-184.285  806.31-159.843  805.74-155.413  804.79 -81.299     804 -59.055     802
 -54.167     800   -52.1     800  -28.35  799.23  -10.13  797.03   -4.61  791.44
      13  791.03    20.6  792.24  41.148     800  52.756  800.69  59.974     804
  62.402     806 121.227  808.77 149.409     808 168.602   811.2 198.556     820
 201.673  820.32 224.278     822 253.314  821.88  266.01  823.05 296.818  823.46
#Mann= 4 ,-1 , 0
-340.814     .12       0-274.147     .12       0   -52.1    .038       0
  52.756     .12       0
Bank Sta=-52.1,52.756
XS Rating Curve= 0 ,0
Exp/Cntr=0.3,0.1
Stream Node=Deckers_Creek   ,1               , 0 , 0 ,Upstream end
Stream Node=Deckers_Creek   ,1               , 0 , 1 ,Downstream end

Chan Stop Cuts=-1
Use User Specified Reach Order=0
Composite Channel Slope=5