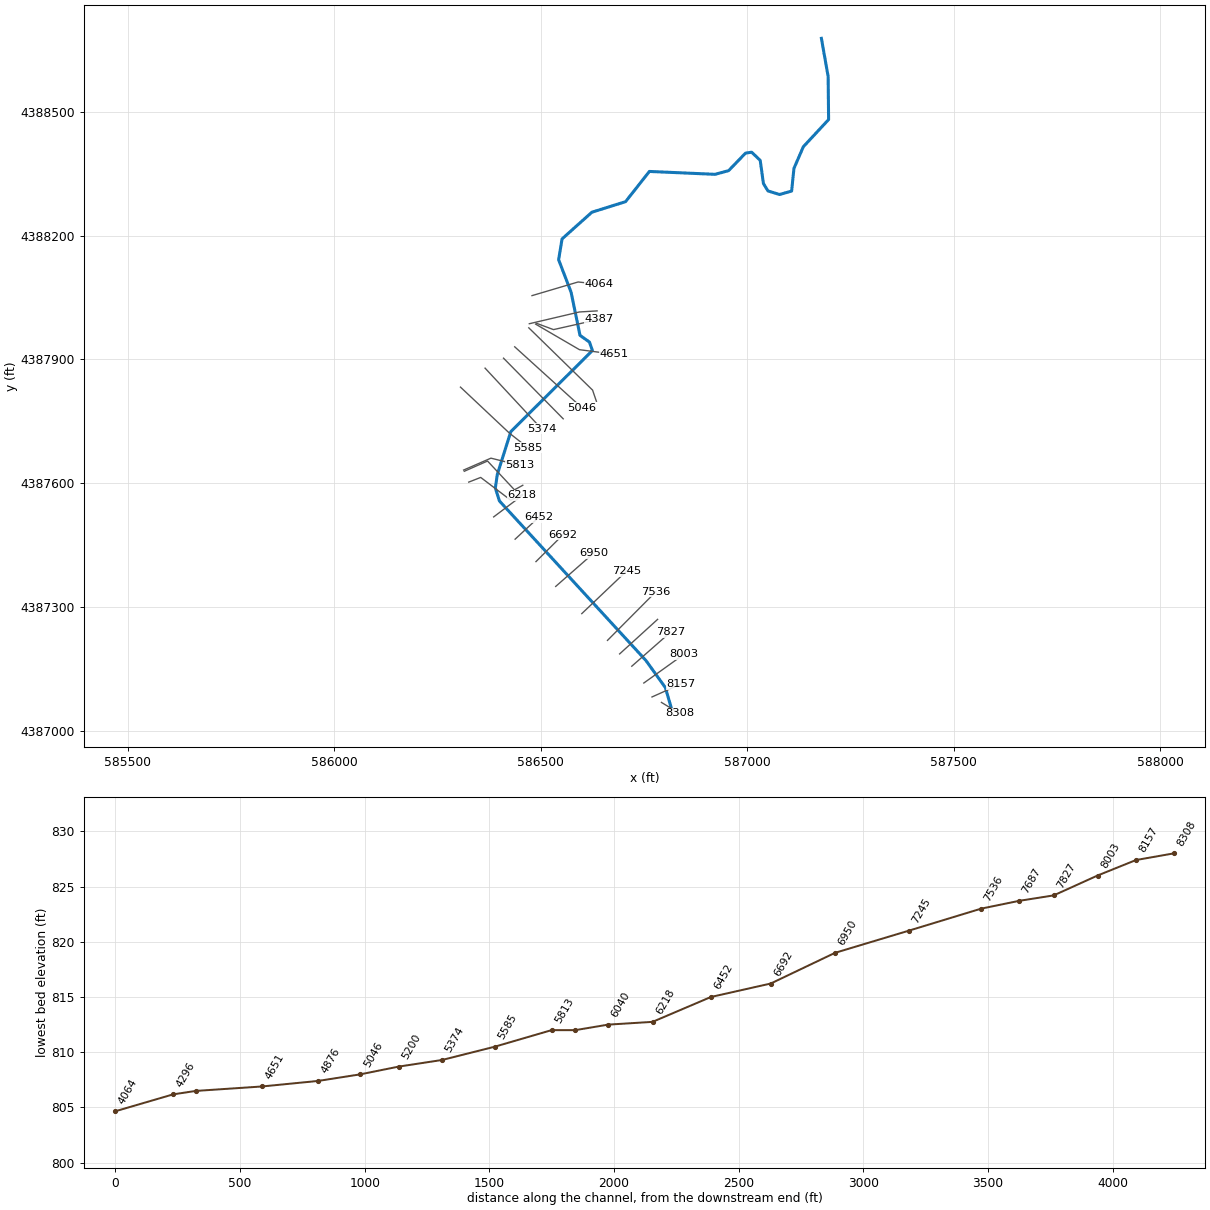
--- DentsRun.prj (project) ---

Proj Title=Dents Run
Current Plan=p01
Default Exp/Contr=0.3,0.1
English Units
Geom File=g01
Flow File=f01
Flow File=f02
Plan File=p01
Plan File=p02
Y Axis Title=Elevation
X Axis Title(PF)=Main Channel Distance
X Axis Title(XS)=Station
BEGIN DESCRIPTION:
Detailed Study for Dents Run
Upper Monongahela Watershed, Monongalia County, WV
Submitted by RAMPP for FEMA Region III
Model date: October 2015
HEC-RAS version 4.1.0
Vertical Datum: NAVD88 (feet)
Horizontal Datum: NAD_1983_UTM_Zone_17N
END DESCRIPTION:
DSS Export Rating Curves= 0
DSS Export Rating Curve Sorted= 0
DSS Export Volume Flow Curves= 0
DXF Filename=..\..\..\..\..\DETAILED\Basin_HUC_Stream\HEC-RAS\Dents Run\DentsRun.
DXF OffsetX= 0
DXF OffsetY= 0
DXF ScaleX= 1
DXF ScaleY= 10

--- DentsRun.p01 (plan) ---

Plan Title=Dents Run - Multiprofile
Program Version=4.10
Short Identifier=Multiprofile
Geom File=g01
Flow File=f01
Subcritical Flow
K Sum by GR= 0
Std Step Tol= 0.01
Critical Tol= 0.01
Num of Std Step Trials= 20
Max Error Tol= 0.3
Flow Tol Ratio= 0.001
Split Flow NTrial= 30
Split Flow Tol= 0.02
Split Flow Ratio= 0.02
Log Output Level= 0
Friction Slope Method= 1
Unsteady Friction Slope Method= 2
Unsteady Bridges Friction Slope Method= 1
Parabolic Critical Depth
Global Vel Dist= 0 , 0 , 0
Global Log Level= 0
CheckData=True
Encroach Param=-1 ,0,0, 0
Computation Interval=1HOUR
Output Interval=1HOUR
Run HTab= 0
Run UNet= 0
Run PostProcess= 0
Run WQNet= 0
UNET Theta= 1
UNET Theta Warmup= 1
UNET ZTol= 0.02
UNET ZSATol= 0.05
UNET MxIter= 20
UNET MaxInSteps= 0
UNET DtIC= 0
UNET DtMin= 0
UNET MaxCRTS= 20
UNET WFStab= 2
UNET SFStab= 1
UNET WFX= 1
UNET SFX= 1
UNET DSS MLevel= 4
UNET DZMax Abort= 98.43
UNET Convert EG Bridges= 0
UNET Use Existing IB Tables=-1
UNET Froude Reduction=False
UNET Froude Limit= 1
UNET Froude Power= 10
UNET Time Slicing=0,0, 5
UNET Junction Losses=0
Instantaneous Interval=1HOUR
DSS File=dss
Write IC File= 0
Write IC File at Sim End=0
Echo Input=False
Echo Parameters=False
Echo Output=False
Write Detailed= 0
WQ AD Non Conservative
WQ ULTIMATE=-1
WQ Max Comp Step=1HOUR
WQ Output Interval=15MIN
WQ Output Selected Increments= 0
WQ Output face flow=0
WQ Output face velocity=0
WQ Output face area=0
WQ Output face dispersion=0
WQ Output cell volume=0
WQ Output cell surface area=0
WQ Output cell continuity=0
WQ Output cumulative cell continuity=0
WQ Output face conc=0
WQ Output face dconc_dx=0
WQ Output face courant=0
WQ Output face peclet=0
WQ Output face adv mass=0
WQ Output face disp mass=0
WQ Output cell mass=0
WQ Output cell source sink temp=0
WQ Output cell source sink nsm=0
WQ Output MaxMinRange=-1
WQ Daily Max Min Mean=-1
WQ Daily Range=0
WQ Daily Time=0
WQ Create Restart=0
WQ Fixed Restart=0
WQ System Summary=0
WQ Use Fixed Temperature=0
Sorting and Armoring Iterations= 10
XS Update Threshold= 0.02
Hydraulics Update Threshold= 0.02
Energy Slope Method= 1
Volume Change Method= 0
XS Weighting Method= 0
Number of US Weighted Cross Sections= 1
Number of DS Weighted Cross Sections= 1
Upstream XS Weight=0.25
Main XS Weight=0.5
Downstream XS Weight=0.25
Number of DS XS's Weighted with US Boundary= 1
Upstream Boundary Weight= 1
Weight of XSs Associated with US Boundary= 0
Number of US XS's Weighted with DS Boundary= 1
Downstream Boundary Weight= 0.5
Weight of XSs Associated with DS Boundary= 0.5
Sediment Output Level= 4
Mass or Volume Output= 0
Output Increment Type= 1
Profile and TS Output Increment= 10
XS Output Flag= 0
XS Output Increment= 10
Disregard all LS=0
Disregard all Conn=0
Disregard all Breaches=0
Disregard all Pumps=0

--- DentsRun.p02 (plan) ---

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Plan Title=Dents Run - Floodway
Short Identifier=Floodway
Geom File=g01
Flow File=f02
Encroach Param=-1 ,0,0, 2
Encroach River=Dents Run
Encroach Reach=Reach 1
Encroach Node=8308
       1     -26      28
Encroach Node=8157
       1     -18      23
Encroach Node=8003
       1     -22    23.4
Encroach Node=7827
       1     -20    18.5
Encroach Node=7687
       1     -25      20
Encroach Node=7536
       1     -17      28
Encroach Node=7245
       1     -18      27
Encroach Node=6950
       1     -50      60
Encroach Node=6692
       1     -60      60
Encroach Node=6452
       1     -60      40
Encroach Node=6218
       1     -40      35
Encroach Node=6040
       1     -28      28
Encroach Node=5908
       1     -30      30
Encroach Node=5813
       1     -25      22
Encroach Node=5585
       1     -50      55
Encroach Node=5374
       1     -50      36
Encroach Node=5200
       1     -40      45
Encroach Node=5046
       1  -30.12      75
Encroach Node=4876
       1  -32.21      85
Encroach Node=4651
       1    -100   17.82
Encroach Node=4387
       1     -45      35
Encroach Node=4296
       1     -46   43.11
Encroach Node=4064
       1     -75   37.21
Encroach Node=4029
       1     -85      60
Encroach Node=3983
       1     -70      60
Encroach Node=3721
       1     -40     100
Encroach Node=3439
       1     -55      60
Encroach Node=3279
       1     -90      50
Encroach Node=3183
       1    -120      27
Encroach Node=3143
       1    -120    28.3
Encroach Node=3049
       1    -125      35
Encroach Node=2705
       1  -46.83     132
Encroach Node=2478
       1  -18.42     140
Encroach Node=2283
       1  -16.86     105
Encroach Node=2036
       1   -53.4      84
Encroach Node=1491
       1    -175      30
Encroach Node=1145
       1     -75      95
Encroach Node=913
       1     -22      95
Encroach Node=666
       1  -54.46   49.23
Encroach Node=488
       1     -37      93
Encroach Node=402
       1     -37      93
Encroach Node=324
       1   -43.5    47.5
Encroach Node=261
       1   -61.5      47
Encroach Node=177
       1   -62.5      43
Encroach Node=23
       1     -47      70

--- DentsRun.f01 (steady flow) ---

Flow Title=Dents Run - Multiprofile
Program Version=4.10
Number of Profiles= 6
Profile Names=10PCT,4PCT,2PCT,1PCT,1PCT_PLUS,0.2PCT
River Rch & RM=Dents Run,Reach 1         ,8308
    1663    2167    2571    2982    3951    4017
River Rch & RM=Dents Run,Reach 1         ,7536
    1671    2177    2582    2994    3967    4033
River Rch & RM=Dents Run,Reach 1         ,6692
    1673    2179    2585    2998    3972    4038
River Rch & RM=Dents Run,Reach 1         ,5813
    1827    2377    2817    3264    4325    4390
River Rch & RM=Dents Run,Reach 1         ,4651
    1831    2382    2823    3271    4334    4398
River Rch & RM=Dents Run,Reach 1         ,3721
    1834    2386    2827    3276    4340    4405
River Rch & RM=Dents Run,Reach 1         ,3049
    1856    2413    2860    3313    4390    4454
River Rch & RM=Dents Run,Reach 1         ,1491
    1864    2424    2873    3328    4409    4473
River Rch & RM=Dents Run,Reach 1         ,324
    1864    2425    2873    3328    4410    4474
River Rch & RM=Dents Run,Reach 1         ,23
    1865    2425    2874    3329    4411    4475
Boundary for River Rch & Prof#=Dents Run,Reach 1         , 1
Up Type= 0
Dn Type= 3
Dn Slope=0.001
Boundary for River Rch & Prof#=Dents Run,Reach 1         , 2
Up Type= 0
Dn Type= 3
Dn Slope=0.001
Boundary for River Rch & Prof#=Dents Run,Reach 1         , 3
Up Type= 0
Dn Type= 3
Dn Slope=0.001
Boundary for River Rch & Prof#=Dents Run,Reach 1         , 4
Up Type= 0
Dn Type= 3
Dn Slope=0.001
Boundary for River Rch & Prof#=Dents Run,Reach 1         , 5
Up Type= 0
Dn Type= 3
Dn Slope=0.001
Boundary for River Rch & Prof#=Dents Run,Reach 1         , 6
Up Type= 0
Dn Type= 3
Dn Slope=0.001
DSS Import GetInterval= 0
DSS Import GetPeak= 0
DSS Import FillOption= 0

--- DentsRun.f02 (steady flow) ---

Flow Title=Dents Run - Floodway
Program Version=4.10
Number of Profiles= 2
Profile Names=1PCT,FLOODWAY
River Rch & RM=Dents Run,Reach 1         ,8308
    2982    2982
River Rch & RM=Dents Run,Reach 1         ,7536
    2994    2994
River Rch & RM=Dents Run,Reach 1         ,6692
    2998    2998
River Rch & RM=Dents Run,Reach 1         ,5813
    3264    3264
River Rch & RM=Dents Run,Reach 1         ,4651
    3271    3271
River Rch & RM=Dents Run,Reach 1         ,3721
    3276    3276
River Rch & RM=Dents Run,Reach 1         ,3049
    3313    3313
River Rch & RM=Dents Run,Reach 1         ,1491
    3328    3328
River Rch & RM=Dents Run,Reach 1         ,324
    3328    3328
River Rch & RM=Dents Run,Reach 1         ,23
    3329    3329
Boundary for River Rch & Prof#=Dents Run,Reach 1         , 1
Up Type= 0
Dn Type= 3
Dn Slope=0.001
Boundary for River Rch & Prof#=Dents Run,Reach 1         , 2
Up Type= 0
Dn Type= 3
Dn Slope=0.001
DSS Import GetInterval= 0
DSS Import GetPeak= 0
DSS Import FillOption= 0

--- DentsRun.g01 (geometry) ---

Geom Title=Dents Run
Program Version=4.10

River Reach=Dents Run       ,Reach 1
Reach XY= 30
 586816.816852454387052.94024345586801.497604261 4387105.5487241
 586754.506587684387171.11425291586399.7010952954387557.51226568
586389.8164311734387589.02249007586394.6200792334387621.80677848
586427.3220716374387725.31076376586624.8080900774387921.68426218
586617.6635779894387942.16377444586594.8035777074387958.35475064
 586573.214593444388062.81275993586543.051585067 4388141.3962969
586551.3055691694388191.87727352586623.5370740624388256.48877832
 586705.135083074388282.04930664586762.7605717824388355.23178754
586921.5126057444388348.24577146586954.5315901524388357.13678757
586995.6491106614388399.68077209587010.4136228434388401.74426812
587031.0485830984388382.06028387587038.8301271944388326.02280318
 587049.781591334388308.08227496587077.8811036774388299.35280285
587107.0900880384388307.76528296587112.7441281084388362.57746763
587135.3480963874388414.92077228587196.625089144 4388480.8032931
587195.5156171314388584.94431038587179.1661449294388677.46330353

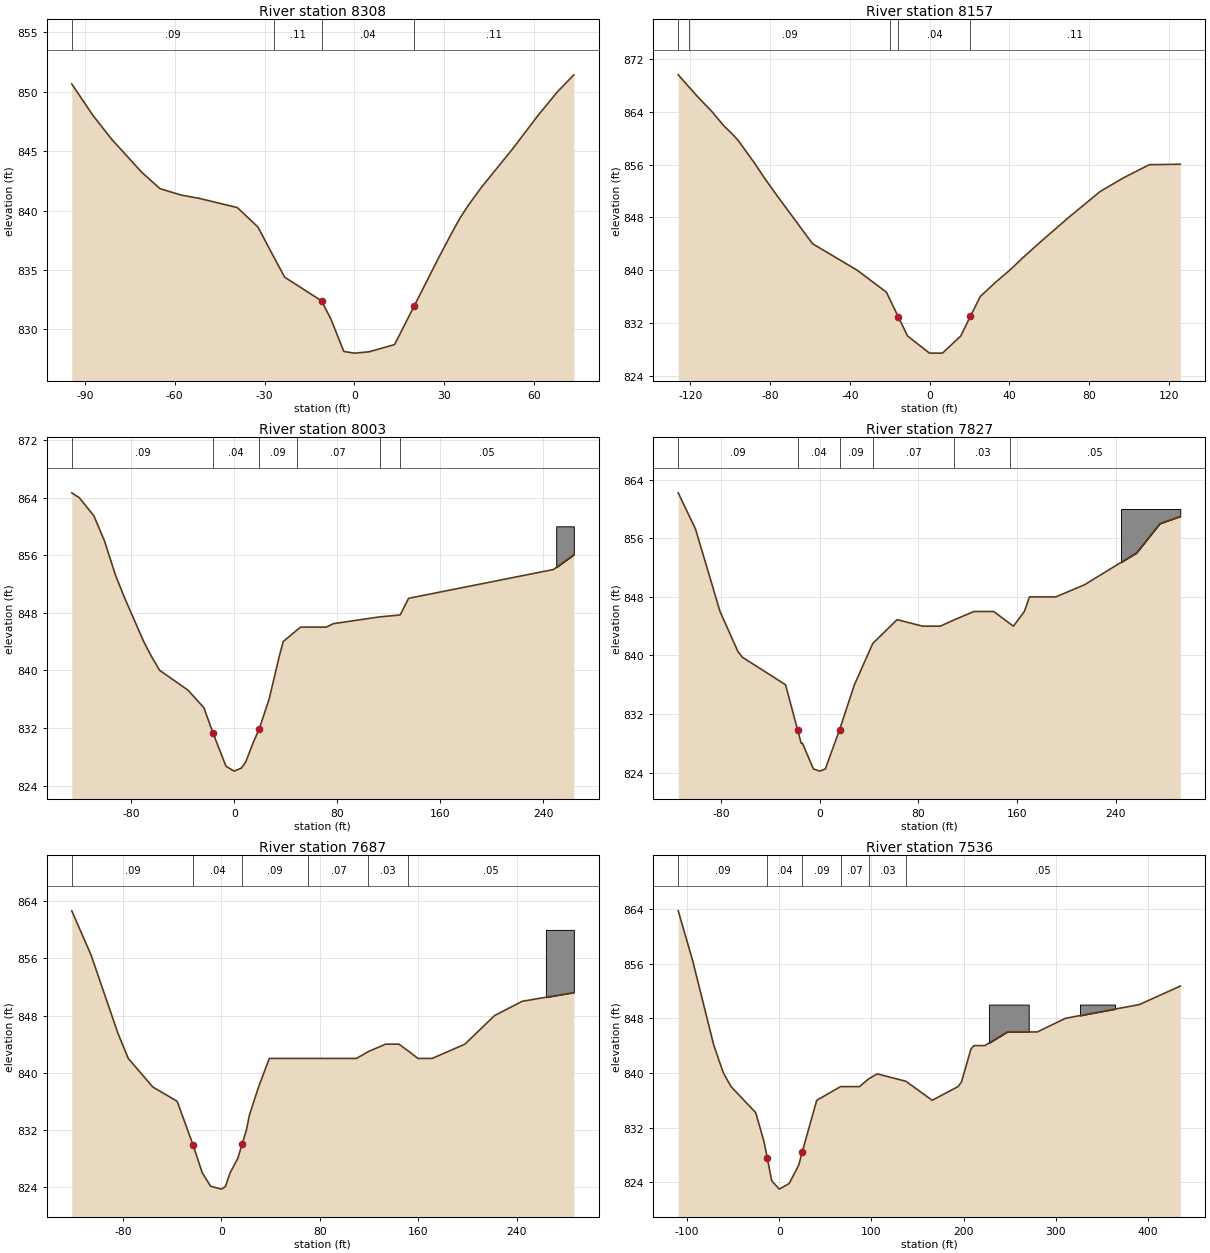
Type RM Length L Ch R = 1 ,8308    ,151,151,151
BEGIN DESCRIPTION:
(Channel invert from effective profile)
END DESCRIPTION:
XS GIS Cut Line= 2
586791.9299321434387069.79568366586835.6047246834387043.25674733
#Sta/Elev= 27
  -94.39  850.65 -87.303     848  -81.07     846  -71.03  843.22 -64.928  841.84
 -57.808   841.3 -51.772  841.02 -39.108  840.25 -32.218  838.61 -26.739     836
 -23.294  834.39     -11   832.4   -7.85  830.86   -3.55  828.14       0     828
    4.86  828.11   13.41  828.72      20 831.993  27.822  835.88  32.251     838
  35.269  839.38  38.025  840.44  42.421  841.96  52.756  845.17  61.286     848
  67.815     850  73.261  851.42
#Mann= 4 ,-1 , 0
  -94.39     .09       0 -26.739     .11       0     -11     .04       0
      20     .11       0
Bank Sta=-11,20
XS Rating Curve= 0 ,0
Exp/Cntr=0.3,0.1

Type RM Length L Ch R = 1 ,8157    ,147.43,154,160.57
XS GIS Cut Line= 2
586769.1095558614387082.99657182586839.2227007274387114.41535621
#Sta/Elev= 30
-126.148  869.64-120.768   867.8-116.109  866.23-109.055     864-103.543     862
 -98.491   860.5  -96.03  859.67 -87.664  856.17 -82.907     854 -75.951  851.06
 -58.694     844 -36.385     840 -21.654  836.66 -19.783  835.48   -15.6 832.877
 -11.024     830       0   827.4    6.49   827.4  15.682     830    20.5 832.974
  25.492     836   33.53  838.25  40.322     840   47.31     842  56.168   844.4
  69.882     848  85.761  851.95  97.474  854.02 110.335     856 125.919  856.07
#Mann= 5 ,-1 , 0
-126.148     .03       0-120.768     .09       0 -19.783     .11       0
   -15.6     .04       0    20.5     .11       0
Bank Sta=-15.6,20.5
XS Rating Curve= 0 ,0
Exp/Cntr=0.3,0.1

Type RM Length L Ch R = 1 ,8003    ,172.71,176,179.29
XS GIS Cut Line= 2
586749.2640276164387116.72878824586845.8368608094387185.85133309
#Sta/Elev= 30
 -126.05  864.65-120.341     864-108.891  861.46-100.722     858 -92.028  853.17
 -84.908     850 -70.243     844 -64.436     842 -57.841     840 -35.827  837.24
 -23.524  834.81   -16.5 831.324   -6.34  826.67       0     826     5.6  826.43
    8.96  827.28  14.829     830    19.5 831.897    27.1     836  35.039     842
  38.058     844  48.556  845.57  51.509     846  71.457     846  76.968  846.48
 112.828  847.42 128.839  847.69 135.335     850 247.769     854 263.583  856.06
#Mann= 6 ,-1 , 0
 -126.05     .09       0   -16.5     .04       0    19.5     .09       0
  48.556     .07       0 112.828     .03       0 128.839     .05       0
#Block Obstruct= 1 ,-1
 249.902 263.583     860
Bank Sta=-16.5,19.5
XS Rating Curve= 0 ,0
Exp/Cntr=0.3,0.1

Type RM Length L Ch R = 1 ,7827    ,139.45,140,140.55
XS GIS Cut Line= 2
586720.1617232564387157.41044474586813.4274764084387239.42907775
#Sta/Elev= 30
-114.928  862.21-100.853  857.24 -81.004     846 -66.503  840.54 -62.894  839.76
 -27.822     836     -18 829.809 -15.125     828 -14.075     828   -5.22   824.5
       0   824.2    4.48   824.5      16 829.846  28.084     836  43.012  841.65
  62.762  844.89  83.301     844  97.769     844 109.285  844.88 125.098     846
 141.142     846 154.593  844.31 157.119     844  166.01     846 170.177     848
 191.568     848 214.797  849.65 257.021     854 275.951     858 292.585  858.99
#Mann= 6 ,-1 , 0
-114.928     .09       0     -18     .04       0      16     .09       0
  43.012     .07       0 109.285     .03       0 154.593     .05       0
#Block Obstruct= 1 ,-1
 244.455 292.552     860
Bank Sta=-18,16
XS Rating Curve= 0 ,0
Exp/Cntr=0.3,0.1

Type RM Length L Ch R = 1 ,7687    ,149.37,151,152.63
XS GIS Cut Line= 2
586690.7241388924387187.17416511586782.6670600284387270.85091014
#Sta/Elev= 30
-121.522  862.67 -105.84  856.48 -84.022  845.53 -75.623     842 -55.676     838
 -35.892     836     -23 829.891 -15.551     826   -8.75  824.11       0   823.7
     3.3  824.06   7.152     826  13.353     828      17 830.075  20.374     832
  22.769  834.04  30.217     838  38.976     842  70.505     842 109.744     842
 119.521  842.97 133.465     844 144.324     844 151.706  843.06 159.744     842
 171.227     842 197.835     844 221.949     848 244.357     850 286.352  851.23
#Mann= 6 ,-1 , 0
-121.522     .09       0     -23     .04       0      17     .09       0
  70.505     .07       0 119.521     .03       0 151.706     .05       0
#Block Obstruct= 1 ,-1
 263.648 286.352     860
Bank Sta=-23,17
XS Rating Curve= 0 ,0
Exp/Cntr=0.3,0.1

Type RM Length L Ch R = 1 ,7536    ,291.92,291,290.08
XS GIS Cut Line= 2
586661.2896025284387219.91882951586778.3693799754387337.65697497
#Sta/Elev= 30
-109.613  863.72 -93.963  856.43 -71.129   844.1 -60.663     840 -52.264     838
 -25.558  834.19 -16.634     830     -13 827.593  -8.235  824.24       0     823
   10.75  823.82   21.26  826.55      25 828.489  40.682     836  66.535     838
  87.041     838  97.277  839.16 106.398  839.86 137.434  838.78 165.945     836
 193.996     838 197.769  838.69 207.907  843.47 211.155     844 223.064     844
 247.507     846  280.02     846 310.728     848  390.65     850 435.171  852.71
#Mann= 6 ,-1 , 0
-109.613     .09       0     -13     .04       0      25     .09       0
  66.535     .07       0  97.277     .03       0 137.434     .05       0
#Block Obstruct= 2 ,-1
 227.493 270.669     850 326.247 364.337     850
Bank Sta=-13,25
XS Rating Curve= 0 ,0
Exp/Cntr=0.3,0.1

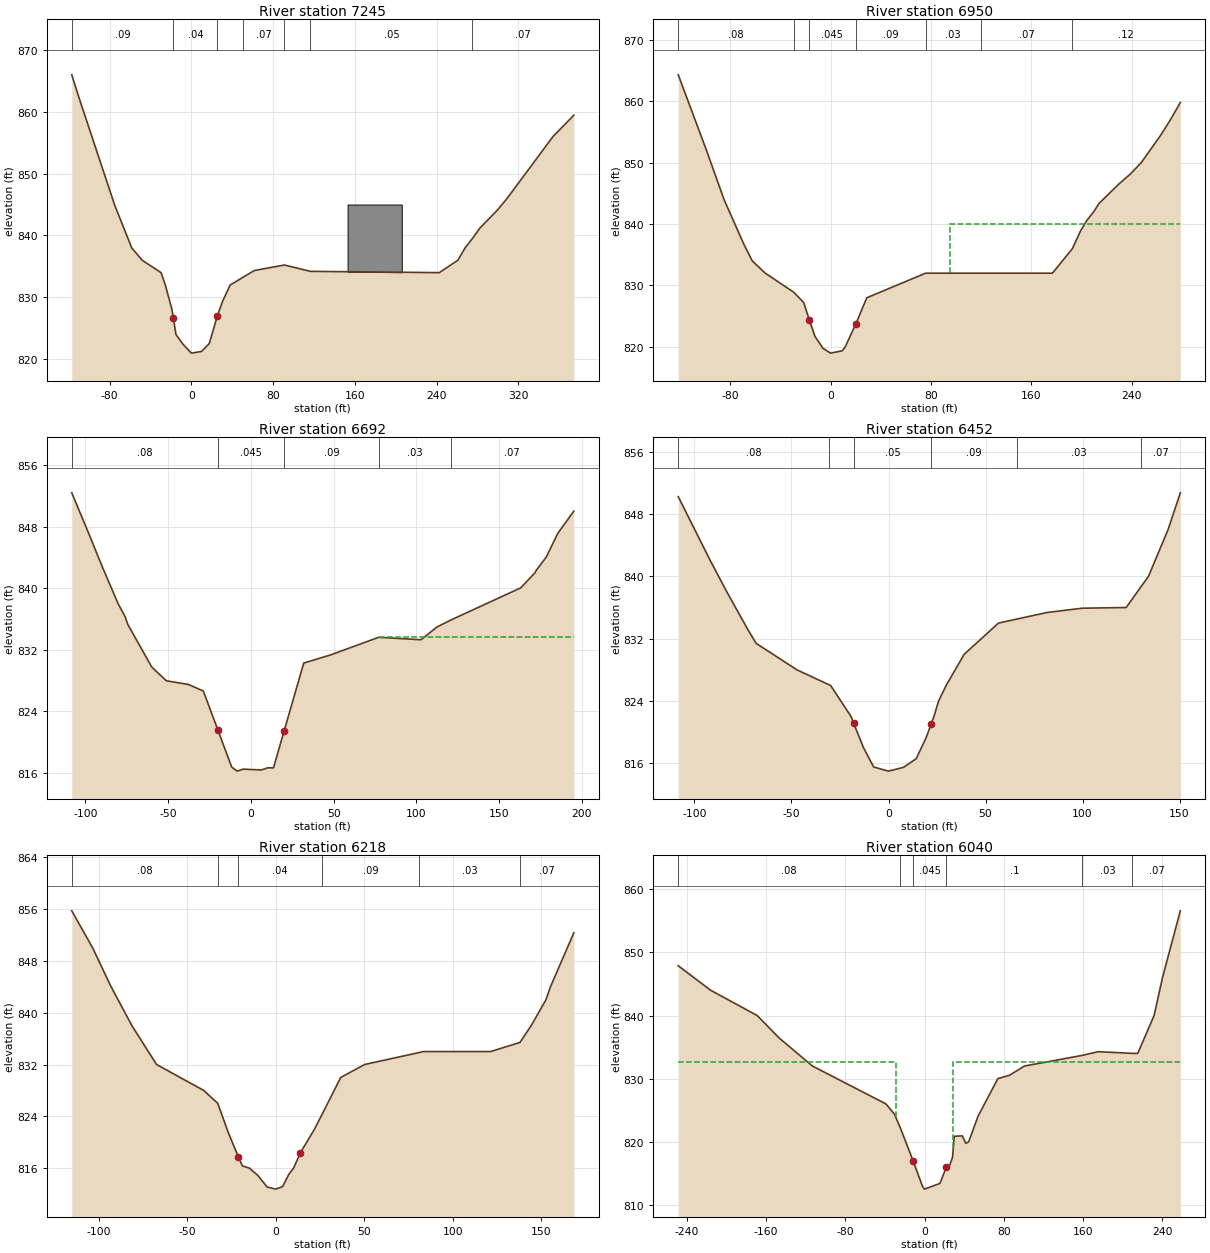
Type RM Length L Ch R = 1 ,7245    ,296.32,295,293.62
XS GIS Cut Line= 2
 586599.113449764387284.74064631  586707.59177114387387.92763959
#Sta/Elev= 30
-116.929  865.95 -109.35     862 -74.967  844.92 -58.268     838 -47.999     836
  -29.56     834 -25.361     832 -18.865     828   -17.5 826.644 -14.993     824
   -8.36  822.49       0     821      10  821.27   17.61  822.55    25.6 827.068
  30.774  829.44  38.058     832  50.459  833.24  61.811  834.35  91.142  835.23
 116.503  834.21 242.684     834 260.761     836 267.881     838 274.967  839.49
  282.71  841.26 299.147  844.04 309.022     846  353.97     856 374.278  859.43
#Mann= 7 ,-1 , 0
-116.929     .09       0   -17.5     .04       0    25.6     .09       0
  50.459     .07       0  91.142     .03       0 116.503     .05       0
 274.967     .07       0
#Block Obstruct= 1 ,-1
  152.92 205.938     845
Bank Sta=-17.5,25.6
XS Rating Curve= 0 ,0
Exp/Cntr=0.3,0.1

Type RM Length L Ch R = 1 ,6950    ,255.96,258,260.78
XS GIS Cut Line= 2
586535.9436489794387350.55611113586627.5573861114387430.92272812
#Sta/Elev= 30
-121.293  864.26 -98.819     852 -84.875     844 -68.898  836.65 -62.336     834
 -51.969     832 -29.331  828.91 -21.358  827.22     -17 824.459 -12.402  821.72
      -6  819.78       0     819    9.33  819.38  11.647     820      20 823.684
  28.871     828  75.722     832 119.521     832 176.706     832 192.618     836
  199.18  838.91 204.101  840.58 209.514  841.97 213.747  843.33 229.921  846.56
 238.714  848.12 247.507     850  262.73  854.38 270.538   856.9 278.543  859.76
#Mann= 7 ,-1 , 0
-121.293     .08       0 -29.331     .09       0     -17    .045       0
      20     .09       0  75.722     .03       0 119.521     .07       0
 192.618     .12       0
#XS Ineff= 2 , 0
       0                      95       0     840
Permanent Ineff=
       F       F
Bank Sta=-17,20
XS Rating Curve= 0 ,0
Exp/Cntr=0.3,0.1

Type RM Length L Ch R = 1 ,6692    ,241.16,240,238.59
BEGIN DESCRIPTION:
(Surveyed XS DEN_04X)
END DESCRIPTION:
XS GIS Cut Line= 2
586488.1632003894387410.63828787586553.7531131994387475.81367267
#Sta/Elev= 30
-108.268  852.38 -97.671  846.92 -90.059  842.89 -80.315     838 -76.083  836.31
 -74.475  835.31 -59.941  829.74 -51.148  827.96 -37.795  827.48 -28.773  826.63
     -20 821.569 -11.647  816.75  -8.366  816.22  -4.692  816.48   6.266  816.37
  10.203  816.65  13.583  816.64      20 821.414   31.89  830.26  48.524  831.35
  77.198  833.61 102.723  833.29 112.402  834.95 120.636  835.84 162.959  840.03
 171.621     842  172.31  842.29 178.412  844.03   185.4  847.12 195.079     850
#Mann= 5 ,-1 , 0
-108.268     .08       0     -20    .045       0      20     .09       0
  77.198     .03       0 120.636     .07       0
#XS Ineff= 2 , 0
       0                    77.2       0   833.7
Permanent Ineff=
       F       F
Bank Sta=-20,20
XS Rating Curve= 0 ,0
Exp/Cntr=0.3,0.1

Type RM Length L Ch R = 1 ,6452    ,237.37,234,230.71
XS GIS Cut Line= 2
586437.7157517654387464.98717654 586495.59422448 4387518.5649212
#Sta/Elev= 30
-108.366  850.23 -91.798     842 -83.301     838 -72.441  833.15 -68.209   831.4
 -47.178     828 -30.873  826.11 -29.823  825.99 -19.259     822     -18 821.172
 -12.861     818   -7.65  815.53       0     815    7.76  815.49   14.29   816.6
  19.357  819.27      22  821.03  23.392     822   25.82     824  29.724     826
  39.009     830  56.693     834   66.01  834.51  81.726  835.36  99.803  835.91
 122.507     836 130.348  838.74  133.99     840 144.094     846 150.394  850.72
#Mann= 6 ,-1 , 0
-108.366     .08       0 -30.873     .09       0     -18     .05       0
      22     .09       0   66.01     .03       0 130.348     .07       0
Bank Sta=-18,22
XS Rating Curve= 0 ,0
Exp/Cntr=0.3,0.1

Type RM Length L Ch R = 1 ,6218    ,223.08,178,127.54
BEGIN DESCRIPTION:
(Channel invert from effective profile)
END DESCRIPTION:
XS GIS Cut Line= 2
586385.7930711234387518.89715321586454.9156159784387570.82288185
#Sta/Elev= 30
-115.223  855.74-103.379     850 -93.241  844.14 -81.234     838 -67.323     832
 -40.682     828 -32.743     826 -26.706  821.42 -21.161  817.78 -18.832  816.34
 -14.895     816  -10.17  814.89   -4.86  813.08       0  812.75    3.94  813.15
    7.43  815.05  10.105     816      14 818.404  21.883     822  26.181  824.29
  36.745     830   50.23     832  80.873  833.84  83.465     834 121.424     834
 137.992  835.41 144.324     838  152.69     842 155.217     844 168.438  852.35
#Mann= 6 ,-1 , 0
-115.223     .08       0 -32.743     .09       0 -21.161     .04       0
  26.181     .09       0  80.873     .03       0 137.992     .07       0
Bank Sta=-21.161,14
XS Rating Curve= 0 ,0
Exp/Cntr=0.5,0.3

Type RM Length L Ch R = 1 ,6040    ,137.263,132,132.302
BEGIN DESCRIPTION:
US of County Route 49 (Channel invert from effective profile)
END DESCRIPTION:
XS GIS Cut Line= 4
586325.4518143784387603.10729825586354.3742867354387614.47938639
586427.1330956344387559.24657771 586455.906215994387573.46854588
#Sta/Elev= 30
-248.753  847.88-216.043     844-169.062     840-146.818  836.43-113.255     832
 -39.075     826 -30.545   824.4 -24.606  822.25 -11.385  816.89   -2.03  812.91
       0   812.5   15.55  813.41      22     816  24.672     816  28.248  817.56
  29.888  820.87  38.058  820.94  41.634  819.75  44.554     820  53.839     824
   73.95     830   85.63  830.53 100.886     832 159.383  833.69 175.361  834.27
 209.908     834 215.223     834 231.726     840 240.223     846 258.202  856.58
#Mann= 6 ,-1 , 0
-248.753     .08       0 -24.606      .1       0 -11.385    .045       0
      22      .1       0 159.383     .03       0 209.908     .07       0
#XS Ineff= 3 ,-1
                        -248.753     -29  832.63      29 258.202  832.63
Permanent Ineff=
       F       F       F
Bank Sta=-11.385,22
XS Rating Curve= 0 ,0
Exp/Cntr=0.5,0.3

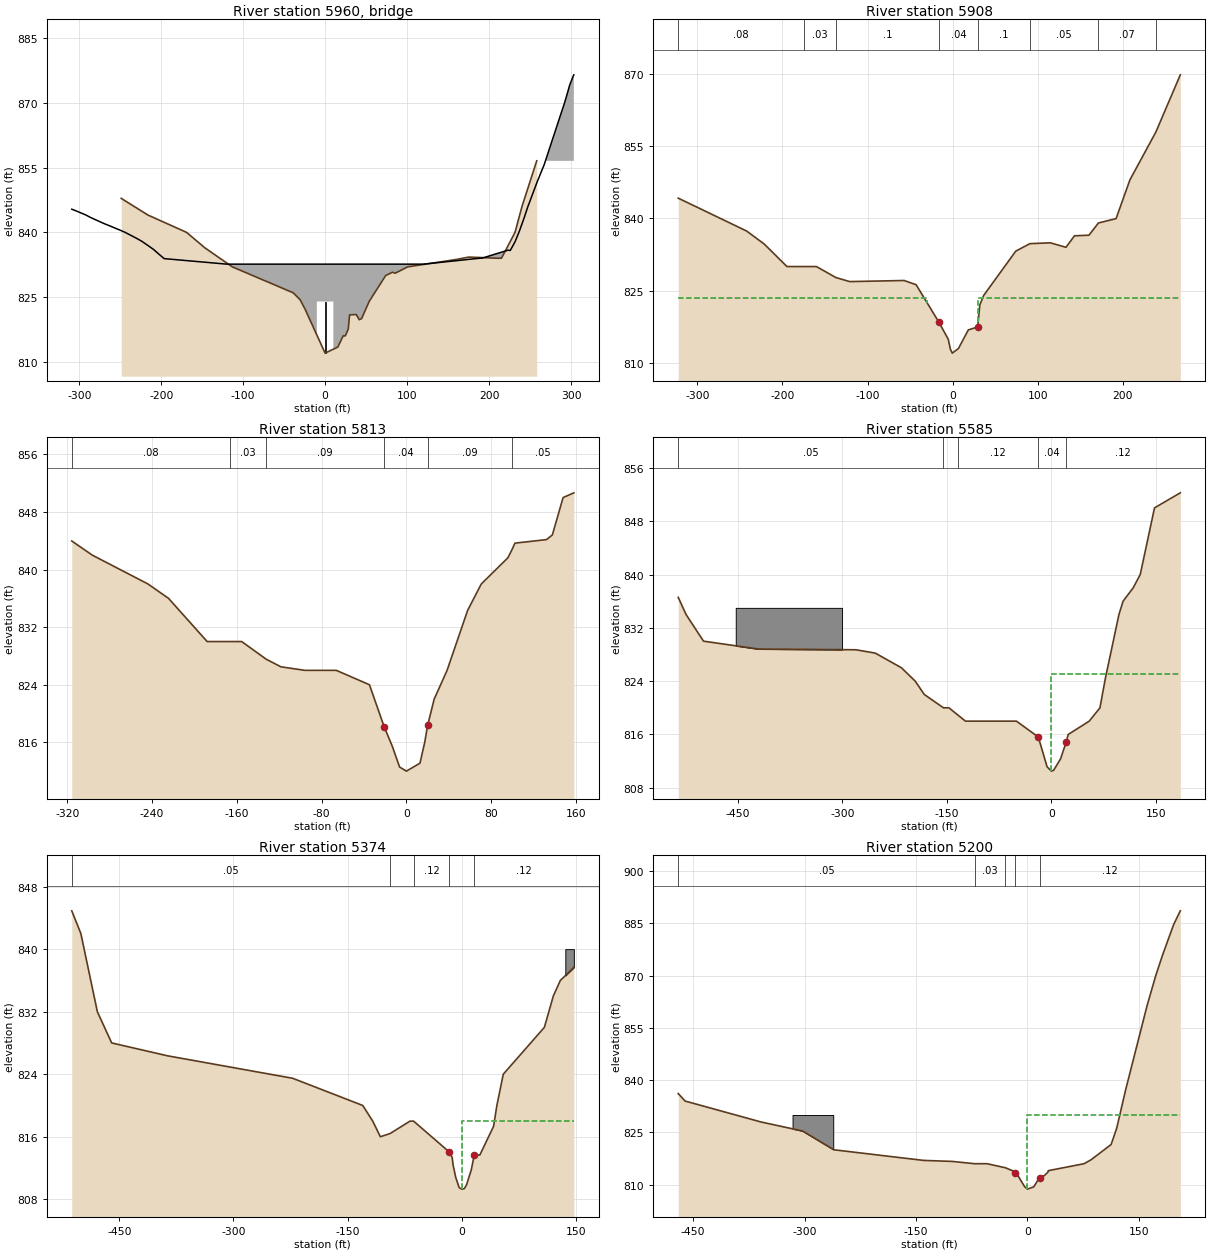
Type RM Length L Ch R = 3 ,5960    ,,,
BEGIN DESCRIPTION:
County Route 49 / Dents Run Boulevard (structure dimensions & channel invert from effective HEC-2 data)
END DESCRIPTION:
Bridge Culvert--1,0,-1,-1, 0
Deck Dist Width WeirC Skew NumUp NumDn MinLoCord MaxHiCord MaxSubmerge Is_Ogee
50,42,3,0, 73, 73, , , 0.98, 0, 0,0,,
-309.088-301.804-292.224-291.929-291.634-286.122-269.291-267.717-267.421-266.765
-260.597 -258.53-254.692 -251.28-245.341-244.915-244.029-234.941 -231.07-225.098
-224.213 -216.01-213.386-212.205-211.516-209.121-206.004-203.773-196.949-196.391
    -120  -10.09  -10.08   10.08   10.09     120 188.517 189.272 189.665 190.059
 190.486 190.912 194.685  223.13 225.787 226.476 229.035 230.479 232.152 237.172
 243.307 243.963 245.046 247.441 249.049 259.318  260.63 263.648 266.699 267.356
 270.079 272.703 292.093 294.554 294.587  295.21 297.113 298.163 300.262 301.312
 302.198  302.92 303.478
  845.37  844.82  844.05  844.02     844  843.44     842  841.88  841.86  841.81
  841.34  841.17  840.86   840.6  840.11  840.08     840   839.1  838.72  838.09
     838  836.93  836.58  836.42  836.33     836  835.48  835.11     834  833.91
  832.63  832.63  832.63  832.63  832.63  832.63     834     834     834     834
     834     834   834.2  835.87  835.79     836  836.88  837.37     838  840.35
  843.61     844  844.63     846  846.79     852  852.57     854   855.4  855.72
  857.31  858.83     870  871.57  871.61     872  873.28     874  875.05  875.57
     876   876.3  876.52
                                                                                
                                                                                
                                                                                
                  823.96  823.96
                                                                                
                                                                                
                                                                                
                        
-309.088-301.804-292.224-291.929-291.634-286.122-269.291-267.717-267.421-266.765
-260.597 -258.53-254.692 -251.28-245.341-244.915-244.029-234.941 -231.07-225.098
-224.213 -216.01-213.386-212.205-211.516-209.121-206.004-203.773-196.949-196.391
    -120  -10.09  -10.08   10.08   10.09     120 188.517 189.272 189.665 190.059
 190.486 190.912 194.685  223.13 225.787 226.476 229.035 230.479 232.152 237.172
 243.307 243.963 245.046 247.441 249.049 259.318  260.63 263.648 266.699 267.356
 270.079 272.703 292.093 294.554 294.587  295.21 297.113 298.163 300.262 301.312
 302.198  302.92 303.478
  845.37  844.82  844.05  844.02     844  843.44     842  841.88  841.86  841.81
  841.34  841.17  840.86   840.6  840.11  840.08     840   839.1  838.72  838.09
     838  836.93  836.58  836.42  836.33     836  835.48  835.11     834  833.91
  832.63  832.63  832.63  832.63  832.63  832.63     834     834     834     834
     834     834   834.2  835.87  835.79     836  836.88  837.37     838  840.35
  843.61     844  844.63     846  846.79     852  852.57     854   855.4  855.72
  857.31  858.83     870  871.57  871.61     872  873.28     874  875.05  875.57
     876   876.3  876.52
                                                                                
                                                                                
                                                                                
                  823.96  823.96
                                                                                
                                                                                
                                                                                
                        
Pier Skew, UpSta & Num, DnSta & Num=  ,0, 2 ,0, 2 , 0 , 0 , 0 ,,
       1       1
     810  823.96
       1       1
     810  823.96
BR Coef=-1 , 1 , 1 ,1.25, 0 ,,,0.8,0,1.466,0,
WSPro=,,,, 1 ,,,, 0 ,,,, 0 ,,,,-1 ,-1 ,-1 , 0 , 0 , 0 , 0 , 0
BR U #Sta/Elev= 30
-248.753  847.88-216.043     844-169.062     840-146.818  836.43-113.255     832
 -39.075     826 -30.545   824.4 -24.606  822.25     -16 818.681       0     812
   15.55  813.41      22     816  24.672     816  28.248  817.56  29.888  820.87
  38.058  820.94  41.634  819.75  44.554     820  53.839     824   73.95     830
  82.251  830.75   85.63  830.53 100.886     832 159.383  833.69 175.361  834.27
 209.908     834 215.223     834 231.726     840 240.223     846 258.202  856.58
BR U #Mann= 6
-248.753     .08 -24.606     .09     -16    .045      22     .09 159.383    .035
 209.908     .07
BR D #Sta/Elev= 30
-322.572  844.22-242.224  837.39-194.751     830-174.967     830-160.138     830
-137.336  827.72-120.965  826.87 -56.988   827.1 -42.913  826.22     -16 818.396
  -7.874     816    -2.6   812.8       0     812    6.89  812.97  18.471  816.83
  24.147  817.18  29.462  817.43  31.923     822  36.549     824  74.213   833.2
  90.846  834.76 114.993  834.93 133.268     834 143.241  836.39 160.302  836.52
 171.424  839.06 192.159  839.96 208.399     848 239.042     858 267.684  869.86
BR D #Mann= 8
-322.572     .08-174.967    .035-137.336     .09     -16    .045  24.147     .09
  90.846     .05 171.424     .07 239.042     .12
BC Design=,, 0 ,, 0 ,,,,,,
BC Use User HTab Curves=0
BC User HTab FreeFlow(D)= 0

Type RM Length L Ch R = 1 ,5908    ,74.4,95,116.29
BEGIN DESCRIPTION:
DS of County Route 49  (Channel invert from effective profile)
END DESCRIPTION:
XS GIS Cut Line= 4
586314.6862782454387629.35972257586370.9096869394387654.16434688
586436.0911677454387584.44134602586456.2963599954387595.46291415
#Sta/Elev= 30
-322.572  844.22-242.224  837.39-221.358  834.66-194.751     830-174.967     830
-160.138     830-137.336  827.72-120.965  826.87 -56.988   827.1 -42.913  826.22
     -16 818.396    -5.1  814.88    -2.6   812.8   -.394     812    6.89  812.97
  18.471  816.83  29.462  817.43  31.923     822  36.549     824  74.213   833.2
  90.846  834.76 114.993  834.93 133.268     834 143.241  836.39 160.302  836.52
 171.424  839.06 192.159  839.96 208.399     848 239.042     858 267.684  869.86
#Mann= 8 ,-1 , 0
-322.572     .08       0-174.967     .03       0-137.336      .1       0
     -16     .04       0  29.462      .1       0  90.846     .05       0
 171.424     .07       0 239.042     .12       0
#XS Ineff= 2 ,-1
-322.572     -30   823.5      30 267.684   823.5
Permanent Ineff=
       F       F
Bank Sta=-16,29.462
XS Rating Curve= 0 ,0
Exp/Cntr=0.5,0.3

Type RM Length L Ch R = 1 ,5813    ,244.62,228,214.13
XS GIS Cut Line= 3
586313.0312142244387632.33761861586379.1789110424387661.11073896
586449.2920559084387643.58169075
#Sta/Elev= 30
-315.781  843.97-296.358     842-243.898     838-224.475     836-188.025     830
-166.601     830-155.446     830-132.218  827.54-118.406  826.49 -95.669     826
 -66.175     826 -34.875     824     -21  818.17 -13.419  815.49   -6.43  812.57
       0     812   12.79   813.1   17.29     816      20 818.339  26.214     822
  38.386     826  57.776  834.33  70.669     838  95.801  841.64  99.442  842.71
 102.428  843.67 132.152  844.16 137.697   844.8 147.867     850 158.005  850.66
#Mann= 6 ,-1 , 0
-315.781     .08       0-166.601     .03       0-132.218     .09       0
     -21     .04       0      20     .09       0  99.442     .05       0
Bank Sta=-21,20
XS Rating Curve= 0 ,0
Exp/Cntr=0.3,0.1

Type RM Length L Ch R = 1 ,5585    ,213.32,211,205.94
XS GIS Cut Line= 3
 586305.426454134387833.09109309586424.0698555964387721.52514771
586468.8053521494387686.24759527
#Sta/Elev= 30
-535.958  836.58-524.705     834-499.639     830-420.932  828.82-280.807  828.71
 -252.92  828.21-215.223     826-195.505     824 -182.48     822-154.921     820
-147.047     820-133.694  818.87 -123.36     818 -50.131     818 -18.734  815.62
    -6.1  811.15       0   810.5    3.27  810.62   13.21  812.33  21.293  814.85
  24.245     816  54.429     818  69.849     820  77.657  824.44  97.113     834
 103.084     836 117.552     838 127.723     840 148.196     850 185.269  852.26
#Mann= 5 ,-1 , 0
-535.958     .05       0-154.921     .03       0-133.694     .12       0
 -18.734     .04       0  21.293     .12       0
#XS Ineff= 2 , 0
       0     -95     825               0
Permanent Ineff=
       F       F
#Block Obstruct= 2 ,-1
-453.346-300.623     835 160.203 185.269     835
Bank Sta=-18.734,21.293
XS Rating Curve= 0 ,0
Exp/Cntr=0.3,0.1

Type RM Length L Ch R = 1 ,5374    ,173.08,174,174.92
XS GIS Cut Line= 2
586364.9569428664387879.06102966586501.8792005584387731.88834784
#Sta/Elev= 30
-512.336   844.9-500.394     842 -478.74     832-459.908     828-386.319  826.35
-222.178  823.48-130.085     820-116.995     818-106.988     816 -94.193  816.41
 -68.045     818 -63.353     818 -16.437  814.05  -12.68  813.37  -11.41  812.38
   -7.96   810.8   -3.41  809.48       0   809.3    3.31  809.36     6.4  809.89
    12.4  811.75  16.437  813.68  23.688  813.66  41.765  817.34  46.096  820.01
  54.495     824 108.497     830  120.21     834 129.462     836 147.178  837.66
#Mann= 5 ,-1 , 0
-512.336     .05       0 -94.193     .03       0 -63.353     .12       0
 -16.437     .04       0  16.437     .12       0
#XS Ineff= 2 , 0
       0   -62.4     818               0
Permanent Ineff=
       F       F
#Block Obstruct= 1 ,-1
 135.958 147.178     840
Bank Sta=-16.437,16.437
XS Rating Curve= 0 ,0
Exp/Cntr=0.3,0.1

Type RM Length L Ch R = 1 ,5200    ,152.13,154,155.87
XS GIS Cut Line= 2
586409.6040474184387903.20423796586554.1341132044387756.36074014
#Sta/Elev= 30
-470.046  836.15-460.794     834-358.825     828-302.657   825.4-260.499     820
-139.731  816.95-101.181  816.66 -70.801     816 -54.232     816  -29.56  814.84
 -20.112     814 -16.404  813.33 -13.156  812.75   -3.68   809.4       0   808.7
    8.58  809.34  16.404     812   22.39   812.5  27.756  813.59   28.15     814
  76.312     816  85.728  817.12 112.795  821.52 120.276  826.17 132.415  837.29
 161.188   861.4 172.736  869.93 181.627  875.69 196.982  884.71 205.938  888.64
#Mann= 5 ,-1 , 0
-470.046     .05       0 -70.801     .03       0  -29.56     .12       0
 -16.404     .04       0  16.404     .12       0
#XS Ineff= 2 , 0
       0    -102     830               0
Permanent Ineff=
       F       F
#Block Obstruct= 1 ,-1
-316.142-261.352     830
Bank Sta=-16.404,16.404
XS Rating Curve= 0 ,0
Exp/Cntr=0.3,0.1

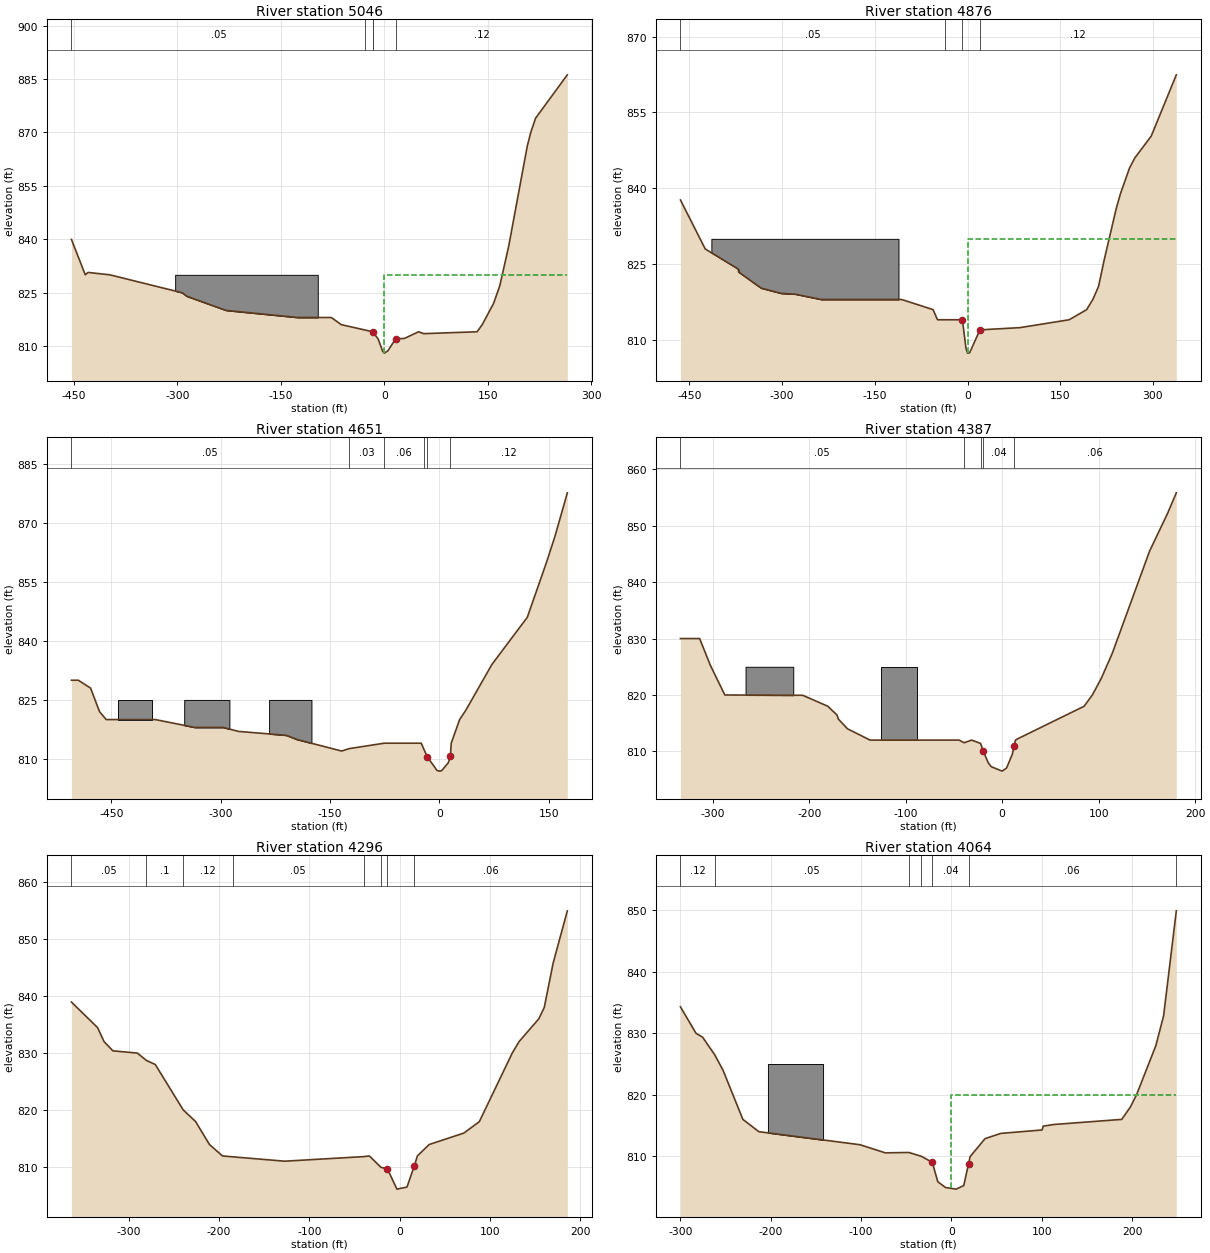
Type RM Length L Ch R = 1 ,5046    ,171.22,170,168.78
XS GIS Cut Line= 2
586436.725151753 4387930.6545263 586599.113449764387783.48184448
#Sta/Elev= 30
-453.576  839.93 -433.53     830 -429.56  830.67-397.966     830-292.979  824.96
 -286.68     824-229.462     820-125.262     818 -76.772     818 -62.303     816
 -27.395  814.47 -16.732     814  -16.47  813.93  -8.891     812    -2.3   808.5
       0     808    5.14  808.62   16.47     812  29.331  812.14   49.77     814
  57.185  813.47  134.58     814  142.06     816 158.596     822  167.52  826.94
 180.413     838 207.382  866.17 212.434     870 219.423     874 265.453  886.18
#Mann= 5 ,-1 , 0
-453.576     .05       0 -27.395     .03       0 -16.732     .12       0
  -16.47     .04       0   16.47     .12       0
#XS Ineff= 2 , 0
       0  -96.42     830               0
Permanent Ineff=
       F       F
#Block Obstruct= 1 ,-1
-303.215 -96.424     830
Bank Sta=-16.47,16.47
XS Rating Curve= 0 ,0
Exp/Cntr=0.3,0.1

Type RM Length L Ch R = 1 ,4876    ,203.61,225,246.39
XS GIS Cut Line= 3
586470.7896001744387976.62751086586625.240906083  4387825.815517
586634.5007301974387798.69441266
#Sta/Elev= 30
-464.501  837.68-424.377     828-370.735     824-370.472  823.44 -333.76  820.24
-301.411  819.21-278.379  819.05-236.713     818-106.463     818 -55.807     816
 -48.589     814  -37.27     814  -9.055     814  -7.677  813.38   -2.58  808.41
       0   807.4    3.41  807.48      20     812  84.744  812.44 164.469     814
 192.684     816 202.657     818 211.909  820.58 221.391     826 240.584     836
 247.441  838.95 262.041     844 270.669     846 297.146  850.31 337.762  862.43
#Mann= 4 ,-1 , 0
-464.501     .05       0  -37.27     .03       0  -9.055     .04       0
      20     .12       0
#XS Ineff= 2 , 0
       0 -111.71     830               0
Permanent Ineff=
       F       F
#Block Obstruct= 1 ,-1
-414.469-111.713     830
Bank Sta=-9.055,20
XS Rating Curve= 0 ,0
Exp/Cntr=0.3,0.1

Type RM Length L Ch R = 1 ,4651    ,252.84,264,275.16
XS GIS Cut Line= 3
586487.3280483784387985.55815097 586593.489889694387923.71118221
586677.1666347244387912.79629407
#Sta/Elev= 30
-504.593     830 -495.21     830-478.379     828-466.043     822-456.923     820
  -389.6     820-335.531     818-296.719     818-275.394  816.99-210.007     816
-195.636  814.95-134.022     812-123.917  812.61 -75.689     814     -25     814
 -21.227  812.41 -16.699  810.55   -3.43  807.09       0   806.9    2.83  806.98
   12.15  809.03      15  810.66  16.175     814  27.657     820  36.024  822.32
  71.916     834 120.505     846 146.883     860 158.629   866.7 175.361  877.62
#Mann= 6 ,-1 , 0
-504.593     .05       0-123.917     .03       0 -75.689     .06       0
 -21.227     .12       0 -16.699     .04       0      15     .12       0
#Block Obstruct= 3 ,-1
 -440.65-393.898     825-349.967-288.025     825-233.563-175.492     825
Bank Sta=-16.699,15
XS Rating Curve= 0 ,0
Exp/Cntr=0.3,0.1

Type RM Length L Ch R = 1 ,4387    ,90.69,91,91.31
XS GIS Cut Line= 3
586489.641480407  4387987.542399586530.6523209144387972.32678281
586640.7857062754387997.13140712
#Sta/Elev= 30
-333.399     830-313.517     830-302.264  825.21-287.402     820-206.627  819.94
-180.676     818-171.161  816.45-169.718  815.72-160.302     814-136.877     812
 -44.652     812 -39.403  811.53 -31.594     812 -22.375  811.41  -19.39  809.98
 -14.501     808  -11.36  807.29       0   806.5     4.6  807.06  10.499  809.48
  12.402  810.94  13.812     812  16.437  812.26  84.941     818  93.471     820
  102.69  822.93 114.108  827.38 152.756  845.49 171.555  852.24 180.479  855.83
#Mann= 5 ,-1 , 0
-333.399     .05       0 -39.403     .03       0 -22.375     .06       0
  -19.39     .04       0  12.402     .06       0
#Block Obstruct= 2 ,-1
-265.945-216.503     825-125.919 -88.386     825
Bank Sta=-19.39,12.402
XS Rating Curve= 0 ,0
Exp/Cntr=0.3,0.1

Type RM Length L Ch R = 1 ,4296    ,230.13,232,233.87
XS GIS Cut Line= 3
 586472.112432194387986.54875099586593.1607056864388014.99268734
586636.1557942184388017.63835137
#Sta/Elev= 30
-363.517  838.93 -334.58  834.46-327.362     832-317.585  830.39-290.518     830
-280.446  828.71-270.636     828-239.797  820.07 -226.05  818.03-210.663     814
-196.227     812-184.777  811.84-127.329  811.08 -39.797  811.88  -33.53     812
 -20.604     810 -13.484  809.72   -2.99  806.19    8.12  806.55  16.404  810.31
  19.652     812  32.743     814  71.129     816  88.287     818 124.738     830
 132.251     832 154.167     836 160.236     838 170.046  845.76 185.761   854.9
#Mann= 8 ,-1 , 0
-363.517     .05       0-280.446      .1       0-239.797     .12       0
-184.777     .05       0 -39.797     .03       0 -20.604     .06       0
 -13.484     .04       0  16.404     .06       0
#XS Ineff= 2 , 0
       0    -146                       0
Permanent Ineff=
       F       F
Bank Sta=-13.484,16.404
XS Rating Curve= 0 ,0
Exp/Cntr=0.3,0.1

Type RM Length L Ch R = 1 ,4064    ,34.35,35,35.65
BEGIN DESCRIPTION:
(Surveyed XS DEN_03)
END DESCRIPTION:
XS GIS Cut Line= 3
 586478.574192274388054.56791983 586590.228529654388087.64176824
586640.7643702754388082.08526417
#Sta/Elev= 30
-299.934   834.3 -282.71     830-275.361  829.36-261.909  826.48-252.822     824
 -230.84     816-213.123     814-101.181  811.88 -73.228  810.56 -47.146  810.62
 -33.465  810.01 -21.129  809.01 -15.092  805.86  -6.496  804.92   5.282  804.66
  13.648  805.24      19 808.814  20.702  809.95  37.205  812.87  54.626  813.72
 100.394  814.28 101.575   814.9 113.419  815.17 188.517     816 198.031     818
 204.888     820  226.28     828 234.843  832.84 248.294  849.16 248.917  849.91
#Mann= 7 ,-1 , 0
-299.934     .12       0-261.909     .05       0 -47.146     .03       0
 -33.465     .06       0 -21.129     .04       0      19     .06       0
 248.294     .12       0
#XS Ineff= 2 , 0
       0 -142.06     820               0
Permanent Ineff=
       F       F
#Block Obstruct= 1 ,-1
-203.117 -142.06     825
Bank Sta=-21.129,19
XS Rating Curve= 0 ,0
Exp/Cntr=0.5,0.3