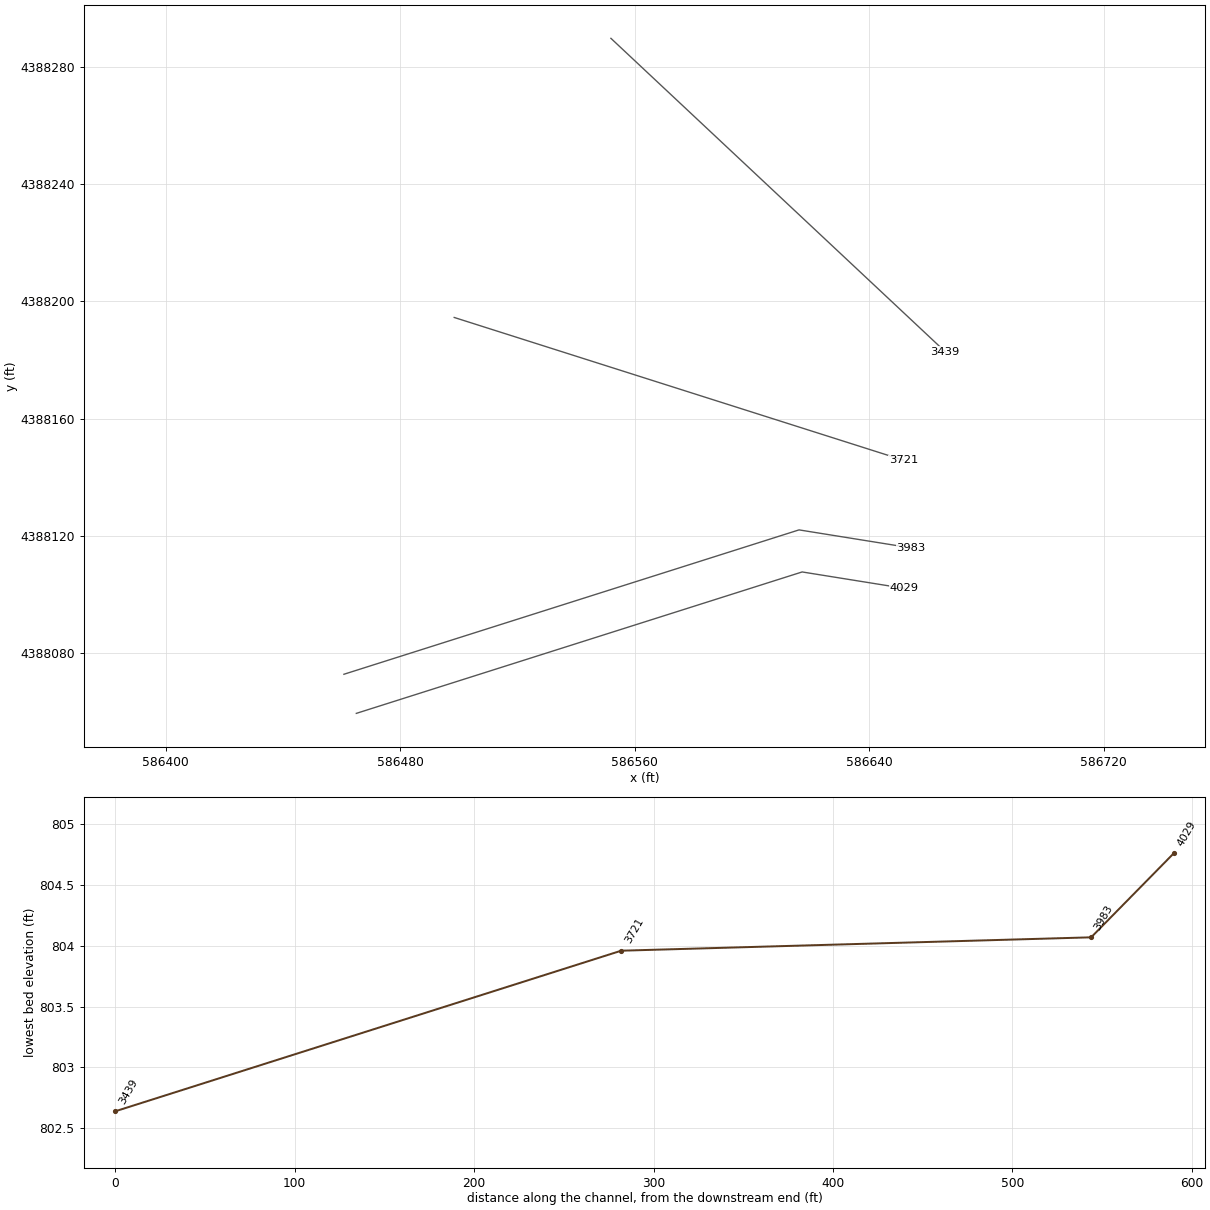
HEC-RAS study DentsRun.prj: Dents Run

--- DentsRun.g01 (geometry) --- (continued)

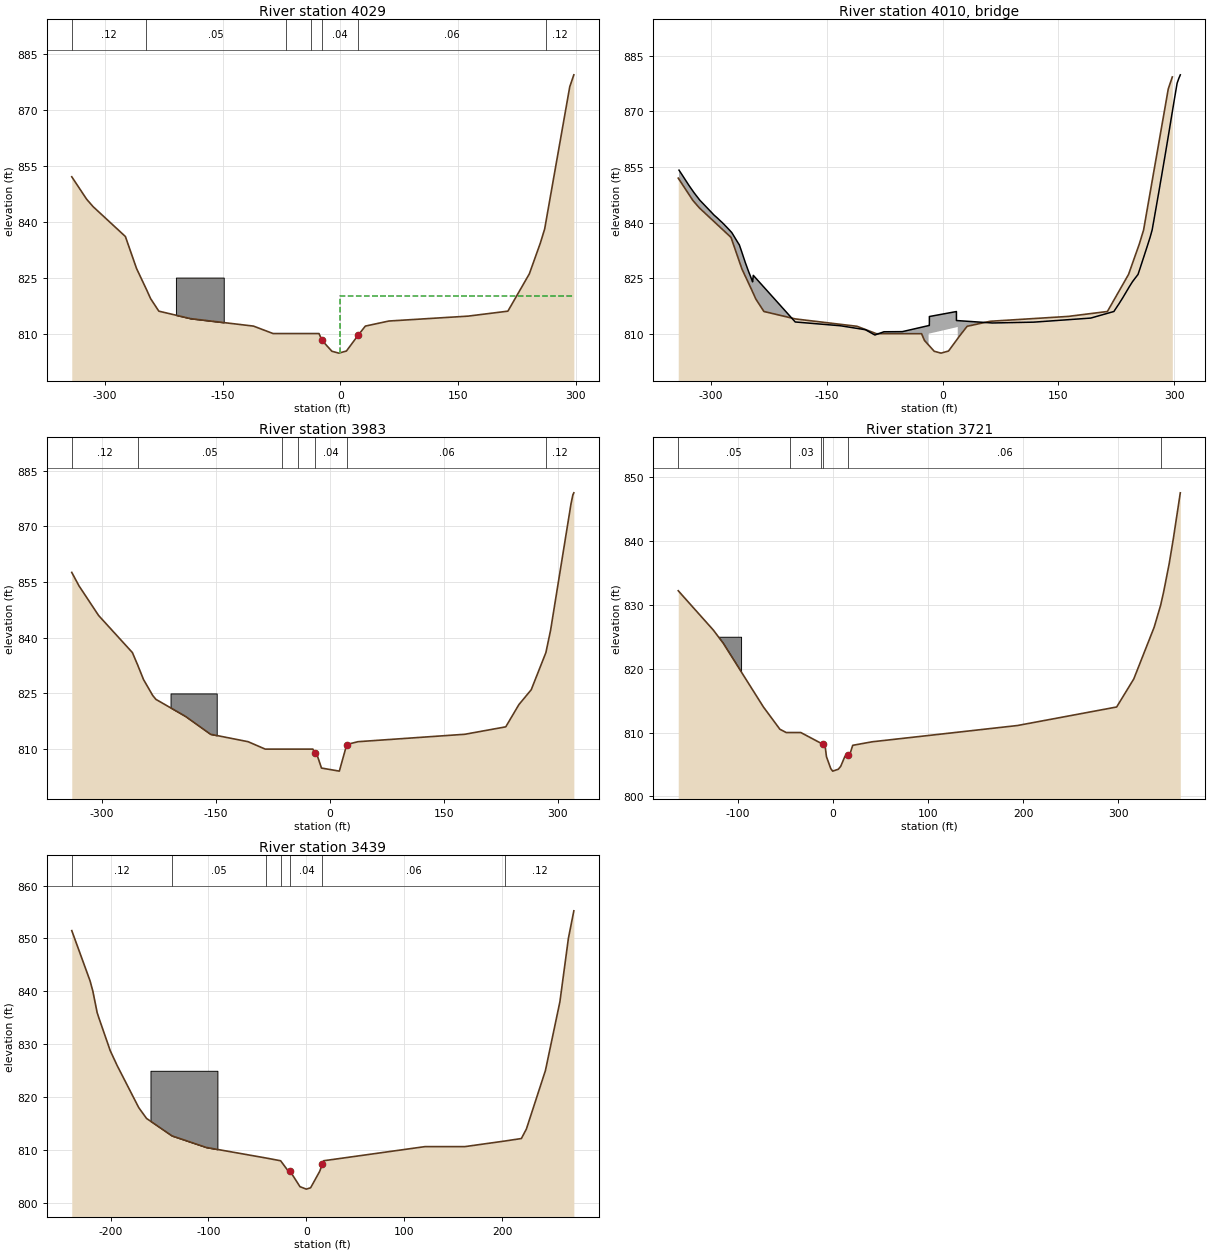
Type RM Length L Ch R = 1 ,4029    ,45.989,46,45.989
BEGIN DESCRIPTION:
US of Driveway (Channel invert from survey data DEN_03)
END DESCRIPTION:
XS GIS Cut Line= 3
586465.0410721034388059.43252789586617.1423699834388107.68541648
586651.9840584134388102.09233641
#Sta/Elev= 30
-341.962     852-322.999  845.98-314.797     844-273.688     836-259.514  827.45
-247.277     822-241.568  819.36-231.102     816 -190.65     814-110.597     812
 -85.564     810 -69.652     810 -37.861     810 -27.133     810 -23.327  808.17
  -10.72  805.26   -1.91  804.76    7.79  805.33  22.736  809.57  31.857     812
  61.811  813.36 162.598  814.67 213.353     816 240.682     826 254.593  834.19
 260.171     838 261.844  839.98 261.844     840 292.126  876.11 297.342  879.31
#Mann= 7 ,-1 , 0
-341.962     .12       0-247.277     .05       0 -69.652     .03       0
 -37.861     .06       0 -23.327     .04       0  22.736     .06       0
 261.844     .12       0
#XS Ineff= 2 , 0
       0 -148.46     820               0
Permanent Ineff=
       F       F
#Block Obstruct= 1 ,-1
 -209.35-148.458     825
Bank Sta=-23.327,22.736
XS Rating Curve= 0 ,0
Exp/Cntr=0.5,0.3

Type RM Length L Ch R = 3 ,4010    ,,,
BEGIN DESCRIPTION:
Driveway (Surveyed Structure DEN_03)
END DESCRIPTION:
Bridge Culvert--1,0,-1,-1, 0
Deck Dist Width WeirC Skew NumUp NumDn MinLoCord MaxHiCord MaxSubmerge Is_Ogee
11,24.8,2.6,0, 111, 111, , , 0.98, 0, 0,0,,
-340.978-337.598-327.986-326.542 -321.26-316.896-314.829-313.845-312.959-311.844
-309.613-308.432-304.626-302.231-295.505-292.126-291.306-289.829 -286.68-285.007
-283.301-275.722-272.605-263.747-263.025-262.927-261.877-259.613-258.038-257.415
 -256.43-255.577-255.184-250.722-248.163-247.638-246.161-245.735-244.849-190.584
-132.218  -99.77 -87.533 -75.755 -52.067  -18.01     -18  -17.01     -17      18
   18.01    19.7   19.71  64.567 117.848 191.798 221.719 227.362 228.084 231.759
 233.301 233.596 235.367 241.142 242.323 245.669 248.163 252.953 255.807 256.135
 258.038 259.252 260.302 262.369 264.206 265.486  267.52 268.537 270.407 271.129
 271.227 271.424 272.375 272.933 274.344 274.606  276.05 276.312 277.756 277.986
 279.462 279.659 281.135 281.299 282.776 282.972 283.104 283.399 284.941 285.827
 287.205 289.206 289.436 290.682 290.912 292.126 300.098 300.886 303.543  305.84
 307.677
  854.16   853.1     850  849.57     848  846.82  846.26     846  845.81  845.57
  845.09  844.83     844  843.48     842  841.39  841.23  840.94  840.32     840
  839.65     838  837.28  834.25  834.06     834  833.37     832     831  830.61
     830  829.47  829.21  826.67  825.34  825.04  824.24     824  825.76  813.17
  812.15  811.08  809.65  810.53  810.56812.1921812.1926  812.24  814.64  815.99
  813.56813.5361813.5359   812.9  813.12  814.22     816  817.78     818  819.22
  819.73  819.84  820.46  822.49  822.89     824   824.7     826  827.79     828
  829.22     830  830.66     832  833.17     834  835.34     836  837.39  837.95
     838  838.23  839.37     840  841.67     842  843.71     844  845.75     846
  847.77     848  849.78     850   851.8     852  852.18  852.53  854.43  855.51
  857.19  859.67  859.96  861.53   861.8  863.32   873.4  874.37  877.63  878.98
  879.89
                                                                                
                                                                                
                                                                                
                                                                                
                                                  809.99810.0381810.0385811.7375
 811.738  811.82
                                                                                
                                                                                
                                                                                
                                                                                
                                                                                
        
-340.978-337.598-327.986-326.542 -321.26-316.896-314.829-313.845-312.959-311.844
-309.613-308.432-304.626-302.231-295.505-292.126-291.306-289.829 -286.68-285.007
-283.301-275.722-272.605-263.747-263.025-262.927-261.877-259.613-258.038-257.415
 -256.43-255.577-255.184-250.722-248.163-247.638-246.161-245.735-244.849-190.584
-132.218  -99.77 -87.533 -75.755 -52.067  -18.01     -18  -17.01     -17      18
   18.01    19.7   19.71  64.567 117.848 191.798 221.719 227.362 228.084 231.759
 233.301 233.596 235.367 241.142 242.323 245.669 248.163 252.953 255.807 256.135
 258.038 259.252 260.302 262.369 264.206 265.486  267.52 268.537 270.407 271.129
 271.227 271.424 272.375 272.933 274.344 274.606  276.05 276.312 277.756 277.986
 279.462 279.659 281.135 281.299 282.776 282.972 283.104 283.399 284.941 285.827
 287.205 289.206 289.436 290.682 290.912 292.126 300.098 300.886 303.543  305.84
 307.677
  854.16   853.1     850  849.57     848  846.82  846.26     846  845.81  845.57
  845.09  844.83     844  843.48     842  841.39  841.23  840.94  840.32     840
  839.65     838  837.28  834.25  834.06     834  833.37     832     831  830.61
     830  829.47  829.21  826.67  825.34  825.04  824.24     824  825.76  813.17
  812.15  811.08  809.65  810.53  810.56812.1921812.1926  812.24  814.64  815.99
  813.56813.5361813.5359   812.9  813.12  814.22     816  817.78     818  819.22
  819.73  819.84  820.46  822.49  822.89     824   824.7     826  827.79     828
  829.22     830  830.66     832  833.17     834  835.34     836  837.39  837.95
     838  838.23  839.37     840  841.67     842  843.71     844  845.75     846
  847.77     848  849.78     850   851.8     852  852.18  852.53  854.43  855.51
  857.19  859.67  859.96  861.53   861.8  863.32   873.4  874.37  877.63  878.98
  879.89
                                                                                
                                                                                
                                                                                
                                                                                
                                                  809.99810.0381810.0385811.7375
 811.738  811.82
                                                                                
                                                                                
                                                                                
                                                                                
                                                                                
        
BR Coef=-1 , 1 , 0 ,, 0 ,,,0.8,0,1.2,0,
WSPro=,,,, 1 ,,,, 0 ,,,, 0 ,,,,-1 ,-1 ,-1 , 0 , 0 , 0 , 0 , 0
BC Design=,, 0 ,, 0 ,,,,,,
BC Use User HTab Curves=0
BC User HTab FreeFlow(D)= 0

Type RM Length L Ch R = 1 ,3983    ,282.31,262,241.69
BEGIN DESCRIPTION:
DS of Driveway (Channel from survey data DEN_03)
END DESCRIPTION:
XS GIS Cut Line= 3
 586460.807400054388072.77667205586616.0786179694388122.03540066
586654.2030024414388115.91501659
#Sta/Elev= 30
-339.665   857.6-330.217     854-304.331     846 -259.81     836-252.822  832.63
-245.177  828.74-233.136  824.47-228.839   823.4-189.862  818.81-156.923     814
-107.513     812 -84.908     810 -63.419     810  -41.24     810 -22.211     810
 -19.783  809.07 -16.503  808.35  -10.86   804.9  12.664  804.07  22.441  811.24
  37.238     812 178.018     814 231.791     816 249.147     822 265.354     826
 284.646     836 290.814     842 317.717  876.08 320.144  878.46 321.457  879.04
#Mann= 7 ,-1 , 0
-339.665     .12       0-252.822     .05       0 -63.419     .03       0
  -41.24     .06       0 -19.783     .04       0  22.441     .06       0
 284.646     .12       0
#Block Obstruct= 1 ,-1
-209.613-148.819     825
Bank Sta=-19.783,22.441
XS Rating Curve= 0 ,0
Exp/Cntr=0.5,0.3

Type RM Length L Ch R = 1 ,3721    ,296.66,282,267.34
XS GIS Cut Line= 2
586498.4380085164388194.51074556586651.6335384094388145.82808896
#Sta/Elev= 30
-162.369   832.2-125.427  826.03 -115.19     824 -72.867     814  -55.61  810.52
 -48.917     810 -44.849     810 -33.596     810  -12.73  808.35 -10.203  808.16
  -8.169     808  -6.693  806.23    -2.2  804.37    -.16  803.96     5.7  804.25
    8.26   804.7  12.795   806.3  16.437  806.48  17.782  806.54  20.899     808
  41.207  808.55 193.963   811.1  298.13     814 316.109  818.39 337.533  826.49
 344.291  829.91 347.441     832 353.346  836.46 357.677  840.36 364.993  847.53
#Mann= 6 ,-1 , 0
-162.369     .05       0 -44.849     .03       0  -12.73     .06       0
 -10.203     .04       0  16.437     .06       0 344.291     .12       0
#Block Obstruct= 1 ,-1
-146.916 -96.358     825
Bank Sta=-10.203,16.437
XS Rating Curve= 0 ,0
Exp/Cntr=0.3,0.1

Type RM Length L Ch R = 1 ,3439    ,178.86,160,141.13
XS GIS Cut Line= 2
586551.8999291764388289.74550673586665.9347545864388182.85214541
#Sta/Elev= 30
-239.567  851.48-220.899     842-217.979     840-213.648     836-211.745  834.92
-200.262  828.79-193.241     826-171.161  818.04-163.222     816-137.238   812.7
-102.067  810.51 -40.879  808.51 -26.247     808 -18.241     806  -16.47     806
   -6.48   803.1       0  802.64    4.39   802.9  13.648     806   16.47   807.4
  17.651     808 121.161  810.67 161.909  810.67 203.248  811.74 219.652   812.2
  224.77     814 244.193  825.04  258.99  838.04 267.651     850 273.228  855.22
#Mann= 7 ,-1 , 0
-239.567     .12       0-137.238     .05       0 -40.879     .03       0
 -26.247     .06       0  -16.47     .04       0   16.47     .06       0
 203.248     .12       0
#Block Obstruct= 1 ,-1
-159.186 -90.814     825
Bank Sta=-16.47,16.47
XS Rating Curve= 0 ,0
Exp/Cntr=0.3,0.1