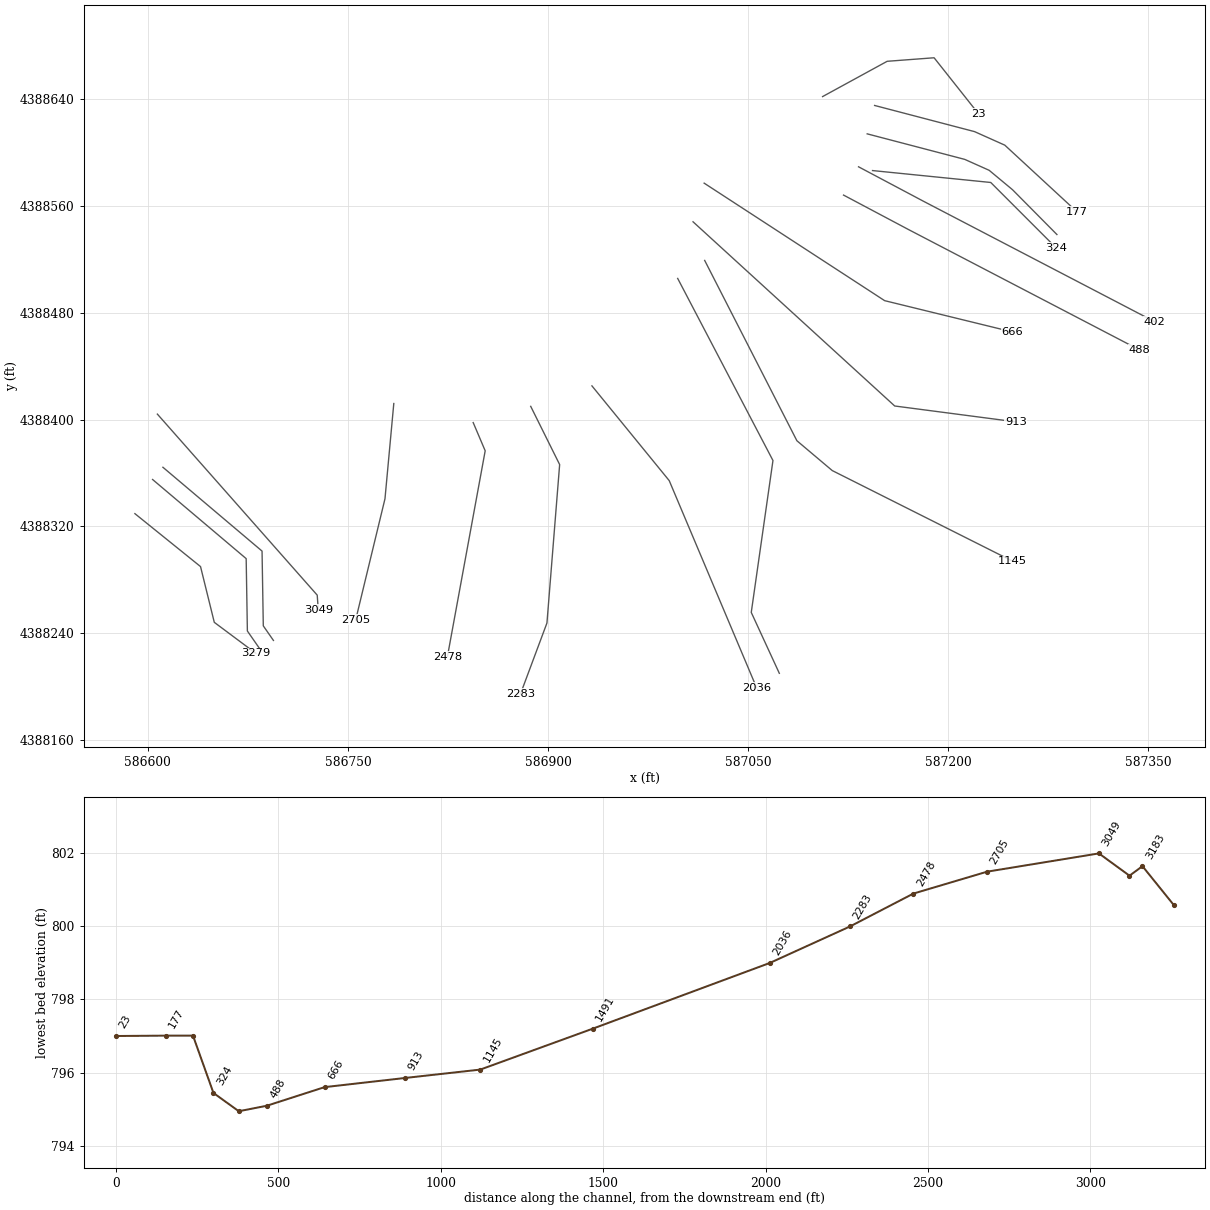
HEC-RAS study DentsRun.prj: Dents Run

--- DentsRun.g01 (geometry) --- (continued)

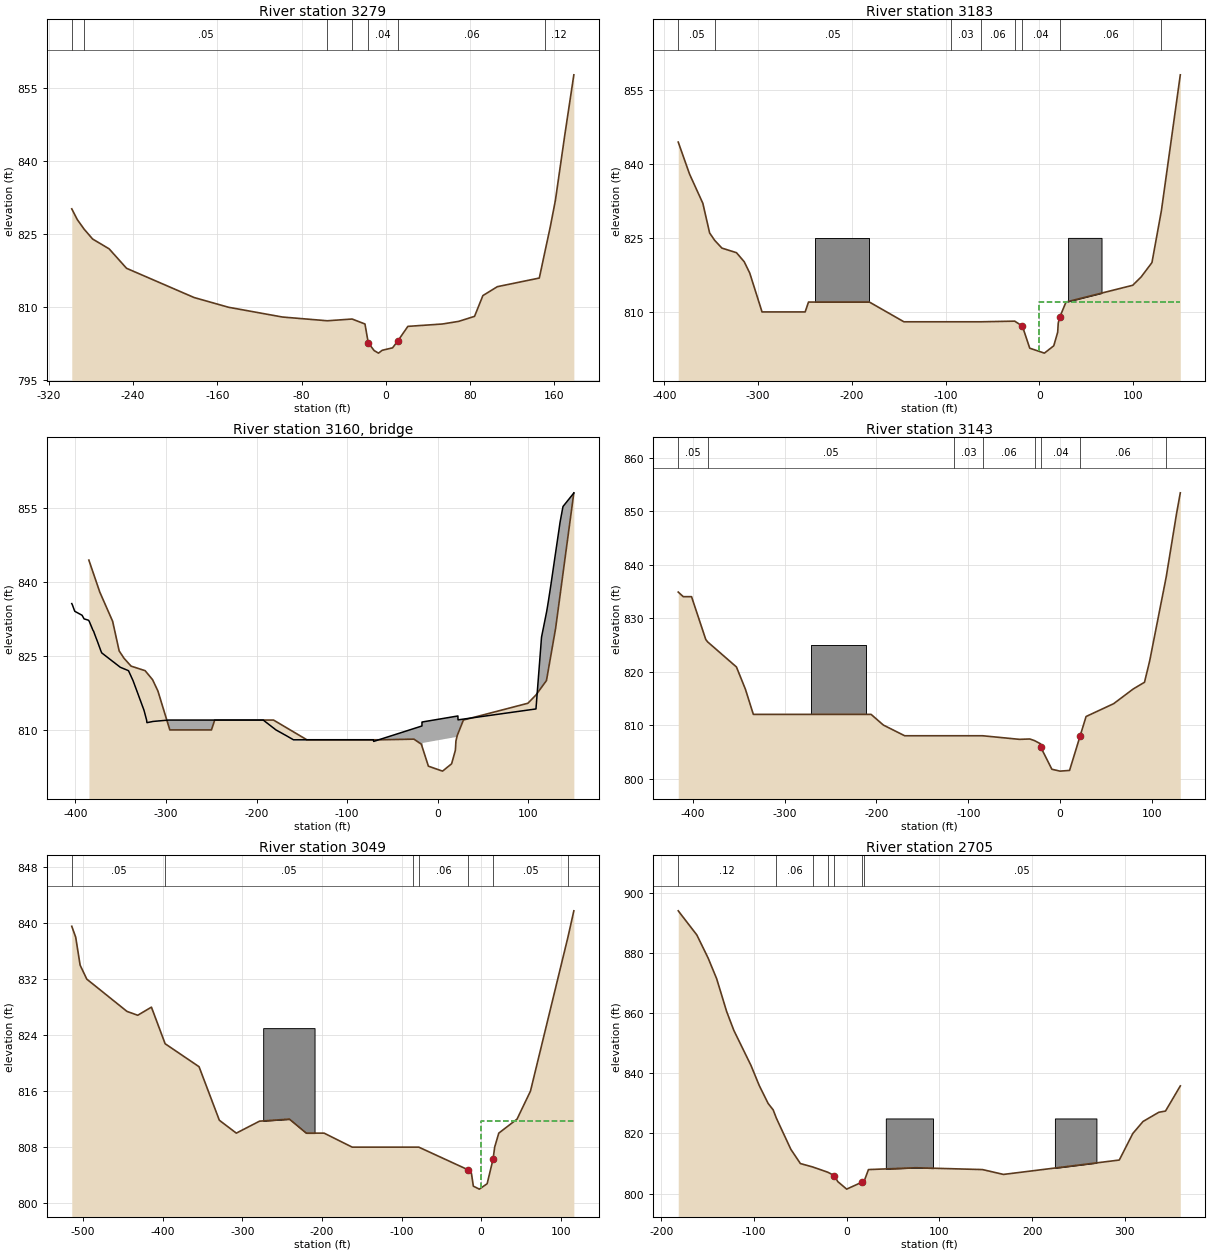
Type RM Length L Ch R = 1 ,3279    ,103.42,96,88.58
BEGIN DESCRIPTION:
(Surveyed XS DEN_02)
END DESCRIPTION:
XS GIS Cut Line= 4
 586590.228529654388329.47313922586639.4415382584388289.78513073
586649.7590183864388247.97876222586680.9796827724388224.69813793
#Sta/Elev= 30
-298.064   830.2-292.815     828 -286.22     826-278.215     824-262.631     822
-246.063     818-181.955     812-149.213     810 -98.163     808 -55.479  807.23
 -32.021  807.59 -19.816  806.57 -16.699  802.71 -11.122  801.12  -6.988  800.59
  -3.478  801.17   6.398  801.68   11.45  803.12  20.899  806.08   53.74  806.57
   69.16  807.11  84.186  808.14  92.093   812.4  105.84  814.23 145.636     816
 150.787  821.22 156.037   826.5 160.892  831.93 169.849   845.4 178.412  857.71
#Mann= 7 ,-1 , 0
-298.064     .12       0 -286.22     .05       0 -55.479     .03       0
 -32.021     .09       0 -16.699     .04       0   11.45     .06       0
 150.787     .12       0
Bank Sta=-16.699,11.45
XS Rating Curve= 0 ,0
Exp/Cntr=0.5,0.3

Type RM Length L Ch R = 1 ,3183    ,40.829,40,39.519
BEGIN DESCRIPTION:
US of Driveway (Channel invert from survey data DEN_03)
END DESCRIPTION:
XS GIS Cut Line= 4
586603.4873298144388355.08243554586673.6644826814388295.75006681
586674.5666906924388241.47737814586684.2501868124388227.55716196
#Sta/Elev= 30
-385.072  844.41-372.966  837.91-358.825     832-351.608     826-346.161  824.49
-338.517  822.93-322.966     822-314.731  820.17-308.858  817.88-295.735     810
 -249.77     810-246.194     812-181.299     812-144.488     808 -94.455     808
 -62.598     808 -26.378  808.13 -18.176  807.11  -10.38  802.65   5.249  801.65
   15.25  803.14   19.42  805.89      20 807.744  21.555  808.91  28.281     812
  99.409   815.4 108.399  817.09 119.915     820  130.02  830.57 150.131  858.04
#Mann= 8 ,-1 , 0
-385.072     .05       0-346.161     .05       0 -94.455     .03       0
 -62.598     .06       0 -26.378     .09       0 -18.176     .04       0
  21.555     .06       0  130.02     .12       0
#XS Ineff= 2 , 0
       0 -181.43     812               0
Permanent Ineff=
       F       F
#Block Obstruct= 2 ,-1
-238.944-182.185     825  30.479  66.142     825
Bank Sta=-18.176,21.555
XS Rating Curve= 0 ,0
Exp/Cntr=0.5,0.3

Type RM Length L Ch R = 3 ,3160    ,,,
BEGIN DESCRIPTION:
Driveway (Surveyed Structure DEN_02)
END DESCRIPTION:
Bridge Culvert--1,0,-1,-1, 0
Deck Dist Width WeirC Skew NumUp NumDn MinLoCord MaxHiCord MaxSubmerge Is_Ogee
15,12.4,2.6,0, 121, 121, , , 0.98, 0, 0,0,,
-403.937-403.248-401.247-401.115 -400.82-400.722-400.689-400.656-400.591-392.552
-390.387-385.531-384.646-380.545-379.823-378.806 -378.15-375.787-375.492-371.785
 -371.49-370.899-350.427-348.786-346.785-344.291-341.339-341.207-336.352 -331.07
-324.278-323.852-321.358-320.997-314.108-296.916-285.171-262.697-243.832-193.504
-193.307-192.979-192.848-192.618-189.862-178.609-167.848-159.285 -154.79-154.724
-153.543-153.346-153.215 -152.69-152.526-149.639-127.559 -126.87-126.181 -115.42
-114.698-113.976-113.156-111.614-109.055-107.185-101.936 -92.028 -87.828 -87.467
  -86.68 -85.466 -84.646 -84.186  -83.76 -83.432 -83.333 -82.907 -82.513 -82.349
 -82.152  -78.15 -77.428 -76.476 -76.312  -76.05 -75.919 -75.787 -74.672 -74.573
 -74.508 -74.409 -73.031 -72.999 -72.408  -71.03 -70.801   -17.5 -17.454  -16.71
   -16.7      20    20.1  22.178   22.31 108.333 114.468 120.144 120.604 121.949
 124.278 124.869 126.148 127.001 129.987 132.349  133.99 134.843 137.106 138.156
   150.1
   835.6  835.34  834.33  834.27  834.14   834.1  834.08  834.06  834.03  833.23
   832.5  832.23     832  830.19     830  829.46  829.14     828  827.86     826
  825.87  825.61   822.7  822.57  822.42  822.23     822  821.95     820  817.39
     814  813.72     812  811.47  811.72     812     812     812     812     812
     812     812     812     812   811.6     810   808.9     808     808     808
     808     808     808     808     808     808     808     808     808     808
     808     808     808     808     808     808     808     808     808     808
     808     808     808     808     808     808     808     808     808     808
     808     808     808     808     808     808     808     808     808     808
     808     808     808     808     808     808  807.67   810.8   811.6 811.623
 811.623 812.762 812.763  812.83  812.04  814.25  828.81     834   834.5     836
  838.77  839.49  841.09  842.17  845.92  848.86   850.9     852  854.26  855.27
     858
                                                                                
                                                                                
                                                                                
                                                                                
                                                                                
                                                                                
                                                                                
                                                                                
                                                                                
                                                                                
  807.36  808.55
                                                                                
        
-403.937-403.248-401.247-401.115 -400.82-400.722-400.689-400.656-400.591-392.552
-390.387-385.531-384.646-380.545-379.823-378.806 -378.15-375.787-375.492-371.785
 -371.49-370.899-350.427-348.786-346.785-344.291-341.339-341.207-336.352 -331.07
-324.278-323.852-321.358-320.997-314.108-296.916-285.171-262.697-243.832-193.504
-193.307-192.979-192.848-192.618-189.862-178.609-167.848-159.285 -154.79-154.724
-153.543-153.346-153.215 -152.69-152.526-149.639-127.559 -126.87-126.181 -115.42
-114.698-113.976-113.156-111.614-109.055-107.185-101.936 -92.028 -87.828 -87.467
  -86.68 -85.466 -84.646 -84.186  -83.76 -83.432 -83.333 -82.907 -82.513 -82.349
 -82.152  -78.15 -77.428 -76.476 -76.312  -76.05 -75.919 -75.787 -74.672 -74.573
 -74.508 -74.409 -73.031 -72.999 -72.408  -71.03 -70.801   -17.5 -17.454  -16.71
   -16.7      20    20.1  22.178   22.31 108.333 114.468 120.144 120.604 121.949
 124.278 124.869 126.148 127.001 129.987 132.349  133.99 134.843 137.106 138.156
   150.1
   835.6  835.34  834.33  834.27  834.14   834.1  834.08  834.06  834.03  833.23
   832.5  832.23     832  830.19     830  829.46  829.14     828  827.86     826
  825.87  825.61   822.7  822.57  822.42  822.23     822  821.95     820  817.39
     814  813.72     812  811.47  811.72     812     812     812     812     812
     812     812     812     812   811.6     810   808.9     808     808     808
     808     808     808     808     808     808     808     808     808     808
     808     808     808     808     808     808     808     808     808     808
     808     808     808     808     808     808     808     808     808     808
     808     808     808     808     808     808     808     808     808     808
     808     808     808     808     808     808  807.67   810.8   811.6 811.623
 811.623 812.762 812.763  812.83  812.04  814.25  828.81     834   834.5     836
  838.77  839.49  841.09  842.17  845.92  848.86   850.9     852  854.26  855.27
     858
                                                                                
                                                                                
                                                                                
                                                                                
                                                                                
                                                                                
                                                                                
                                                                                
                                                                                
                                                                                
  807.36  808.55
                                                                                
        
BR Coef=-1 , 1 , 0 ,, 0 ,,,0.8,0,1.2,0,
WSPro=,,,, 1 ,,,, 0 ,,,, 0 ,,,,-1 ,-1 ,-1 , 0 , 0 , 0 , 0 , 0
BC Design=,, 0 ,, 0 ,,,,,,
BC Use User HTab Curves=0
BC User HTab FreeFlow(D)= 0

Type RM Length L Ch R = 1 ,3143    ,69.75,94,117.73
BEGIN DESCRIPTION:
DS of Driveway (Channel from survey data DEN_03))
END DESCRIPTION:
XS GIS Cut Line= 4
 586611.235345914388364.24777165586685.5699708284388301.39801088
 586686.505706844388245.33005018586694.1013229344388234.40906605
#Sta/Elev= 30
-415.945  834.86-410.466     834-401.444     834-385.958     826-383.858  825.54
-352.526  820.86-342.749   816.7-334.121     812 -205.84     812-192.454     810
-169.193     808-115.026     808 -84.186     808 -44.094  807.33 -32.907   807.4
 -27.756  807.09 -21.129  806.49 -20.965  805.86  -8.858  801.74       0  801.39
    10.4  801.52      22 808.012  28.412   811.6  58.465     814   79.79  816.75
   92.06     818  97.703     822 115.715  837.69 126.969  849.52  131.07  853.41
#Mann= 8 ,-1 , 0
-415.945     .05       0-383.858     .05       0-115.026     .03       0
 -84.186     .06       0 -27.756     .09       0 -20.965     .04       0
      22     .06       0 115.715     .12       0
#Block Obstruct= 1 ,-1
-271.096 -211.22     825
Bank Sta=-20.965,22
XS Rating Curve= 0 ,0
Exp/Cntr=0.5,0.3

Type RM Length L Ch R = 1 ,3049    ,370.97,344,317.03
XS GIS Cut Line= 3
586607.0778738584388404.10342015 586726.934379344388268.36988247
586727.7268593494388257.25687433
#Sta/Elev= 30
-514.206  839.55-509.285     838-503.707     834-495.341     832-444.849  827.39
-431.365  826.84 -414.14     828-396.916  822.77-354.331  819.49-328.839  811.84
-307.513     810-278.346  811.71-240.814     812-219.652     810-197.277     810
-162.008     808 -85.039     808 -78.346     808 -16.437  804.76  -12.27  804.31
   -9.79  802.42   -2.27     802    7.52  802.77      15  806.29  16.995     808
  22.146     810  45.079     812  61.942     816 109.022     838 116.437  841.76
#Mann= 7 ,-1 , 0
-514.206     .05       0-396.916     .05       0 -85.039     .03       0
 -78.346     .06       0 -16.437     .04       0      15     .05       0
 109.022     .12       0
#XS Ineff= 2 , 0
       0 -273.79  811.75               0
Permanent Ineff=
       F       F
#Block Obstruct= 1 ,-1
-273.786-209.252     825
Bank Sta=-16.437,15
XS Rating Curve= 0 ,0
Exp/Cntr=0.3,0.1

Type RM Length L Ch R = 1 ,2705    ,229.93,227,224.07
XS GIS Cut Line= 3
586784.3495560494388412.04041224586777.7353959674388340.60138736
586755.7745556964388249.85023424
#Sta/Elev= 30
-181.726  894.04-161.614     886-149.442  878.32-140.256  871.46-129.429  860.51
-121.719  854.28-103.248  842.64  -94.39     836 -84.744     830 -79.265  827.84
 -75.853   825.1 -60.203  814.73 -49.902     810 -36.844  808.89 -20.604  807.15
 -13.255     806  -9.547     804       0   801.5   16.47  803.81  18.438  803.78
  23.524     808   74.77  808.61 146.621     808 169.193  806.39  294.16  811.17
  308.76     820 319.816     824 336.778  827.05 344.029  827.46 360.007  835.82
#Mann= 7 ,-1 , 0
-181.726     .12       0 -75.853     .06       0 -36.844     .03       0
 -20.604     .09       0 -13.255    .035       0   16.47     .09       0
  18.438     .05       0
#Block Obstruct= 2 ,-1
  42.257  93.176     825 224.705 269.488     825
Bank Sta=-13.255,16.47
XS Rating Curve= 0 ,0
Exp/Cntr=0.3,0.1

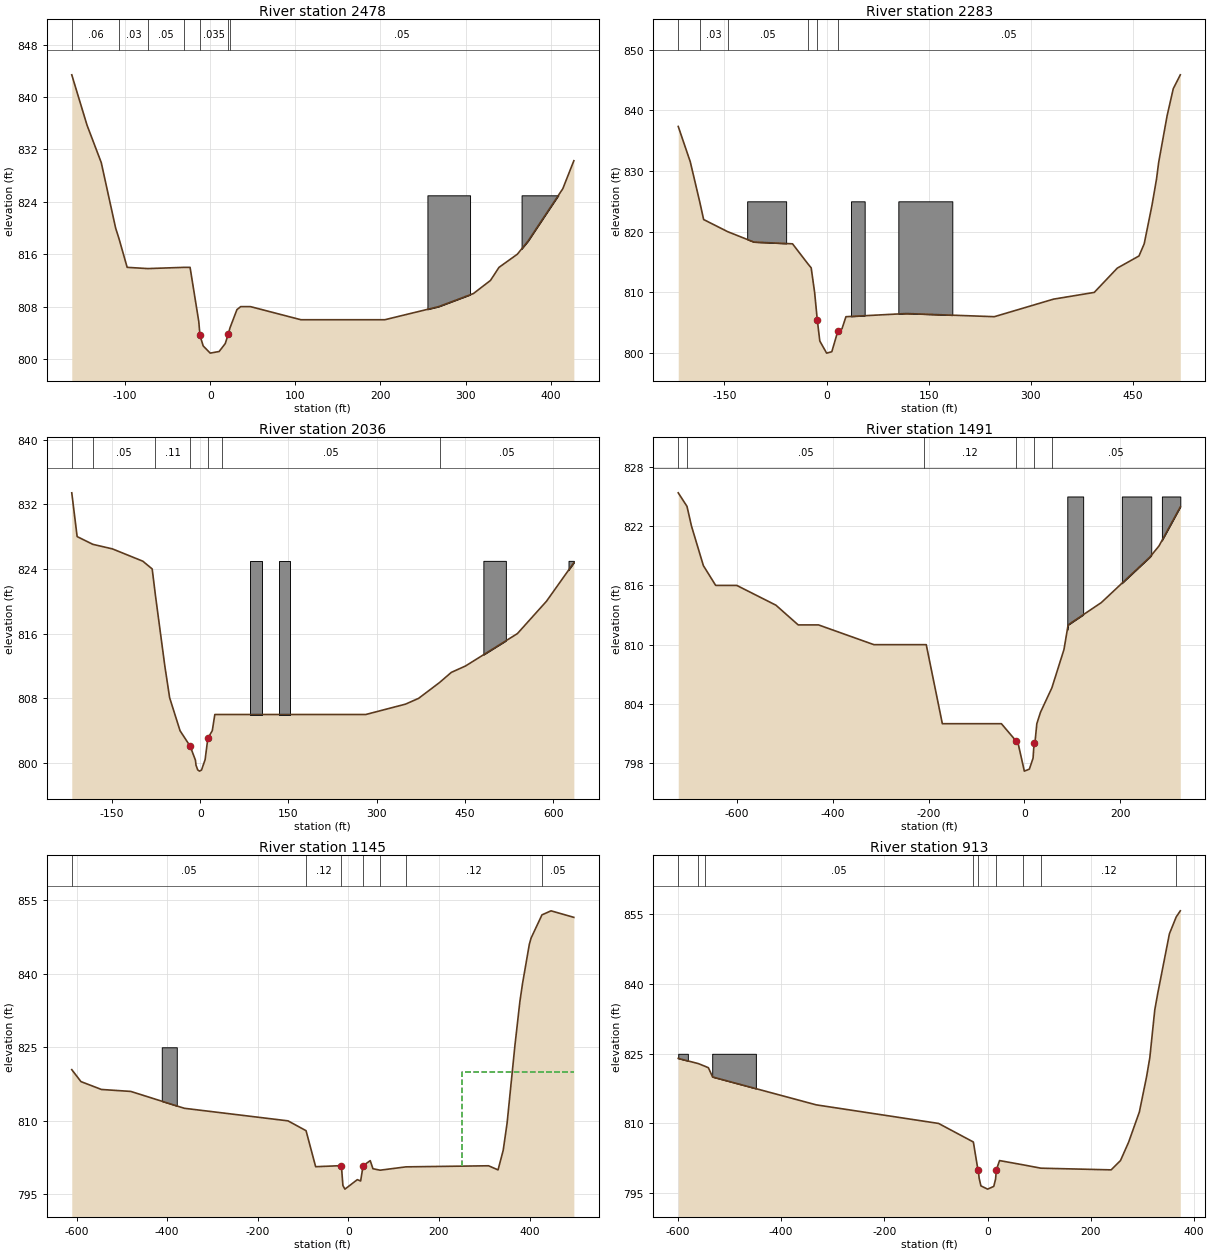
Type RM Length L Ch R = 1 ,2478    ,191.66,195,198.34
XS GIS Cut Line= 3
586843.8800447854388397.75138807586852.8746928964388376.58607581
586824.564868546 4388222.3328899
#Sta/Elev= 30
-162.664   843.4-144.751  835.72-128.018     830-111.122     820-107.218   818.4
 -97.572     814 -73.294  813.81 -30.381     814 -23.655     814 -13.419  805.72
 -12.008   803.6  -8.235     802       0   800.9   10.52  801.15  17.651  802.35
  21.293  803.84  23.228  804.75  31.398  807.54  35.827     808  47.343     808
 106.594     806 205.217     806 268.406     808 309.318     810 329.331     812
  339.37     814  360.86     816 373.392     818 414.304     826 427.297  830.28
#Mann= 7 ,-1 , 0
-162.664     .06       0-107.218     .03       0 -73.294     .05       0
 -30.381     .11       0 -12.008    .035       0  21.293     .11       0
  23.228     .05       0
#Block Obstruct= 2 ,-1
 255.249 305.348     825 365.879 427.329     825
Bank Sta=-12.008,21.293
XS Rating Curve= 0 ,0
Exp/Cntr=0.3,0.1

Type RM Length L Ch R = 1 ,2283    ,221.96,247,272.12
XS GIS Cut Line= 4
586887.0061973184388409.92205222586908.7018615864388366.26554768
586899.1768614684388247.46974621586879.3343812234388194.28824155
#Sta/Elev= 30
-217.881  837.33 -200.23  831.52-186.089   824.8-180.577     822-145.276     820
 -106.89  818.29 -50.066     818 -27.526  814.71 -22.671  814.04 -17.618     810
 -13.747  805.51 -10.039     802       0     800    7.62  800.23  16.437  803.62
  22.539     804  28.346     806 117.126  806.52 246.227     806 333.136  808.89
 392.946     810 426.772     814 458.629     816 466.273     818 477.756  824.38
 484.383  828.68 487.533  831.42 499.902  839.09 508.957  843.55 519.291  845.83
#Mann= 6 ,-1 , 0
-217.881     .06       0-186.089     .03       0-145.276     .05       0
 -27.526     .11       0 -13.747    .035       0  16.437     .05       0
#Block Obstruct= 3 ,-1
-116.667 -59.449     825  35.794   55.84     825 105.282 184.547     825
Bank Sta=-13.747,16.437
XS Rating Curve= 0 ,0
Exp/Cntr=0.3,0.1

Type RM Length L Ch R = 1 ,2036    ,571.85,545,518.07
XS GIS Cut Line= 3
586932.9121258854388425.26873241586990.8576546014388354.22899553
587056.3408874114388199.04921761
#Sta/Elev= 30
-218.307  833.41-209.186     828-182.448  827.04-149.245  826.48 -97.605  824.96
 -81.627     824 -76.017  820.69 -60.138     812 -51.936  808.07 -34.285     804
 -16.962  802.07   -8.05  800.34   -7.15  799.73   -4.17  799.15  -1.181     799
    2.24  799.14    8.35  800.42      13 803.067  20.538     804  24.836     806
  36.581     806 281.365     806 348.884  807.28  371.26     808 406.726  809.95
 426.804  811.21 450.951     812 539.075     816 588.517     820 635.072  824.77
#Mann= 7 ,-1 , 0
-218.307     .03       0-182.448     .05       0 -76.017     .11       0
 -16.962    .035       0      13     .11       0  36.581     .05       0
 406.726     .05       0
#Block Obstruct= 4 ,-1
  84.055 104.757     825 133.596  151.87     825 481.299 519.488     825
 626.017 635.039     825
Bank Sta=-16.962,13
XS Rating Curve= 0 ,0
Exp/Cntr=0.3,0.1

Type RM Length L Ch R = 1 ,1491    ,313.13,346,385.67
XS GIS Cut Line= 4
 586997.20663868 4388505.8334694587068.6426155634388369.31049972
587052.3723913624388255.40673831587073.4066396224388209.76598575
#Sta/Elev= 30
-722.375  825.37-704.101     824-694.685     822-669.882     818-644.226     816
-600.263     816 -518.57     814-471.949     812-429.593     812-313.944     810
-209.482     810-204.724     810-171.129     802 -47.867     802 -17.028  800.24
 -12.959     800       0   797.2   10.44   797.4   18.21  798.51  20.276     800
  21.982     800   26.05     802  33.629  803.15  57.448  805.63   82.71  809.51
  91.371     812 160.663  814.26 262.303  818.88 281.135     820 325.525  823.95
#Mann= 6 ,-1 , 0
-722.375     .03       0-704.101     .05       0-209.482     .12       0
 -17.028    .035       0  20.276     .06       0  57.448     .05       0
#Block Obstruct= 3 ,-1
  89.633 122.769     825  203.51 264.895     825 287.073 325.525     825
Bank Sta=-17.028,20.276
XS Rating Curve= 0 ,0
Exp/Cntr=0.3,0.1

Type RM Length L Ch R = 1 ,1145    ,232.69,232,224.51
BEGIN DESCRIPTION:
(Surveyed XS DEN_01X)
END DESCRIPTION:
XS GIS Cut Line= 4
 587017.448406934388519.32696557587086.586191784 4388384.1359719
587113.0946481124388361.76974762587248.3130737834388293.84506678
#Sta/Elev= 30
-610.531  820.44-590.223     818-545.046   816.4-480.249     816-361.975  812.56
-133.202     810  -93.34     808 -72.113  800.65 -15.322  800.87 -11.909  796.81
   -7.48  796.08  19.849  798.01  27.231  797.74  32.579  800.84   48.36  801.89
  54.364  800.24  70.177  799.94 127.362  800.62 309.646  800.84 330.577     800
 341.962     804 350.558  809.56 367.946  825.48 378.806  834.34 384.613     838
 399.639     846 403.412  847.24 427.526     852 447.572  852.82   497.9  851.49
#Mann= 7 ,-1 , 0
-610.531     .05       0  -93.34     .12       0 -15.322    .035       0
  32.579     .12       0  70.177     .06       0 127.362     .12       0
 427.526     .05       0
#XS Ineff= 2 , 0
       0                     250       0     820
Permanent Ineff=
       F       F
#Block Obstruct= 1 ,-1
-411.844-378.707     825
Bank Sta=-15.322,32.579
XS Rating Curve= 0 ,0
Exp/Cntr=0.3,0.1

Type RM Length L Ch R = 1 ,913     ,230.28,247,263.72
XS GIS Cut Line= 3
587008.7158868224388548.30125393587159.9241206914388410.18722822
587250.8093858144388398.28174008
#Sta/Elev= 30
-599.278     824-560.138  822.88 -548.13  822.34-540.879     822-532.677     820
-331.923     814 -95.013     810 -27.559     806 -18.701     800     -18     800
  -16.43  798.24  -12.95  796.55       0  795.85   11.98  796.44   15.46  798.01
      17     800   23.13     802  68.504  801.09 103.281  800.36 239.304     800
 257.415     802 273.163  805.95 293.996  812.46 307.874     820 314.239  824.15
 323.885  834.47 329.593     838 352.231  850.85 365.354  854.47 373.327  855.79
#Mann= 9 ,-1 , 0
-599.278     .05       0-560.138     .03       0 -548.13     .05       0
 -27.559     .12       0     -18    .035       0      17     .12       0
  68.504     .06       0 103.281     .12       0 365.354     .05       0
#Block Obstruct= 2 ,-1
-599.278-580.676     825-533.465-448.885     825
Bank Sta=-18,17
XS Rating Curve= 0 ,0
Exp/Cntr=0.3,0.1

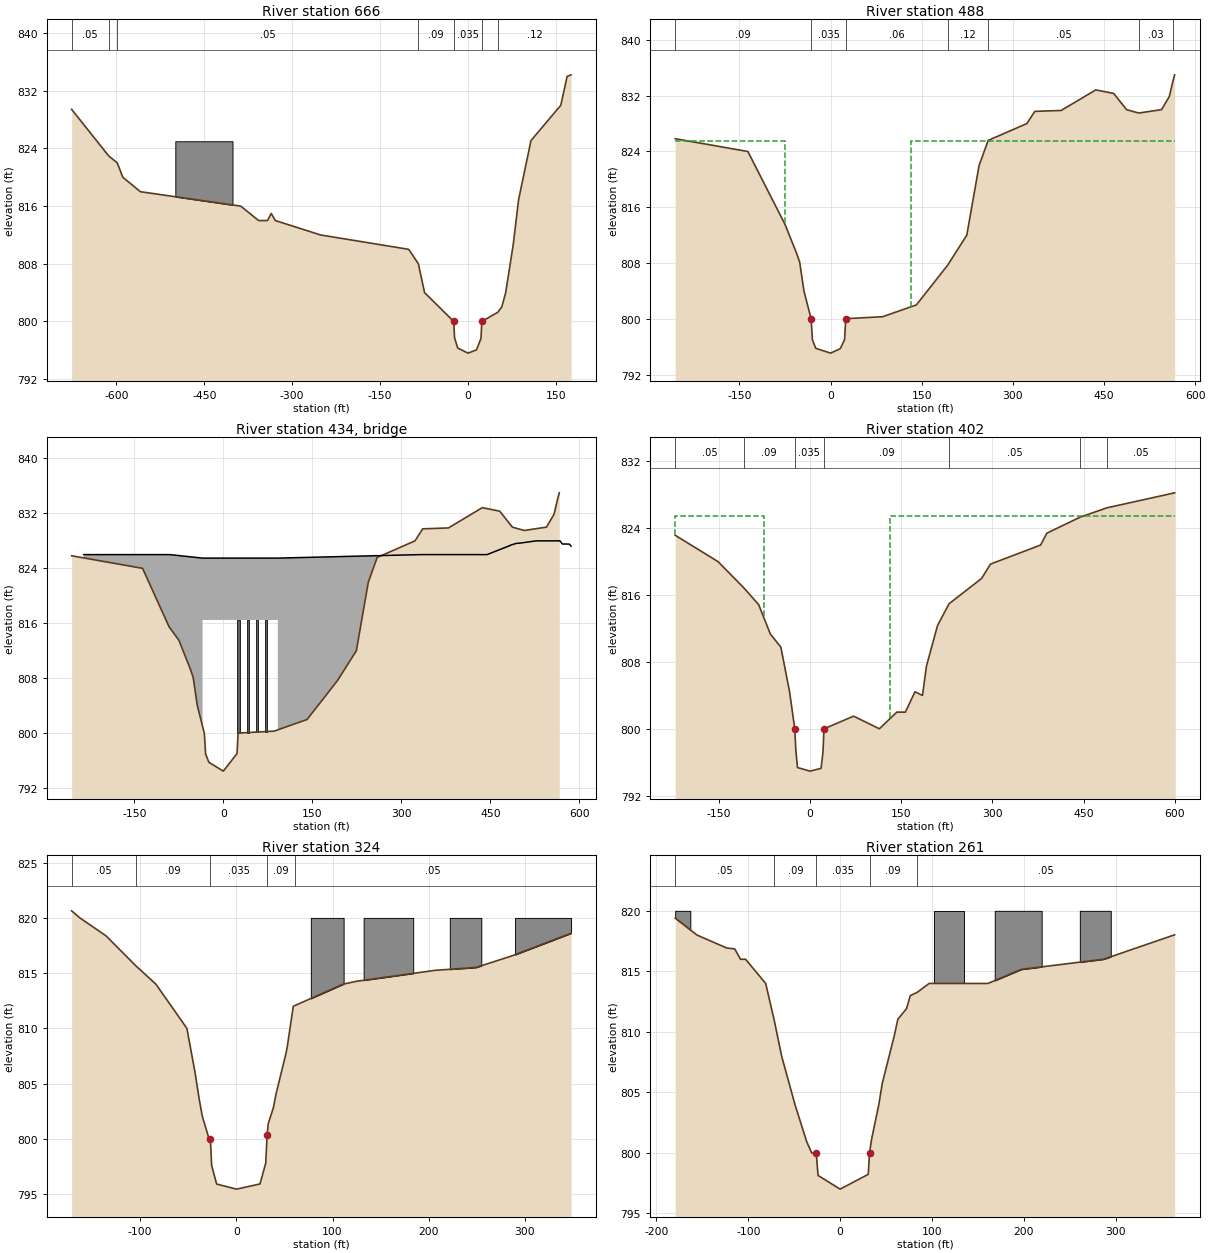
Type RM Length L Ch R = 1 ,666     ,186.52,178,166.77
BEGIN DESCRIPTION:
(Channel invert from effective profile)
END DESCRIPTION:
XS GIS Cut Line= 3
587017.0491189254388577.27249429587152.383368598 4388489.1670052
 587248.032657784388465.74922091
#Sta/Elev= 30
-676.411  829.43-613.156  822.97-598.491     822-588.976     820-558.957     818
-387.697     816-357.119     814-341.896     814-335.564  814.98-328.576     814
-251.411     812-100.755     810  -84.35     808 -73.753     804     -24     800
  -22.49  797.73  -17.19  796.31     .42   795.6   14.95  796.05   22.65  797.66
      24     800  51.148  801.26  58.104     802  64.797     804  77.953  810.82
  86.745  816.86  107.94  825.09 158.924     830 169.685     834 176.444  834.22
#Mann= 7 ,-1 , 0
-676.411     .05       0-613.156     .03       0-598.491     .05       0
  -84.35     .09       0     -24    .035       0      24     .09       0
  51.148     .12       0
#Block Obstruct= 1 ,-1
-499.377-401.706     825
Bank Sta=-24,24
XS Rating Curve= 0 ,0
Exp/Cntr=0.5,0.3

Type RM Length L Ch R = 1 ,488     ,85.929,86,87.319
BEGIN DESCRIPTION:
US of CSX Transportation (Channel invert from effective profile)
END DESCRIPTION:
XS GIS Cut Line= 3
587121.5589442174388568.32966218587170.2263608184388542.50700586
587343.5783149614388452.19171674
#Sta/Elev= 30
-255.709  825.83-136.122     824 -74.934  813.54 -56.398  809.52  -50.82  808.14
 -43.799     804     -32     800  -29.88     797  -24.39  795.78     .12  795.09
      16  795.73   23.05  797.04      25 800.028   85.63  800.31 141.206     802
 192.585  807.68 224.245     812 244.488     822 259.448  825.59  323.13     828
 336.155  829.75 379.495  829.88 436.581  832.83 466.043  832.32 487.205     830
 507.152  829.51 544.816     830 557.579  831.88 563.287     834 566.339  834.99
#Mann= 7 ,-1 , 0
-255.709     .09       0     -32    .035       0      25     .06       0
 192.585     .12       0 259.448     .05       0 507.152     .03       0
 563.287     .05       0
#XS Ineff= 2 ,-1
-255.709     -75  825.49   131.9 566.339  825.49
Permanent Ineff=
       F       F
Bank Sta=-32,25
XS Rating Curve= 0 ,0
Exp/Cntr=0.5,0.3

Type RM Length L Ch R = 3 ,434     ,,,
BEGIN DESCRIPTION:
CSX Transportation (structure dimentions & channel invert from effective HEC-2 data)
END DESCRIPTION:
Bridge Culvert--1,0,-1,-1, 0
Deck Dist Width WeirC Skew NumUp NumDn MinLoCord MaxHiCord MaxSubmerge Is_Ogee
44,17,3,0, 85, 85, , , 0.98, 0, 0,0,,
-235.433 -90.059  -35.01     -35    91.9   91.91 333.005 362.434 363.714 364.894
 364.961 365.059 365.125 383.824 394.391  394.98 396.883 397.014  397.08 397.113
 397.244 397.277 425.951 426.181 426.214 426.247 426.804 427.001 429.757  430.61
 436.089  436.22 437.172 437.303 437.434  438.32 438.451 438.615 440.092 440.551
 444.029 444.587 481.923 481.988 482.054 482.087 482.152 482.218 482.283 482.316
 484.186 493.832  494.39 501.608 527.526 528.084  528.74 529.429 530.217 532.021
 537.073 538.222 538.747 538.976 539.239 539.469 539.698 539.896  540.19 540.846
 541.175 541.699 565.256 565.846 566.437 567.028 567.585  571.49 573.753 576.017
 578.281 580.512  581.66 583.333 586.253
     826     826  825.49  825.49  825.49  825.49     826     826     826     826
     826     826     826     826     826     826     826     826     826     826
     826     826     826     826     826     826     826     826     826     826
     826     826     826     826     826     826     826     826     826     826
     826     826  827.27  827.27  827.27  827.28  827.28  827.28  827.28  827.28
  827.37  827.63  827.63  827.69     828     828     828     828     828     828
     828     828     828     828     828     828     828     828     828     828
     828     828     828     828     828     828     828  827.54  827.54  827.54
  827.54  827.53  827.53  827.53  827.23
                          816.49  816.49
                                                                                
                                                                                
                                                                                
                                                                                
                                                                                
                                                                                
                                                                                
                                        
-235.433 -90.059  -35.01     -35    91.9   91.91 333.005 362.434 363.714 364.894
 364.961 365.059 365.125 383.824 394.391  394.98 396.883 397.014  397.08 397.113
 397.244 397.277 425.951 426.181 426.214 426.247 426.804 427.001 429.757  430.61
 436.089  436.22 437.172 437.303 437.434  438.32 438.451 438.615 440.092 440.551
 444.029 444.587 481.923 481.988 482.054 482.087 482.152 482.218 482.283 482.316
 484.186 493.832  494.39 501.608 527.526 528.084  528.74 529.429 530.217 532.021
 537.073 538.222 538.747 538.976 539.239 539.469 539.698 539.896  540.19 540.846
 541.175 541.699 565.256 565.846 566.437 567.028 567.585  571.49 573.753 576.017
 578.281 580.512  581.66 583.333 586.253
     826     826  825.49  825.49  825.49  825.49     826     826     826     826
     826     826     826     826     826     826     826     826     826     826
     826     826     826     826     826     826     826     826     826     826
     826     826     826     826     826     826     826     826     826     826
     826     826  827.27  827.27  827.27  827.28  827.28  827.28  827.28  827.28
  827.37  827.63  827.63  827.69     828     828     828     828     828     828
     828     828     828     828     828     828     828     828     828     828
     828     828     828     828     828     828     828  827.54  827.54  827.54
  827.54  827.53  827.53  827.53  827.23
                          816.49  816.49
                                                                                
                                                                                
                                                                                
                                                                                
                                                                                
                                                                                
                                                                                
                                        
Pier Skew, UpSta & Num, DnSta & Num=  ,25.882, 2 ,25.882, 2 , 0 , 0 , 0 ,,
       4       4
     794  816.49
       4       4
     794  816.49
Pier Skew, UpSta & Num, DnSta & Num=  ,41.411, 2 ,41.411, 2 , 0 , 0 , 0 ,,
       4       4
     794  816.49
       4       4
     794  816.49
Pier Skew, UpSta & Num, DnSta & Num=  ,56.94, 2 ,56.94, 2 , 0 , 0 , 0 ,,
       4       4
     794  816.49
       4       4
     794  816.49
Pier Skew, UpSta & Num, DnSta & Num=  ,72.469, 2 ,72.469, 2 , 0 , 0 , 0 ,,
       4       4
     794  816.49
       4       4
     794  816.49
BR Coef=-1 , 1 , 1 ,1.25, 0 ,,,0.8,-1,1.176,0,
WSPro=,,,, 1 ,,,, 0 ,,,, 0 ,,,,-1 ,-1 ,-1 , 0 , 0 , 0 , 0 , 0
BR U #Sta/Elev= 30
-255.709  825.83-136.122     824 -91.437  815.49 -74.934  813.54 -56.398  809.52
  -50.82  808.14 -43.799     804     -32     800  -29.88     797  -24.39  795.78
       0  794.49   23.05  797.04      25 800.028   85.63  800.31 141.206     802
 192.585  807.68 224.245     812 244.488     822 259.448  825.59  323.13     828
 336.155  829.75 379.495  829.88 436.581  832.83 466.043  832.32 487.205     830
 507.152  829.51 544.816     830 557.579  831.88 563.287     834 566.339  834.99
BR U #Mann= 7
-255.709     .09     -32    .035      25     .06 192.585     .12 259.448     .05
 507.152    .035 563.287     .05
BR D #Sta/Elev= 30
-221.686  823.17-151.312  820.02-109.121   816.9 -84.383  814.87 -65.256  811.36
 -47.933  809.78 -33.629  804.46     -25     800  -23.28  797.42  -20.53  795.37
       0  794.49    18.2  795.27   21.37   797.2      23     800  71.785  801.52
 114.075  800.01 142.848     802 156.923     802 172.671  804.44 185.039     804
 191.503  807.49 209.744  812.36 228.707  814.97 282.218     818 296.883  819.72
 379.298     822   389.6  823.42 444.062  825.33 488.155  826.45  599.77  828.25
BR D #Mann= 7
-221.686     .05-109.121     .09     -25    .035      23     .09 228.707     .05
 444.062    .035 488.155     .05
BC Design=,, 0 ,, 0 ,,,,,,
BC Use User HTab Curves=0
BC User HTab FreeFlow(D)= 0

Type RM Length L Ch R = 1 ,402     ,64.55,78,95.65
BEGIN DESCRIPTION:
DS of CSX Transportation (Channel invert from effective profile)
END DESCRIPTION:
XS GIS Cut Line= 3
587132.8091123564388589.53155044587181.3942329564388563.74851812
587354.666939098  4388473.475901
#Sta/Elev= 30
-221.686  823.17-151.312  820.02-109.121   816.9 -84.383  814.87 -65.256  811.36
 -47.933  809.78 -33.629  804.46     -25     800  -23.28  797.42  -20.53  795.37
       0  794.94    18.2  795.27   21.37   797.2      23     800  71.785  801.52
 114.075  800.01 142.848     802 156.923     802 172.671  804.44 185.039     804
 191.503  807.49 209.744  812.36 228.707  814.97 282.218     818 296.883  819.72
 379.298     822   389.6  823.42 444.062  825.33 488.155  826.45  599.77  828.25
#Mann= 7 ,-1 , 0
-221.686     .05       0-109.121     .09       0     -25    .035       0
      23     .09       0 228.707     .05       0 444.062     .03       0
 488.155     .05       0
#XS Ineff= 2 ,-1
-221.686     -75  825.49   131.9  599.77  825.49
Permanent Ineff=
       F       F
Bank Sta=-25,23
XS Rating Curve= 0 ,0
Exp/Cntr=0.5,0.3

Type RM Length L Ch R = 1 ,324     ,69.38,63,53.75
BEGIN DESCRIPTION:
(Channel invert from effective profile)
END DESCRIPTION:
XS GIS Cut Line= 3
587143.300328485 4388586.7091024587231.9361695814388577.77846229
587280.8840021864388528.83062969
#Sta/Elev= 30
-171.293  820.64-162.762     820-135.597  818.38-104.364  815.65 -83.661     814
 -51.444     810 -42.946     806 -38.747  803.65 -35.433  802.05 -28.379     800
     -27     800  -25.71  797.61  -20.53   795.9     .19  795.44   24.62  795.91
   30.54  797.79      32 800.341  33.202  801.37  38.517  802.82  41.142     804
  51.673  807.75  52.854  808.28  59.219     812  60.827  812.06 111.089     814
 124.934  814.26 206.529  815.25 249.213  815.51 286.909  816.57 348.097  818.61
#Mann= 5 ,-1 , 0
-171.293     .05       0-104.364     .09       0     -27    .035       0
      32     .09       0  60.827     .05       0
#Block Obstruct= 4 ,-1
  77.461 111.549     820 132.382 183.891     820 221.949 254.757     820
 289.862 348.097     820
Bank Sta=-27,32
XS Rating Curve= 0 ,0
Exp/Cntr=0.5,0.3

Type RM Length L Ch R = 1 ,261     ,85.22,84,94.446
BEGIN DESCRIPTION:
US of U.S. Route 19 (Channel invert from effective profile)
END DESCRIPTION:
XS GIS Cut Line= 5
587139.2861124364388614.23863874 587212.453353344388595.08500651
587230.7413535664388586.90417441587248.2825937834388572.32559023
587281.5454181944388538.75186981
#Sta/Elev= 30
 -179.56   819.4-155.873     818-123.491  816.93-114.698  816.85-108.465     816
-102.953     816 -81.037     814 -71.588   810.9 -63.681     808  -49.18     804
  -36.45  800.94 -30.971     800     -26     800  -24.06  798.14       0  797.01
   30.59  798.23      32     800  34.186  801.11  42.126     804  45.866  805.75
  58.858  809.65  62.795  811.04  72.343  811.93  76.378     813  83.596  813.25
  96.916     814 160.925     814  197.08  815.16 286.745     816 364.173  818.02
#Mann= 5 ,-1 , 0
 -179.56     .05       0 -71.588     .09       0     -26    .035       0
      32     .09       0  83.596     .05       0
#Block Obstruct= 4 ,-1
 -179.56-163.123     820 102.067 134.318     820 168.307  219.39     820
 260.925 294.619     820
Bank Sta=-26,32
XS Rating Curve= 0 ,0
Exp/Cntr=0.5,0.3

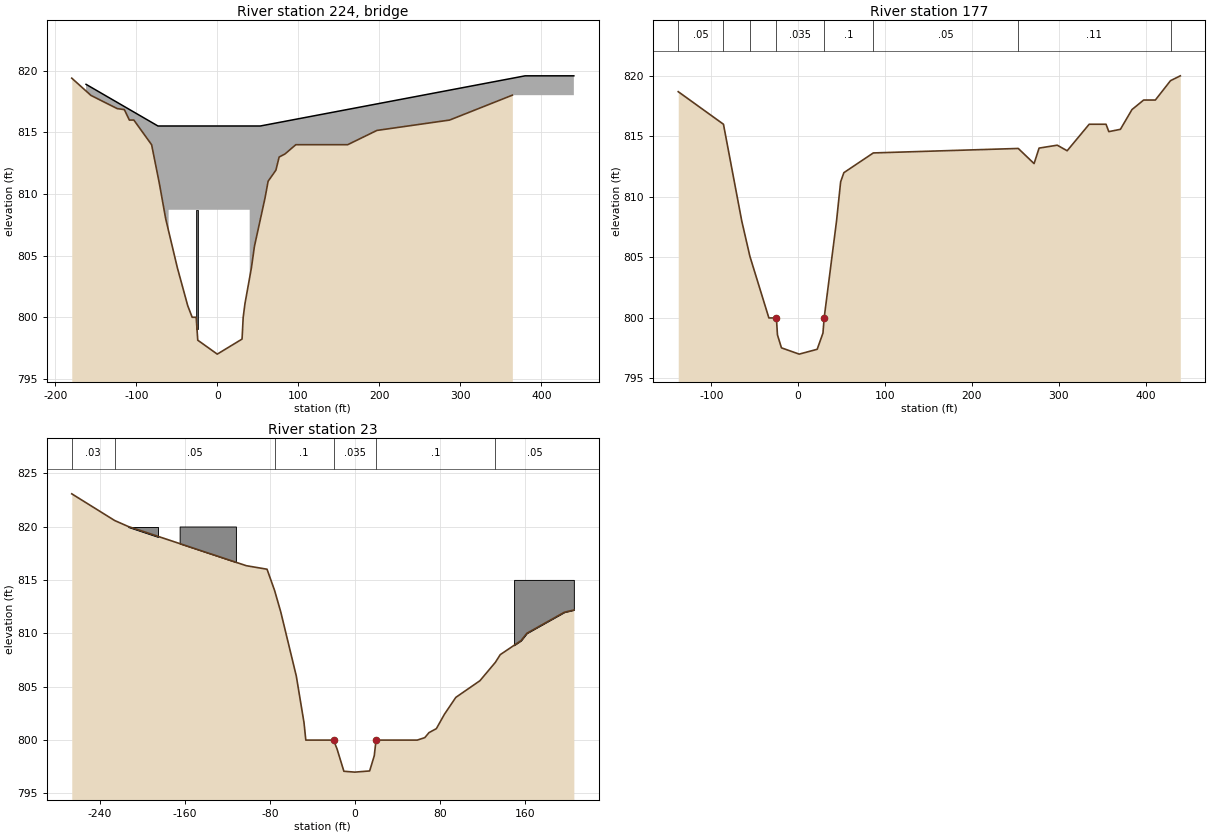
Type RM Length L Ch R = 3 ,224     ,,,
BEGIN DESCRIPTION:
U.S. Route 19 (structure dimensions & channel invert from effective HEC-2 data)
END DESCRIPTION:
Bridge Culvert--1,0,-1,-1, 0
Deck Dist Width WeirC Skew NumUp NumDn MinLoCord MaxHiCord MaxSubmerge Is_Ogee
21,36,3,0, 9, 9, , , 0.98, 0, 0,0,,
-161.942  -73.21   -60.1     -60      40   40.01   53.11  379.92  440.06
   818.9  815.52  815.52  815.52  815.52  815.52  815.52  819.59  819.59
                          808.72  808.72
-161.942  -73.21   -60.1     -60      40   40.01   53.11  379.92  440.06
   818.9  815.52  815.52  815.52  815.52  815.52  815.52  819.59  819.59
                          808.72  808.72
Pier Skew, UpSta & Num, DnSta & Num=  ,-25, 2 ,-25, 2 , 0 , 0 , 0 ,,
     3.4     3.4
     795  808.72
     3.4     3.4
     795  808.72
BR Coef=-1 , 1 , 1 ,1.25, 0 ,,,0.8,0,1.288,0,
WSPro=,,,, 1 ,,,, 0 ,,,, 0 ,,,,-1 ,-1 ,-1 , 0 , 0 , 0 , 0 , 0
BC Design=,, 0 ,, 0 ,,,,,,
BC Use User HTab Curves=0
BC User HTab FreeFlow(D)= 0

Type RM Length L Ch R = 1 ,177     ,154,154,154
BEGIN DESCRIPTION:
DS of U.S. Route 19 (Channel invert from effective profile)
END DESCRIPTION:
XS GIS Cut Line= 4
587144.8578565054388635.52282301587219.7807454314388615.90894276
587242.4792017114388605.75300664587296.7579863824388555.61950202
#Sta/Elev= 30
-138.025  818.69 -85.958     816 -64.862     808 -55.479  805.08 -33.661     800
     -25     800  -23.78   798.6  -19.19  797.53    1.23  797.01   21.97  797.41
   28.61  798.75      30     800  44.226     808  48.983  811.25   52.69     812
  86.581  813.63 253.478     814 271.686  812.75 277.461  814.03 298.392  814.27
 309.777  813.81 335.138     816 354.528     816 357.743  815.39 371.096  815.58
 384.383  817.21 397.835     818 411.319     818 428.773   819.6 440.059     820
#Mann= 8 ,-1 , 0
-138.025     .05       0 -85.958      .1       0 -55.479     .08       0
     -25    .035       0      30      .1       0  86.581     .05       0
 253.478     .11       0 428.773     .05       0
Bank Sta=-25,30
XS Rating Curve= 0 ,0
Exp/Cntr=0.5,0.3

Type RM Length L Ch R = 1 ,23      ,23,23,23
BEGIN DESCRIPTION:
(Channel invert from effective profile)
END DESCRIPTION:
XS GIS Cut Line= 4
587105.8556480234388642.17660709587154.2731286214388668.63629542
587189.4622890564388671.28195945587222.8013134684388629.21346293
#Sta/Elev= 30
-266.601  823.06-226.181  820.56-213.386     820-102.231  816.33 -82.677     816
 -75.525     814 -69.751     812 -55.118     806 -47.867  801.64 -46.161     800
     -20     800  -16.74  799.17   -10.3  797.08       0     797   13.96  797.11
   18.31  798.53      20     800  58.825     800  65.912  800.23  69.882   800.7
  76.804  801.07   84.35  802.41  95.144     804 117.848  805.56 132.382  807.28
 136.975     808 156.529  809.31 162.041     810 197.343  811.97 206.299  812.18
#Mann= 6 ,-1 , 0
-266.601     .03       0-226.181     .05       0 -75.525      .1       0
     -20    .035       0      20      .1       0 132.382     .05       0
#XS Ineff= 2 , 0
       0                      80       0
Permanent Ineff=
       F       F
#Block Obstruct= 3 ,-1
    -230    -185     820    -165    -112     820     150 206.299     815
Bank Sta=-20,20
XS Rating Curve= 0 ,0
Exp/Cntr=0.3,0.1
Stream Node=Dents Run       ,Reach 1         , 0 , 0 ,Upstream end
Stream Node=Dents Run       ,Reach 1         , 0 , 1 ,Downstream end

Chan Stop Cuts=-1
Use User Specified Reach Order=0
Composite Channel Slope=5