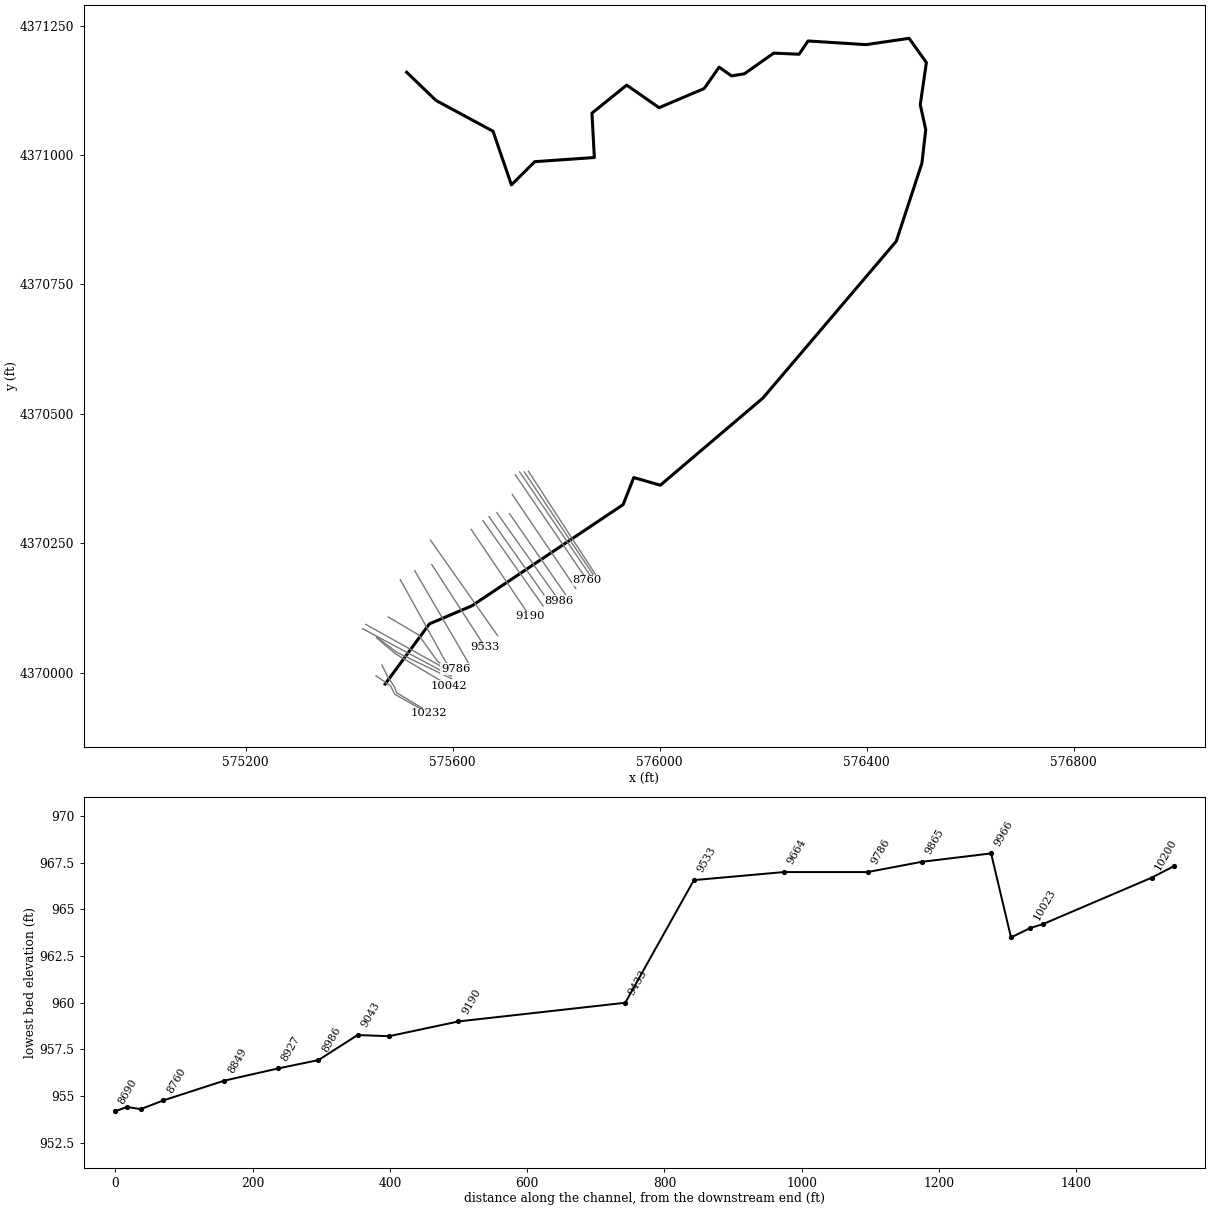
--- HickmanRun.prj (project) ---

Proj Title=Hickman Run
Current Plan=p01
Default Exp/Contr=0.3,0.1
English Units
Geom File=g02
Flow File=f02
Flow File=f01
Plan File=p01
Plan File=p02
Y Axis Title=Elevation
X Axis Title(PF)=Main Channel Distance
X Axis Title(XS)=Station
BEGIN DESCRIPTION:
Detailed Study for Hickman Run
Upper Monongahela Watershed, Marion County, WV
Submitted by RAMPP for FEMA Region III
Model date: October 2015
Description: Detailed model for Hickman Run. Long culverts at cross-sections 5548-8116 and cross-sections 9553-9966 were modeled as overland flow using HY-8. The ground profile elevations for these cross-sections are the overland elevations.
HEC-RAS version 4.1.0
Vertical Datum: NAVD88 (feet)
Horizontal Datum: NAD_1983_UTM_Zone_17N
END DESCRIPTION:
DSS Export Rating Curves= 0
DSS Export Rating Curve Sorted= 0
DSS Export Volume Flow Curves= 0
DXF Filename=..\..\..\..\..\DETAILED\Basin_HUC_Stream\HEC-RAS\Hickman Run\HickmanRun.
DXF OffsetX= 0
DXF OffsetY= 0
DXF ScaleX= 1
DXF ScaleY= 10

--- HickmanRun.p01 (plan) ---

Plan Title=Hickman Run - Multiprofile
Program Version=4.10
Short Identifier=Multiprofile
Geom File=g02
Flow File=f02
Subcritical Flow
K Sum by GR= 0
Std Step Tol= 0.01
Critical Tol= 0.01
Num of Std Step Trials= 20
Max Error Tol= 0.3
Flow Tol Ratio= 0.001
Split Flow NTrial= 30
Split Flow Tol= 0.02
Split Flow Ratio= 0.02
Log Output Level= 0
Friction Slope Method= 1
Unsteady Friction Slope Method= 2
Unsteady Bridges Friction Slope Method= 1
Parabolic Critical Depth
Global Vel Dist= 0 , 0 , 0
Global Log Level= 0
CheckData=True
Encroach Param=-1 ,0,0, 0
Computation Interval=1HOUR
Output Interval=1HOUR
Run HTab= 0
Run UNet= 0
Run PostProcess= 0
Run WQNet= 0
UNET Theta= 1
UNET Theta Warmup= 1
UNET ZTol= 0.02
UNET ZSATol= 0.05
UNET MxIter= 20
UNET MaxInSteps= 0
UNET DtIC= 0
UNET DtMin= 0
UNET MaxCRTS= 20
UNET WFStab= 2
UNET SFStab= 1
UNET WFX= 1
UNET SFX= 1
UNET DSS MLevel= 4
UNET DZMax Abort= 98.43
UNET Convert EG Bridges= 0
UNET Use Existing IB Tables=-1
UNET Froude Reduction=False
UNET Froude Limit= 1
UNET Froude Power= 10
UNET Time Slicing=0,0, 5
UNET Junction Losses=0
Instantaneous Interval=1HOUR
DSS File=dss
Write IC File= 0
Write IC File at Sim End=0
Echo Input=False
Echo Parameters=False
Echo Output=False
Write Detailed= 0
WQ AD Non Conservative
WQ ULTIMATE=-1
WQ Max Comp Step=1HOUR
WQ Output Interval=15MIN
WQ Output Selected Increments= 0
WQ Output face flow=0
WQ Output face velocity=0
WQ Output face area=0
WQ Output face dispersion=0
WQ Output cell volume=0
WQ Output cell surface area=0
WQ Output cell continuity=0
WQ Output cumulative cell continuity=0
WQ Output face conc=0
WQ Output face dconc_dx=0
WQ Output face courant=0
WQ Output face peclet=0
WQ Output face adv mass=0
WQ Output face disp mass=0
WQ Output cell mass=0
WQ Output cell source sink temp=0
WQ Output cell source sink nsm=0
WQ Output MaxMinRange=-1
WQ Daily Max Min Mean=-1
WQ Daily Range=0
WQ Daily Time=0
WQ Create Restart=0
WQ Fixed Restart=0
WQ System Summary=0
WQ Use Fixed Temperature=0
Sorting and Armoring Iterations= 10
XS Update Threshold= 0.02
Hydraulics Update Threshold= 0.02
Energy Slope Method= 1
Volume Change Method= 0
XS Weighting Method= 0
Number of US Weighted Cross Sections= 1
Number of DS Weighted Cross Sections= 1
Upstream XS Weight=0.25
Main XS Weight=0.5
Downstream XS Weight=0.25
Number of DS XS's Weighted with US Boundary= 1
Upstream Boundary Weight= 1
Weight of XSs Associated with US Boundary= 0
Number of US XS's Weighted with DS Boundary= 1
Downstream Boundary Weight= 0.5
Weight of XSs Associated with DS Boundary= 0.5
Sediment Output Level= 4
Mass or Volume Output= 0
Output Increment Type= 1
Profile and TS Output Increment= 10
XS Output Flag= 0
XS Output Increment= 10
Disregard all LS=0
Disregard all Conn=0
Disregard all Breaches=0
Disregard all Pumps=0

--- HickmanRun.p02 (plan) ---

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Plan Title=Hickman Run - Floodway
Short Identifier=Floodway
Geom File=g02
Flow File=f01
Encroach Param=-1 ,0,0, 2
Encroach River=Hickman Run
Encroach Reach=Reach 1
Encroach Node=10232
       1     -20    93.9
Encroach Node=10200
       1   -26.8     110
Encroach Node=10042
       1     -40      50
Encroach Node=10023
       1     -30      30
Encroach Node=9995
       1  -34.15   20.93
Encroach Node=9966
       1  -33.33   27.76
Encroach Node=9865
       1  -41.63    11.3
Encroach Node=9786
       1     -40   44.16
Encroach Node=9664
       1     -40   16.96
Encroach Node=9533
       1   -22.9   38.81
Encroach Node=9433
       1  -13.71   10.54
Encroach Node=9190
       1  -13.16   13.16
Encroach Node=9089
       1     -28      40
Encroach Node=9043
       1  -12.86    39.6
Encroach Node=8986
       1     -20   19.36
Encroach Node=8927
       1     -19   18.21
Encroach Node=8849
       1     -21   16.96
Encroach Node=8760
       1     -18      35
Encroach Node=8727
       1     -18      40
Encroach Node=8707
       1     -18      40
Encroach Node=8690
       1     -18      40
Encroach Node=8657
       1     -18      39
Encroach Node=8531
       1     -26      65
Encroach Node=8184
       1     -35     140
Encroach Node=8155
       1   -18.9     140
Encroach Node=8140
       1  -17.42     142
Encroach Node=8116
       1      40  140.42
Encroach Node=7918
       1 -145.37   17.96
Encroach Node=7675
       1 -217.22   13.91
Encroach Node=7504
       1 -208.73      10
Encroach Node=7283
       1  -214.7   11.25
Encroach Node=7066
       1 -191.96   10.25
Encroach Node=6844
       1 -168.93   39.29
Encroach Node=6638
       1    -200   14.22
Encroach Node=6386
       1 -198.49    8.09
Encroach Node=6191
       1  -78.61   10.32
Encroach Node=5963
       1  -10.27   10.89
Encroach Node=5753
       1  -87.12   31.17
Encroach Node=5548
       1  -77.35   54.53
Encroach Node=5353
       1     -50      23
Encroach Node=5316
       1  -16.82   10.51
Encroach Node=5044
       1  -17.73   10.25
Encroach Node=4784
       1     -40      20
Encroach Node=4603
       1     -45   60.07
Encroach Node=4534
       1   -39.3   31.82
Encroach Node=4479
       1     -70      29
Encroach Node=4373
       1  -127.4      11
Encroach Node=4256
       1    -103      18
Encroach Node=4147
       1     -27   29.64
Encroach Node=4073
       1  -14.95      16
Encroach Node=3724
       1  -45.47      20
Encroach Node=3355
       1  -30.55      38
Encroach Node=3038
       1     -50      20
Encroach Node=2537
       1     -11      80
Encroach Node=2264
       1     -15    8.73
Encroach Node=2157
       1  -14.04   14.19
Encroach Node=2001
       1  -15.72   16.35
Encroach Node=1867
       1  -18.57      18
Encroach Node=1667
       1     -11      16
Encroach Node=1391
       1     -16   11.45
Encroach Node=1211
       1     -40      20
Encroach Node=1178
       1     -25      22
Encroach Node=1052
       1     -27   19.75
Encroach Node=815
       1     -31   16.83
Encroach Node=739
       1   -29.1   17.88
Encroach Node=702
       1  -23.85   18.27
Encroach Node=560
       1     -18    16.3
Encroach Node=166
       1     -43      28

--- HickmanRun.f02 (steady flow) ---

Flow Title=Hickman Run - Multiprofile
Program Version=5.00
Number of Profiles= 6
Profile Names=10PCT,4PCT,2PCT,1PCT,1PCT_PLUS,0.2PCT
River Rch & RM=Hickman Run,Reach 1         ,10232
     552     712     866    1008    1451    1299
River Rch & RM=Hickman Run,Reach 1         ,10200
     554     713     868    1010    1454    1301
River Rch & RM=Hickman Run,Reach 1         ,10023
     573     736     893    1039    1497    1337
River Rch & RM=Hickman Run,Reach 1         ,9966
     169     332     489     635    1093     933
River Rch & RM=Hickman Run,Reach 1         ,9190
     592     759     921    1072    1543    1377
River Rch & RM=Hickman Run,Reach 1         ,8531
     665     849    1026    1194    1719    1528
River Rch & RM=Hickman Run,Reach 1         ,8140
     670     855    1034    1204    1734    1543
River Rch & RM=Hickman Run,Reach 1         ,8116
     188     373     552     772    1252    1061
River Rch & RM=Hickman Run,Reach 1         ,5316
     670     855    1034    1204    1734    1543
River Rch & RM=Hickman Run,Reach 1         ,5044
     822    1041    1254    1461    2104    1862
River Rch & RM=Hickman Run,Reach 1         ,4073
     833    1055    1271    1481    2132    1887
River Rch & RM=Hickman Run,Reach 1         ,2537
     843    1068    1287    1499    2158    1910
River Rch & RM=Hickman Run,Reach 1         ,1391
     882    1115    1341    1563    2250    1989
River Rch & RM=Hickman Run,Reach 1         ,166
     888    1124    1352    1575    2268    2005
Boundary for River Rch & Prof#=Hickman Run,Reach 1         , 1
Up Type= 0
Dn Type= 3
Dn Slope=0.00334
Boundary for River Rch & Prof#=Hickman Run,Reach 1         , 2
Up Type= 0
Dn Type= 3
Dn Slope=0.00334
Boundary for River Rch & Prof#=Hickman Run,Reach 1         , 3
Up Type= 0
Dn Type= 3
Dn Slope=0.00334
Boundary for River Rch & Prof#=Hickman Run,Reach 1         , 4
Up Type= 0
Dn Type= 3
Dn Slope=0.00334
Boundary for River Rch & Prof#=Hickman Run,Reach 1         , 5
Up Type= 0
Dn Type= 3
Dn Slope=0.00334
Boundary for River Rch & Prof#=Hickman Run,Reach 1         , 6
Up Type= 0
Dn Type= 3
Dn Slope=0.00334
DSS Import GetInterval= 0
DSS Import GetPeak= 0
DSS Import FillOption= 0

--- HickmanRun.f01 (steady flow) ---

Flow Title=Hickman Run - Floodway
Program Version=5.00
Number of Profiles= 2
Profile Names=1PCT,FLOODWAY
River Rch & RM=Hickman Run,Reach 1         ,10232
    1008    1008
River Rch & RM=Hickman Run,Reach 1         ,10200
    1010    1010
River Rch & RM=Hickman Run,Reach 1         ,10023
    1039    1039
River Rch & RM=Hickman Run,Reach 1         ,9966
     635     635
River Rch & RM=Hickman Run,Reach 1         ,9190
    1072    1072
River Rch & RM=Hickman Run,Reach 1         ,8531
    1194    1194
River Rch & RM=Hickman Run,Reach 1         ,8140
    1204    1204
River Rch & RM=Hickman Run,Reach 1         ,8116
     772     772
River Rch & RM=Hickman Run,Reach 1         ,5316
    1204    1204
River Rch & RM=Hickman Run,Reach 1         ,5044
    1461    1461
River Rch & RM=Hickman Run,Reach 1         ,4073
    1481    1481
River Rch & RM=Hickman Run,Reach 1         ,2537
    1499    1499
River Rch & RM=Hickman Run,Reach 1         ,1391
    1563    1563
River Rch & RM=Hickman Run,Reach 1         ,166
    1575    1575
Boundary for River Rch & Prof#=Hickman Run,Reach 1         , 1
Up Type= 0
Dn Type= 3
Dn Slope=0.00334
Boundary for River Rch & Prof#=Hickman Run,Reach 1         , 2
Up Type= 0
Dn Type= 3
Dn Slope=0.00334
DSS Import GetInterval= 0
DSS Import GetPeak= 0
DSS Import FillOption= 0

--- HickmanRun.g02 (geometry) ---

Geom Title=Hickman Run
Program Version=4.10

River Reach=Hickman Run     ,Reach 1
Reach XY= 30
575469.7162162124369977.57464041 575555.343681274370093.97166585
575637.2861142834370128.79506628575929.561885895 4370324.3821807
 575950.151126154370376.63709335576001.4581107844370361.90306116
576199.5781132324370530.18009524576457.3901484184370833.28541099
 576506.898813034370984.02730085576514.3054531224371048.79730165
576503.7227969914371097.26964625576515.5764691384371178.54761526
576482.1338127244371225.32831983576398.7222436934371213.13631968
576286.9764663124371220.24730377576269.6181060984371194.63495946
576220.5117774914371196.75027148 576163.785448794371156.74527099
576139.0204484844371152.72495894576115.1027921884371169.65964715
576086.3144318324371128.38363064575999.1081027554371091.34128618
 575936.456461984371134.94597472575869.3577891514371080.75863005
575874.0151332094370995.03362899575758.8769317864370987.02348489
575713.7817712284370942.11730033575678.2207547894371045.83159762
575567.9441134264371105.36513435575511.3640887274371159.83899103

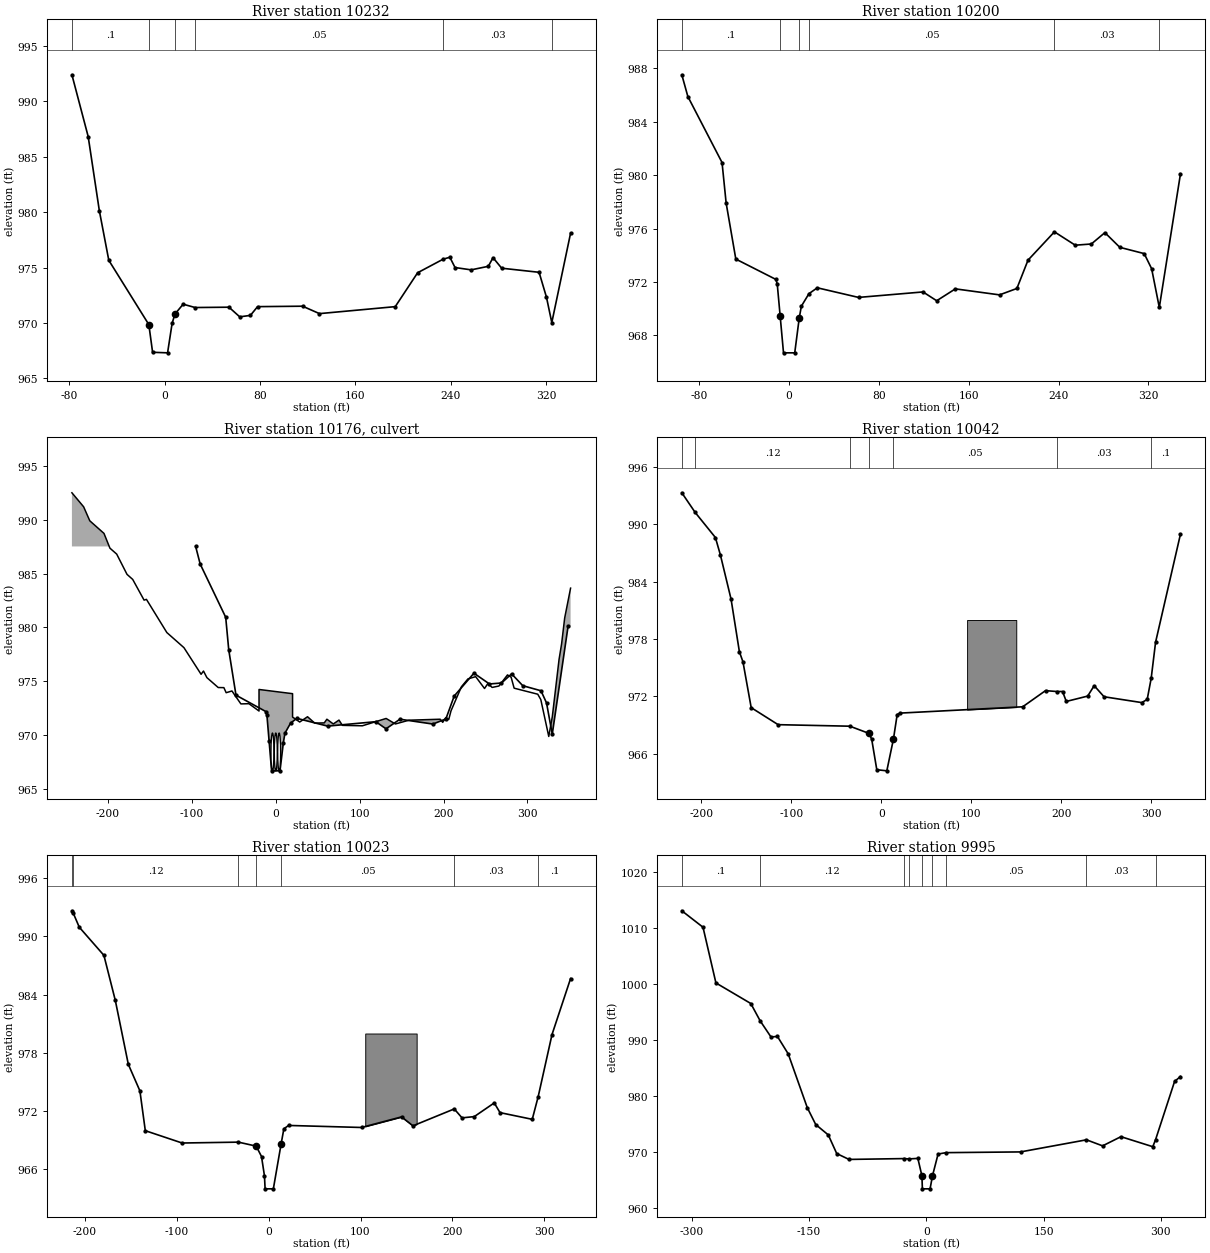
Type RM Length L Ch R = 1 ,10232   ,44.65,32,21.62
XS GIS Cut Line= 4
575452.0500079944369993.63150461575480.2013363414369974.36814437
575488.2450084414369958.07048817575553.6489932494369921.02814372
#Sta/Elev= 30
 -77.657  992.41 -64.009  986.83 -54.659  980.14 -46.719  975.66 -13.156  969.86
     -10  967.36   2.559  967.31   6.365  969.97   8.727  970.81  15.617   971.7
  25.656   971.4  54.035  971.43  63.058  970.56  72.014  970.69  78.018  971.48
 115.748  971.52 129.921  970.85 193.471  971.48 212.238  974.54 233.563  975.76
 239.239  975.94 243.602  975.01 257.119   974.8  271.49  975.12 275.459   975.9
  282.71  974.95 314.075  974.58 320.276  972.33 324.738  970.04 340.486  978.11
#Mann= 6 ,-1 , 0
 -77.657      .1       0 -13.156    .045       0   8.727      .1       0
  25.656     .05       0 233.563     .03       0 324.738      .1       0
#XS Ineff= 2 , 0
       0                     240       0
Permanent Ineff=
       F       F
Bank Sta=-13.156,8.727
XS Rating Curve= 0 ,0
Exp/Cntr=0.5,0.3

Type RM Length L Ch R = 1 ,10200   ,143.75,158,169.979
BEGIN DESCRIPTION:
US of Grafton Road
END DESCRIPTION:
XS GIS Cut Line= 5
575463.4800081354370014.58650487575474.5137682714369991.85452059
575487.0227604264369973.62443237575492.2653204914369960.82283221
575555.7673532754369922.50947173
#Sta/Elev= 30
 -95.571  987.52  -90.19  985.89 -59.744  980.95 -56.102  977.92 -47.474  973.72
 -11.844   972.2 -10.597  971.87      -8 969.471      -5   966.7       5   966.7
       9   969.3  10.892  970.19  17.651  971.13  25.098  971.57  61.811  970.85
 119.259  971.26  131.43   970.6 148.064  971.49 187.402  971.04 202.854  971.52
 212.762  973.64 236.286  975.76 254.823  974.76  269.16  974.85 281.234   975.7
 294.521   974.6  316.24  974.13 322.867     973 329.692   970.1 348.556  980.11
#Mann= 6 ,-1 , 0
 -95.571      .1       0      -8    .045       0       9      .1       0
  17.651     .05       0 236.286     .03       0 329.692      .1       0
#XS Ineff= 2 , 0
       0                     240       0
Permanent Ineff=
       F       F
Bank Sta=-8,9
XS Rating Curve= 0 ,0
Exp/Cntr=0.5,0.3

Type RM Length L Ch R = 2 ,10176   ,,,
BEGIN DESCRIPTION:
Grafton Road (estimated from field recon - US and DS openings are different culvert sizes, the more conservative DS side was modeled)
END DESCRIPTION:
Bridge Culvert--1,0,-1,-1, 0
Deck Dist Width WeirC Skew NumUp NumDn MinLoCord MaxHiCord MaxSubmerge Is_Ogee
12,125,2.6,0, 60, 60, , , 0.98, 0, 0,0,,
-243.143-229.167-221.818-204.888-197.802-189.731-177.428-170.636-157.087-154.265
-129.921-109.547 -89.108  -86.22 -82.185 -68.668 -61.942 -59.186 -52.297 -41.634
 -32.021  -20.01     -20      20   20.01   28.51  37.861  46.358  57.808  60.925
   68.57  75.361  79.396 103.248 131.562 142.618 158.858 196.096 199.049  202.69
 206.266 208.957 221.358 229.134 238.353 248.917 252.887 258.005 266.076 276.312
 280.643 284.219 312.402 316.043 325.525 329.757 337.795 340.814 344.521 351.542
   992.5   991.2   989.9  988.73  987.36  986.81  984.93  984.46  982.54  982.61
  979.53  978.13  975.66  975.96  975.35  974.43  974.42  973.95  974.11  972.91
  972.93  972.25  974.25  973.86  971.69  971.23  971.72  971.13  971.15  971.49
  971.05  971.41  970.92  970.88  971.56  971.05   971.4  971.49   971.2  971.64
  971.47  972.27   974.5  975.23  975.44  974.34   974.8  974.44  974.57   975.6
  975.39  974.37  973.81  973.31  969.89  971.73  977.04  978.47  980.89  983.65
                                                                                
                                                                                
                                                                                
                                                                                
                                                                                
                                                                                
-243.143-229.167-221.818-204.888-197.802-189.731-177.428-170.636-157.087-154.265
-129.921-109.547 -89.108  -86.22 -82.185 -68.668 -61.942 -59.186 -52.297 -41.634
 -32.021  -20.01     -20      20   20.01   28.51  37.861  46.358  57.808  60.925
   68.57  75.361  79.396 103.248 131.562 142.618 158.858 196.096 199.049  202.69
 206.266 208.957 221.358 229.134 238.353 248.917 252.887 258.005 266.076 276.312
 280.643 284.219 312.402 316.043 325.525 329.757 337.795 340.814 344.521 351.542
   992.5   991.2   989.9  988.73  987.36  986.81  984.93  984.46  982.54  982.61
  979.53  978.13  975.66  975.96  975.35  974.43  974.42  973.95  974.11  972.91
  972.93  972.25  974.25  973.86  971.69  971.23  971.72  971.13  971.15  971.49
  971.05  971.41  970.92  970.88  971.56  971.05   971.4  971.49   971.2  971.64
  971.47  972.27   974.5  975.23  975.44  974.34   974.8  974.44  974.57   975.6
  975.39  974.37  973.81  973.31  969.89  971.73  977.04  978.47  980.89  983.65
                                                                                
                                                                                
                                                                                
                                                                                
                                                                                
                                                                                
BR Coef=-1 , 0 , 0 ,, 0 ,,,0.8,-1,,0,
WSPro=,,,, 1 ,,,, 0 ,,,, 0 ,,,,-1 ,-1 ,-1 , 0 , 0 , 0 , 0 , 0
Multiple Barrel Culv=1,3.5,,125,0.025,0.5,1,2,1,966.7,964.4, 3,Culvert #1  , 0 ,12
      -4      -4       0       0       4       4
Culvert Bottom n=0.025
BC Design=,, 0 ,, 0 ,,,,,,
BC Use User HTab Curves=0
BC User HTab FreeFlow(D)= 0

Type RM Length L Ch R = 1 ,10042   ,16.66,19,21.27
BEGIN DESCRIPTION:
DS of Grafton Road
END DESCRIPTION:
XS GIS Cut Line= 3
575453.1076640074370067.07916152 575490.573680474370035.54150513
575593.6539937444369974.36814437
#Sta/Elev= 30
-221.588  993.31-206.726  991.25-184.285  988.63 -178.74  986.81-166.896  982.19
-157.612  976.67-153.675  975.63-144.521  970.83  -114.6  969.05 -34.908  968.89
 -13.484  968.13  -10.63  967.51      -5  964.34   6.135  964.22  13.484  967.54
  17.651  970.11  20.833  970.26 157.054  970.92 182.415  972.61 194.816  972.52
 201.345  972.52 205.512  971.48 229.265  972.04 236.483  973.13 247.441  971.97
 289.337  971.36 295.374  971.69 299.803   973.9 304.692  977.68 332.349  988.99
#Mann= 7 ,-1 , 0
-221.588      .1       0-206.726     .12       0 -34.908     .05       0
 -13.484    .045       0  13.484     .05       0 194.816     .03       0
 299.803      .1       0
#XS Ineff= 2 , 0
       0                     185       0
Permanent Ineff=
       F       F
#Block Obstruct= 1 ,-1
  95.308 149.934     980
Bank Sta=-13.484,13.484
XS Rating Curve= 0 ,0
Exp/Cntr=0.5,0.3

Type RM Length L Ch R = 1 ,10023   ,29.93,28,26.09
XS GIS Cut Line= 3
 575454.165320024370068.13681753575492.0550084884370039.13814517
575598.1010257994369988.12681654
#Sta/Elev= 30
-214.009  992.64-212.467  992.38-206.004  990.95-179.199  988.05-166.765   983.4
-152.625  976.82-140.026  974.09-134.154  969.99 -94.094  968.72 -32.841  968.81
 -13.517   968.4   -7.71  967.33  -4.495  965.33  -3.806     964    5.17     964
  13.517  968.57  16.601  970.18  21.719  970.53 101.083  970.32 144.652  971.41
 157.054  970.49 202.001  972.23 210.466  971.31 223.786  971.44 245.538  972.85
 251.804  971.85 286.877  971.16  293.34   973.5 308.366  979.89 328.576  985.66
#Mann= 7 ,-1 , 0
-214.009      .1       0-212.467     .12       0 -32.841     .05       0
 -13.517    .045       0  13.517     .05       0 202.001     .03       0
  293.34      .1       0
#XS Ineff= 2 , 0
       0                     200       0
Permanent Ineff=
       F       F
#Block Obstruct= 1 ,-1
 105.151 161.089     980
Bank Sta=-13.517,13.517
XS Rating Curve= 0 ,0
Exp/Cntr=0.5,0.3

Type RM Length L Ch R = 1 ,9995    ,29,29,29
BEGIN DESCRIPTION:
US of State Route 310
END DESCRIPTION:
XS GIS Cut Line= 2
575426.1420076734370084.72403374575597.5127617914369993.10115261
#Sta/Elev= 30
-312.467 1013.13-285.367 1010.19-268.865 1000.25-224.278  996.58-212.336  993.49
-198.491  990.61-190.223   990.7-176.444  987.59-152.067  977.99-141.273  974.98
-125.197  973.12-114.436   969.8  -98.72  968.75 -28.248   968.9 -22.474  968.84
 -10.696  968.93    -5.5 965.822   -4.92   963.5    4.92   963.5       8 965.822
  15.157  969.71  25.361  969.96 120.538  970.09 204.888  972.25 225.492  971.17
  248.95  972.81 289.665  971.02 293.274   972.3 317.552  982.68 325.066  983.54
#Mann= 9 ,-1 , 0
-312.467      .1       0-212.336     .12       0 -28.248     .05       0
 -22.474     .09       0    -5.5     .04       0       8     .09       0
  25.361     .05       0 204.888     .03       0 293.274      .1       0
#XS Ineff= 2 , 0
       0                     160       0
Permanent Ineff=
       F       F
Bank Sta=-5.5,8
XS Rating Curve= 0 ,0
Exp/Cntr=0.5,0.3

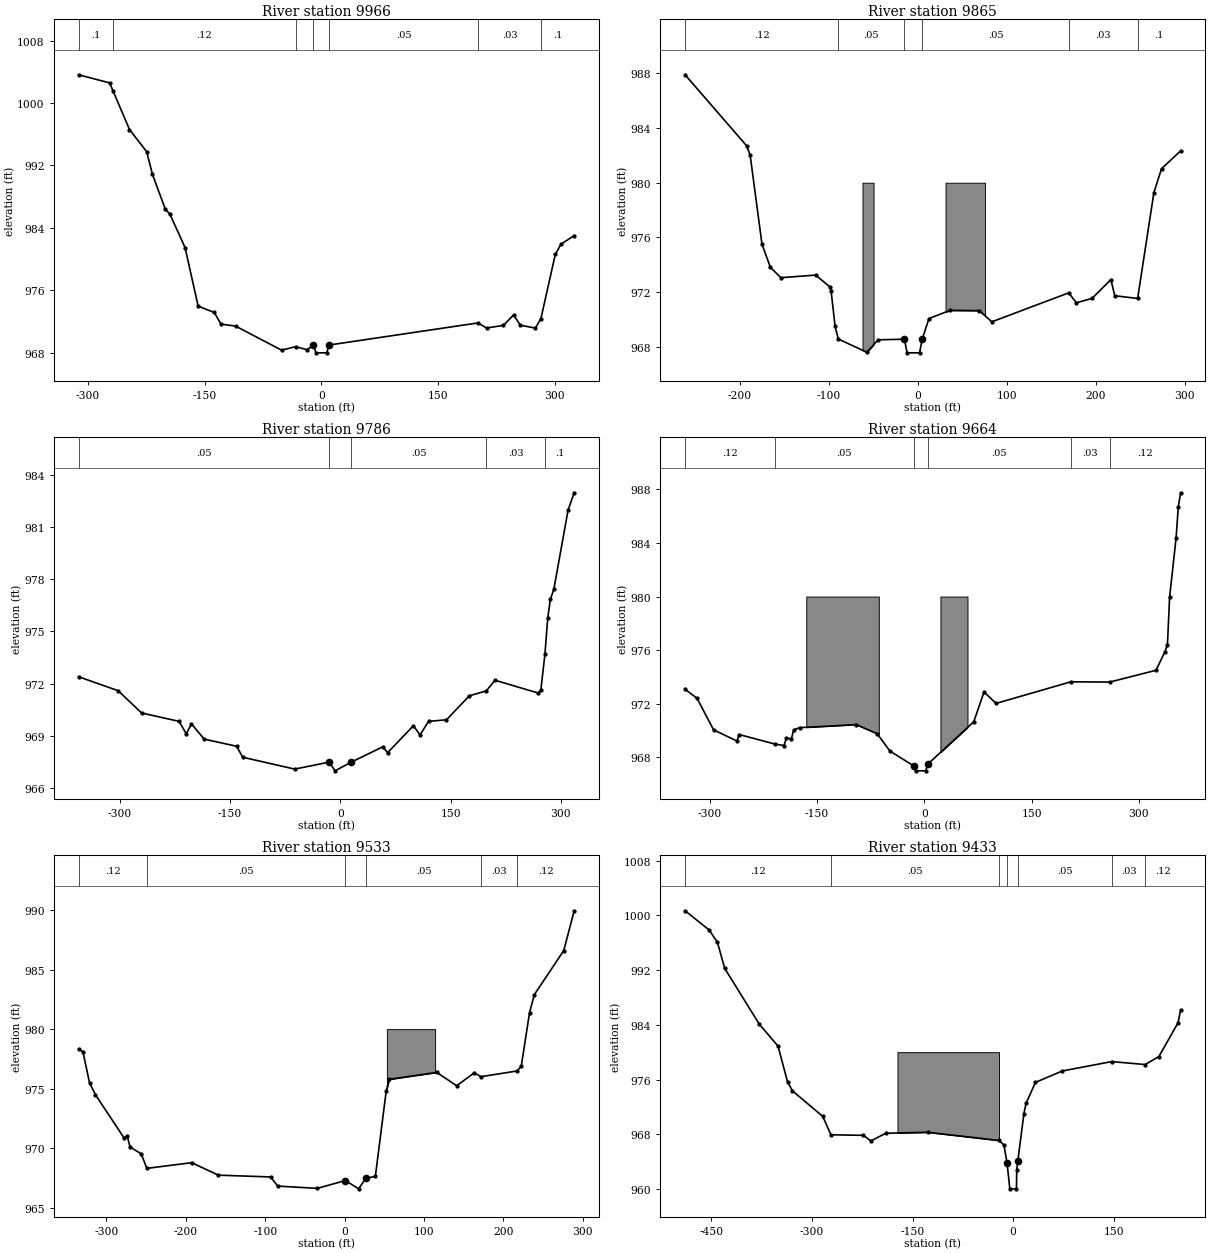
Type RM Length L Ch R = 1 ,9966    ,112.96,101,89.39
BEGIN DESCRIPTION:
Overland XS
END DESCRIPTION:
XS GIS Cut Line= 2
575432.0825597474370093.01764184575601.8409218454369998.61498467
#Sta/Elev= 30
-312.041 1003.62-272.211 1002.58-267.552  1001.5-246.654  996.61-224.541  993.77
-217.159  990.88-200.558  986.39-194.685  985.77-175.197  981.49-158.333  973.98
-137.566  973.17 -128.97  971.68-110.269  971.43 -51.017  968.34 -33.005  968.79
 -18.241   968.4     -10     969      -7     968       7     968      10     969
 201.444  971.83 212.566  971.18 234.285  971.52  247.31  972.85 256.135  971.53
 275.328  971.18 282.448  972.38 300.919   980.6 308.202  981.91  325.23  983.02
#Mann= 7 ,-1 , 0
-312.041      .1       0-267.552     .12       0 -33.005     .05       0
     -10     .04       0      10     .05       0 201.444     .03       0
 282.448      .1       0
#XS Ineff= 2 , 0
       0                  201.44       0
Permanent Ineff=
       F       F
Bank Sta=-10,10
XS Rating Curve= 0 ,0
Exp/Cntr=0.3,0.1

Type RM Length L Ch R = 1 ,9865    ,79,79,76.54
BEGIN DESCRIPTION:
Overland XS
END DESCRIPTION:
XS GIS Cut Line= 4
575475.6872482864370107.41334602 575534.318577014370072.69967359
575571.7845934734370020.62764095575603.9562338714370001.36732871
#Sta/Elev= 30
-261.549   987.9-192.487  982.71-188.419  982.02-175.164  975.52-165.781  973.82
-153.937  973.05-114.764  973.24 -99.213   972.4 -97.441  972.09 -92.913  969.48
 -89.304  968.56 -57.185  967.59 -44.685   968.5     -15  968.55     -12  967.55
       2  967.55       5  968.55  12.598  970.06  36.385  970.66  69.094  970.64
  83.268  969.82 169.685  971.94 178.314  971.21 195.997  971.54 217.126  972.91
 221.424  971.73 247.146  971.53 265.453  979.28 274.049  981.03 295.505  982.33
#Mann= 6 ,-1 , 0
-261.549     .12       0 -89.304     .05       0     -15     .04       0
       5     .05       0 169.685     .03       0 247.146      .1       0
#XS Ineff= 2 , 0
       0                   75.66       0
Permanent Ineff=
       F       F
#Block Obstruct= 2 ,-1
 -62.139 -49.705     980  31.234  75.656     980
Bank Sta=-15,5
XS Rating Curve= 0 ,0
Exp/Cntr=0.3,0.1

Type RM Length L Ch R = 1 ,9786    ,120.9,122,122.07
BEGIN DESCRIPTION:
Overland XS on State Route 310
END DESCRIPTION:
XS GIS Cut Line= 3
575498.9709205734370179.58998691 575587.658577674370019.14631293
575605.8612338944370006.65865677
#Sta/Elev= 30
-355.741   972.4-302.001   971.6-270.112  970.32 -219.16  969.84-209.285  969.12
-202.395   969.7-184.941  968.82-140.846  968.41-132.612  967.78 -61.909   967.1
     -15   967.5      -7     967      15   967.5  57.907  968.38  64.403  968.04
  99.541  969.59 108.465  969.06 120.177  969.84 144.488  969.93 175.689  971.31
 198.655  971.59 210.433   972.2 268.799  971.47 272.769  971.62 278.445  973.72
 282.152  975.76 285.794  976.84 290.486  977.42 309.875  981.97 318.143  982.96
#Mann= 5 ,-1 , 0
-355.741     .05       0     -15     .04       0      15     .05       0
 198.655     .03       0 278.445      .1       0
#XS Ineff= 2 , 0
       0    -115                       0
Permanent Ineff=
       F       F
Bank Sta=-15,15
XS Rating Curve= 0 ,0
Exp/Cntr=0.3,0.1

Type RM Length L Ch R = 1 ,9664    ,129.95,131,132.39
BEGIN DESCRIPTION:
Overland XS
END DESCRIPTION:
XS GIS Cut Line= 2
575526.9119369194370196.73498712575633.1682662324370014.27865687
#Sta/Elev= 30
-334.318  973.08-317.618  972.41-294.554  970.06-261.745  969.22-258.825  969.71
 -208.99     969-196.096  968.89-192.684  969.44-185.761  969.39-182.415  970.06
-174.213  970.22 -95.112  970.45 -65.879  969.77   -47.9  968.47     -15 967.378
     -12     967       2     967       5 967.506  69.193  970.66   83.53  972.88
 100.459  972.03 204.856  973.64 259.219  973.62 323.983   974.5 336.155  975.85
 339.961  976.41 342.979  979.96 352.034  984.36 355.151  986.71 358.399  987.74
#Mann= 6 ,-1 , 0
-334.318     .12       0 -208.99     .05       0     -15     .04       0
       5     .05       0 204.856     .03       0 259.219     .12       0
#XS Ineff= 2 , 0
       0 -164.93                       0
Permanent Ineff=
       F       F
#Block Obstruct= 2 ,-1
  22.605  60.433     980-164.928 -63.517     980
Bank Sta=-15,5
XS Rating Curve= 0 ,0
Exp/Cntr=0.3,0.1

Type RM Length L Ch R = 1 ,9533    ,98.45,100,101.02
BEGIN DESCRIPTION:
Overland XS
END DESCRIPTION:
XS GIS Cut Line= 2
575559.7175613244370208.80201927575663.011234601 4370048.9923293
#Sta/Elev= 30
-335.007  978.31-329.626  978.11 -321.26  975.48 -313.78  974.48-277.461  970.82
-273.819  971.03-270.243  970.09-256.037  969.51-249.114  968.29-192.552  968.77
-159.022  967.72 -93.143  967.57 -84.154   966.8 -34.285  966.61   1.181  967.27
  17.684  966.57  26.903  967.47  38.812  967.61  52.493  974.79  56.398  975.78
 116.109  976.36 141.273  975.24  163.55  976.33  171.85     976 217.487  976.48
 222.671  976.89 233.071  981.38 239.042  982.89 276.214  986.61 289.304  989.95
#Mann= 6 ,-1 , 0
-335.007     .12       0-249.114     .05       0   1.181     .04       0
  26.903     .05       0  171.85     .03       0 217.487     .12       0
#XS Ineff= 2 , 0
       0     -90                       0
Permanent Ineff=
       F       F
#Block Obstruct= 1 ,-1
  53.346 114.108     980
Bank Sta=1.181,26.903
XS Rating Curve= 0 ,0
Exp/Cntr=0.3,0.1

Type RM Length L Ch R = 1 ,9433    ,243.49,243,242.51
BEGIN DESCRIPTION:
DS of State Route 310
END DESCRIPTION:
XS GIS Cut Line= 2
575557.5870092984370255.54005185575686.9989948974370071.31283357
#Sta/Elev= 30
-488.976 1000.69-453.248  997.89-440.748  996.08-429.954  992.26-378.478  984.11
-350.427  980.88-336.286  975.65-329.035  974.35-283.727  970.59-271.621  967.91
-223.294  967.83-212.041  967.01-189.961  968.13-127.493  968.28  -21.13  967.08
 -13.714  966.41   -8.99  963.71   -4.92     960    4.92     960   5.381   962.8
   6.955  964.06  16.076  971.02  19.193   972.5  33.268  975.58   73.36  977.25
  146.85  978.62 196.883  978.19 217.257  979.36 245.768  984.29 249.672  986.18
#Mann= 7 ,-1 , 0
-488.976     .12       0-271.621     .05       0  -21.13     .09       0
   -8.99    .045       0   6.955     .05       0  146.85     .03       0
 196.883     .12       0
#XS Ineff= 2 , 0
       0  -21.13                       0
Permanent Ineff=
       F       F
#Block Obstruct= 1 ,-1
-172.408 -21.129     980
Bank Sta=-8.99,6.955
XS Rating Curve= 0 ,0
Exp/Cntr=0.5,0.3

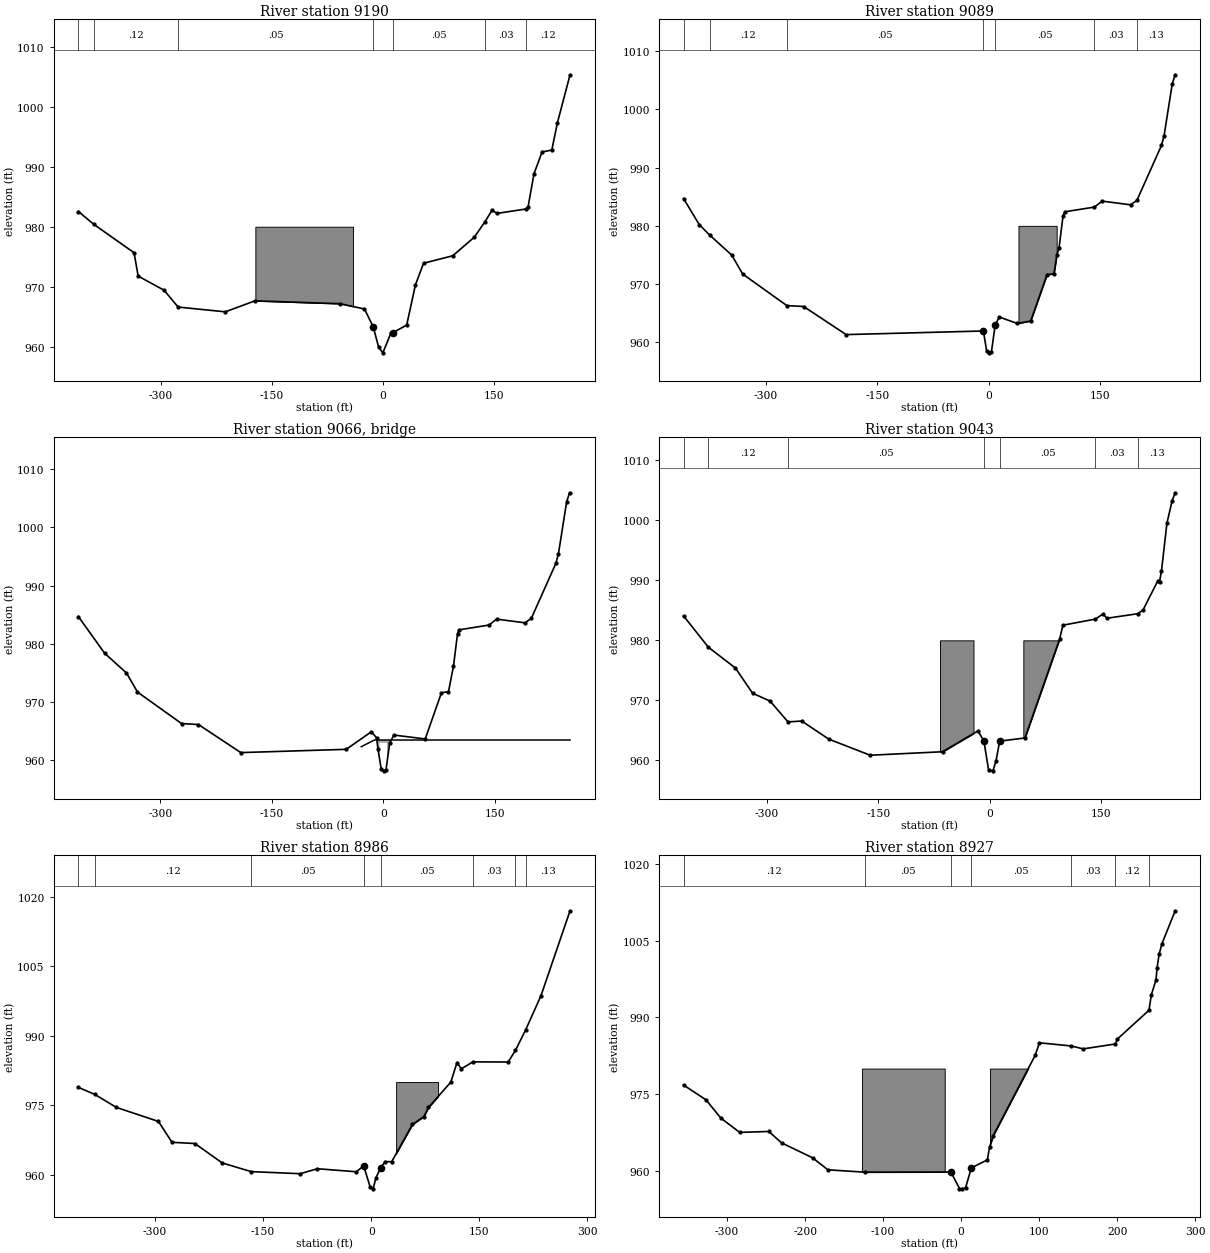
Type RM Length L Ch R = 1 ,9190    ,100.46,101,101.54
XS GIS Cut Line= 2
575635.8535542654370276.69012411575749.0958996654370108.94344204
#Sta/Elev= 30
-411.352  982.53-390.518  980.39 -336.22  975.67-330.676  971.78-295.604  969.42
-276.673  966.62-212.959  965.83  -172.9  967.66 -57.612  967.18 -24.967   966.3
 -13.156  963.32  -5.906  959.97   -.164     959  10.696  962.27  13.156  962.33
  32.054  963.63  43.799  970.29  54.823  973.92  94.193  975.16 123.261  978.24
 137.598  980.79  147.31  982.75 154.232  982.22 193.504  982.96 195.866  983.21
  203.97  988.81 214.928  992.45 228.051  992.77 235.696  997.34  252.69  1005.3
#Mann= 7 ,-1 , 0
-411.352     .11       0-390.518     .12       0-276.673     .05       0
 -13.156    .045       0  13.156     .05       0 137.598     .03       0
 193.504     .12       0
#XS Ineff= 2 , 0
       0  -40.42                       0
Permanent Ineff=
       F       F
#Block Obstruct= 1 ,-1
-172.375  -40.42     980
Bank Sta=-13.156,13.156
XS Rating Curve= 0 ,0
Exp/Cntr=0.5,0.3

Type RM Length L Ch R = 1 ,9089    ,46,46,46
BEGIN DESCRIPTION:
US of Private road
END DESCRIPTION:
XS GIS Cut Line= 2
575658.8385225494370293.22857231575774.9246519844370128.52684228
#Sta/Elev= 30
-410.367  984.67-389.337  980.22 -375.23  978.41-345.702     975-330.873  971.73
-271.522  966.32-248.885  966.16-191.798  961.34  -7.185  961.96  -2.887   958.6
    .525  958.21   3.642  958.39   8.727     963  14.206  964.35  38.484  963.25
  56.463  963.68  78.346  971.62  87.762  971.78  91.568  974.99  94.488  976.16
  99.967  981.75 102.231  982.41 142.192  983.22 152.592  984.24 190.715  983.61
 199.278  984.37 232.349  993.81 235.794  995.45  246.85 1004.39 250.755 1005.92
#Mann= 7 ,-1 , 0
-410.367     .11       0 -375.23     .12       0-271.522     .05       0
  -7.185    .045       0   8.727     .05       0 142.192     .03       0
 199.278     .13       0
#XS Ineff= 2 , 0
       0     -70                       0
Permanent Ineff=
       F       F
#Block Obstruct= 1 ,-1
      40  91.371     980
Bank Sta=-7.185,8.727
XS Rating Curve= 0 ,0
Exp/Cntr=0.5,0.3

Type RM Length L Ch R = 3 ,9066    ,,,
BEGIN DESCRIPTION:
Private road (estimated from effective HEC2 and field recon)
END DESCRIPTION:
Bridge Culvert--1,0,-1,-1, 0
Deck Dist Width WeirC Skew NumUp NumDn MinLoCord MaxHiCord MaxSubmerge Is_Ogee
15,13.2,2.8,0, 7, 7, , , 0.98, 0, 0,0,,
  -29.66     -12   -5.01      -5       5    5.01 251.411
  962.35   963.5   963.5   963.5   963.5   963.5   963.5
                             963     963
  -29.66     -12   -5.01      -5       5    5.01 251.411
  962.35   963.5   963.5   963.5   963.5   963.5   963.5
                             963     963
BR Coef=-1 , 0 , 0 ,, 0 ,,,0.8,0,,0,
WSPro=,,,, 1 ,,,, 0 ,,,, 0 ,,,,-1 ,-1 ,-1 , 0 , 0 , 0 , 0 , 0
BR U #Sta/Elev= 30
-410.367  984.67 -375.23  978.41-345.702     975-330.873  971.73-271.522  966.32
-248.885  966.16-191.798  961.34 -49.902   961.9 -15.978  964.92  -8.924  963.84
  -7.185  961.96  -2.887   958.6    .525  958.21   3.642  958.39   8.727     963
  14.206  964.35  56.463  963.68  78.346  971.62  87.762  971.78  94.488  976.16
  99.967  981.75 102.231  982.41 142.192  983.22 152.592  984.24 190.715  983.61
 199.278  984.37 232.349  993.81 235.794  995.45  246.85 1004.39 250.755 1005.92
BR U #Mann= 7
-410.367     .11 -375.23     .12-271.522     .05  -7.185    .045   8.727     .05
 142.192     .03 199.278     .13
BC Design=,, 0 ,, 0 ,,,,,,
BC Use User HTab Curves=0
BC User HTab FreeFlow(D)= 0

Type RM Length L Ch R = 1 ,9043    ,57,57,117.85
BEGIN DESCRIPTION:
DS of Private road
END DESCRIPTION:
XS GIS Cut Line= 2
575670.2807146914370301.29358041575786.3698921254370136.59185038
#Sta/Elev= 30
-411.877  984.06-378.576  978.86-342.159  975.39-319.062  971.19-295.538  969.89
-271.457  966.42-253.018  966.56-216.568  963.55-161.024  960.87 -63.583  961.45
 -15.978  964.92      -8 963.228   -1.65  958.37   4.199  958.27   8.169  959.88
  13.255  963.22  47.146  963.74  93.832  980.23  98.228  982.52 141.896  983.54
 152.067  984.39 157.448  983.68 198.885  984.43 205.873  985.03  225.82   989.9
 228.215  989.78 230.807  991.57 238.123  999.51 245.144 1003.27 249.213 1004.57
#Mann= 7 ,-1 , 0
-411.877     .11       0-378.576     .12       0-271.457     .05       0
      -8     .04       0  13.255     .05       0 141.896     .03       0
 198.885     .13       0
#XS Ineff= 2 , 0
       0    -100                       0
Permanent Ineff=
       F       F
#Block Obstruct= 2 ,-1
     -67     -22     980      45  92.552     980
Bank Sta=-8,13.255
XS Rating Curve= 0 ,0
Exp/Cntr=0.5,0.3

Type RM Length L Ch R = 1 ,8986    ,59.2,59,58.8
XS GIS Cut Line= 2
575685.5176668794370308.80385251575805.7460283654370139.04549041
#Sta/Elev= 30
 -406.43  978.84-383.629  977.32-353.773  974.52-295.308  971.49-276.542  966.98
-244.718  966.72-206.791  962.52-166.601  960.65 -98.622   960.2 -74.705  961.27
 -20.604  960.62 -10.433   961.9  -1.312  957.26   2.592  956.93   6.759  959.37
  13.156  961.47  19.357  962.82  28.379  962.78  57.283  970.85  73.163  972.54
  79.528  974.51 110.466  979.97 119.127  984.21 125.098  982.86 141.207  984.36
 190.125  984.33 200.295  986.85 214.633  991.34 235.663  998.64  276.05    1017
#Mann= 8 ,-1 , 0
 -406.43     .11       0-383.629     .12       0-166.601     .05       0
 -10.433     .04       0  13.156     .05       0 141.207     .03       0
 200.295     .12       0 214.633     .13       0
#XS Ineff= 2 , 0
       0     -65                       0
Permanent Ineff=
       F       F
#Block Obstruct= 1 ,-1
  34.613  92.848     980
Bank Sta=-10.433,13.156
XS Rating Curve= 0 ,0
Exp/Cntr=0.5,0.3

Type RM Length L Ch R = 1 ,8927    ,78.32,78,77.68
XS GIS Cut Line= 2
575710.0723551824370306.89885248575819.5047005354370148.99416253
#Sta/Elev= 30
 -355.84  976.77-327.034  973.89-308.169  970.33-283.891  967.52-246.555   967.7
-230.217  965.47-190.322  962.54-170.801   960.2-123.589  959.74 -13.123  959.77
  -2.067  956.54   1.083  956.48   5.643  956.65  13.123  960.58  33.694  962.14
   36.45  964.64  41.175  966.88  95.046  982.62 100.394  985.04 141.306  984.42
 156.529  983.85 197.802  984.81 200.131  985.74 240.879  991.41 243.898  994.42
 249.869  997.33  251.28  999.72 253.871 1002.37 257.448 1004.39 274.475 1010.86
#Mann= 7 ,-1 , 0
 -355.84     .12       0-123.589     .05       0 -13.123     .04       0
  13.123     .05       0 141.306     .03       0 197.802     .12       0
 240.879     .13       0
#XS Ineff= 2 , 0
       0     -21                       0
Permanent Ineff=
       F       F
#Block Obstruct= 2 ,-1
    -127     -21     980      37      94     980
Bank Sta=-13.123,13.123
XS Rating Curve= 0 ,0
Exp/Cntr=0.3,0.1

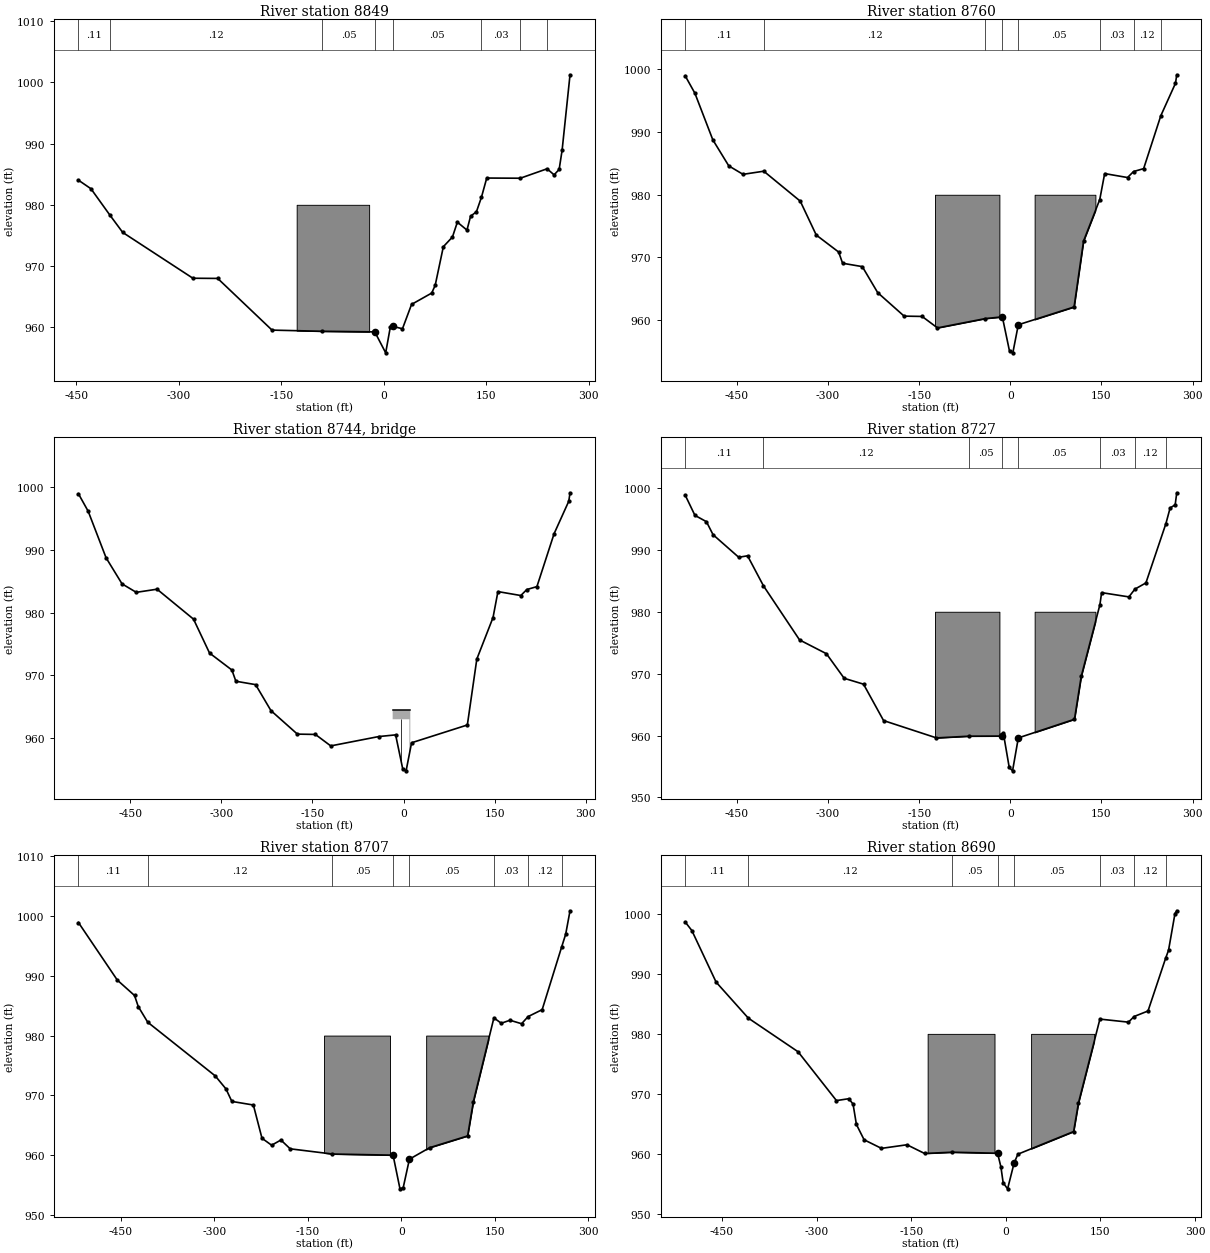
Type RM Length L Ch R = 1 ,8849    ,88.9,89,89.1
XS GIS Cut Line= 2
575715.3636832484370343.93814894575838.131028765 4370162.3291627
#Sta/Elev= 30
-446.785  984.02-428.445  982.62-400.656   978.3-381.988  975.49-279.331  968.01
-243.045  967.98 -163.55  959.54 -89.862  959.35 -13.222  959.25   2.723  955.83
   9.514  960.05  13.222  960.16  27.264  959.76  40.584  963.74  70.046  965.59
  75.131  966.85  87.073  973.16 100.427  974.75 107.579  977.17 121.621  975.87
 126.936  978.14 135.466  978.86 142.815  981.23 150.558  984.37 199.639  984.34
 238.845  985.88 249.114  984.89 256.496  985.78 260.827  988.91 272.408 1001.23
#Mann= 8 ,-1 , 0
-446.785     .11       0-400.656     .12       0 -89.862     .05       0
 -13.222     .04       0  13.222     .05       0 142.815     .03       0
 199.639     .12       0 238.845     .13       0
#XS Ineff= 2 , 0
       0   -21.5                       0
Permanent Ineff=
       F       F
#Block Obstruct= 1 ,-1
  -127.5   -21.5     980
Bank Sta=-13.222,13.222
XS Rating Curve= 0 ,0
Exp/Cntr=0.5,0.3

Type RM Length L Ch R = 1 ,8760    ,32.809,33,32.808
BEGIN DESCRIPTION:
DS of Loading dock bridge #2
END DESCRIPTION:
XS GIS Cut Line= 2
575721.3560513224370381.95280541575860.2625570394370178.22448289
#Sta/Elev= 30
-535.105  998.99-519.062   996.2  -489.6  988.77 -463.32  984.61-439.895  983.26
-405.741  983.76-345.702  978.98-319.357  973.57-282.546  970.86-276.017  969.07
 -243.57  968.53-218.274  964.38 -174.77  960.63-145.144  960.58-119.915  958.75
 -40.978  960.24 -13.123  960.51  -1.312  955.03   4.134  954.77  13.123  959.25
 104.921  962.09 120.505  972.61 147.178  979.24 155.249  983.38 192.881  982.75
 202.822  983.71  219.39  984.17 247.671  992.62 271.818   997.8 273.885  999.15
#Mann= 8 ,-1 , 0
-535.105     .11       0-405.741     .12       0 -40.978     .05       0
 -13.123     .04       0  13.123     .05       0 147.178     .03       0
 202.822     .12       0 247.671     .13       0
#XS Ineff= 2 , 0
       0     -18                       0
Permanent Ineff=
       F       F
#Block Obstruct= 2 ,-1
    -124     -18     980      40     140     980
Bank Sta=-13.123,13.123
XS Rating Curve= 0 ,0
Exp/Cntr=0.5,0.3

Type RM Length L Ch R = 3 ,8744    ,,,
BEGIN DESCRIPTION:
Loading dock bridge #2 (estimated from field recon)
END DESCRIPTION:
Bridge Culvert--1,0,-1,-1, 0
Deck Dist Width WeirC Skew NumUp NumDn MinLoCord MaxHiCord MaxSubmerge Is_Ogee
7.5,12.08,2.6,0, 4, 4, , , 0.98, 0, 0,0,,
     -18     9.5    9.51      11
   964.5   964.5   964.5   964.5
     963     963
     -18     9.5    9.51      11
   964.5   964.5   964.5   964.5
     963     963
Pier Skew, UpSta & Num, DnSta & Num=  ,-4.25, 2 ,-4.25, 2 , 0 , 0 , 0 ,,
      .5      .5
     955     963
      .5      .5
     955     963
BR Coef=-1 , 1 , 1 ,1.25, 0 ,,,0.8,0,1.2,0,
WSPro=,,,, 1 ,,,, 0 ,,,, 0 ,,,,-1 ,-1 ,-1 , 0 , 0 , 0 , 0 , 0
BC Design=,, 0 ,, 0 ,,,,,,
BC Use User HTab Curves=0
BC User HTab FreeFlow(D)= 0

Type RM Length L Ch R = 1 ,8727    ,20.2,20,19.8
BEGIN DESCRIPTION:
DS of Loading dock bridge #2
END DESCRIPTION:
XS GIS Cut Line= 2
575729.6161314244370387.58550948575868.5226371414370183.85718696
#Sta/Elev= 30
-535.138  998.85-519.062  995.57-500.131  994.55-489.239  992.45-446.982   988.8
-432.448  989.04-406.234  984.18-346.883  975.45-302.657  973.22-273.458  969.25
-241.601   968.3-208.629  962.42-121.555  959.62  -67.52   959.9 -13.123  959.92
 -11.516  960.39  -1.837  954.85   3.642   954.3  13.123  959.62 105.512  962.63
 116.699  969.57 147.375  981.13 150.197  983.09 195.079   982.4 204.921  983.65
 223.097  984.66 256.037  994.25 262.927  996.77  271.26  997.28 273.852  999.22
#Mann= 8 ,-1 , 0
-535.138     .11       0-406.234     .12       0  -67.52     .05       0
 -13.123     .04       0  13.123     .05       0 147.375     .03       0
 204.921     .12       0 256.037     .13       0
#XS Ineff= 2 , 0
       0     -18                       0
Permanent Ineff=
       F       F
#Block Obstruct= 2 ,-1
    -124     -18     980      40     140     980
Bank Sta=-13.123,13.123
XS Rating Curve= 0 ,0
Exp/Cntr=0.5,0.3

Type RM Length L Ch R = 1 ,8707    ,17.39,17,16.61
XS GIS Cut Line= 2
575738.6473555364370387.54283748575872.6313411914370187.72814701
#Sta/Elev= 30
-518.307  998.87-455.873  989.26-428.215  986.69-422.244  984.84-407.054  982.23
-298.655  973.27 -281.43   971.1-271.982  969.01-237.434  968.41-223.589  962.86
-208.104   961.7-193.209  962.57-178.346   961.1-110.433  960.23 -13.123  960.04
  -2.034  954.42   3.117   954.6  13.123  959.37  45.636  961.29 106.562  963.25
 115.814  968.98 148.753  982.95  160.63  982.06 174.541  982.56 193.241  981.98
 203.675  983.17  226.28  984.33 257.644  994.82 264.009  996.91 270.997 1000.83
#Mann= 8 ,-1 , 0
-518.307     .11       0-407.054     .12       0-110.433     .05       0
 -13.123     .04       0  13.123     .05       0 148.753     .03       0
 203.675     .12       0 257.644     .13       0
#XS Ineff= 2 , 0
       0     -18                       0
Permanent Ineff=
       F       F
#Block Obstruct= 2 ,-1
    -124     -18     980      40     140     980
Bank Sta=-13.123,13.123
XS Rating Curve= 0 ,0
Exp/Cntr=0.5,0.3

Type RM Length L Ch R = 1 ,8690    ,32.821,33,32.821
BEGIN DESCRIPTION:
US of Loading dock bridge #1
END DESCRIPTION:
XS GIS Cut Line= 2
575746.428899632 4370389.1887575575875.8104052314370189.95928304
#Sta/Elev= 30
-508.432  998.64-497.835  997.21-459.383  988.62-408.301  982.62-329.429  977.02
-268.602  968.89-249.049   969.2-242.257  968.31-236.942  964.91-224.738  962.36
-197.211  960.93-156.791  961.53-128.839  960.08 -85.269  960.29 -13.123  960.12
  -7.874  957.85  -4.265  955.19   2.756  954.19  13.123  958.51  19.062  959.96
 107.415  963.73 115.157  968.52 149.114  982.46  194.39  981.95 203.281  982.89
 225.361  983.81 253.281  992.59 257.907  993.92  268.11 1000.04 270.932  1000.5
#Mann= 8 ,-1 , 0
-508.432     .11       0-408.301     .12       0 -85.269     .05       0
 -13.123     .04       0  13.123     .05       0 149.114     .03       0
 203.281     .12       0 253.281     .13       0
#XS Ineff= 2 , 0
       0     -18                       0
Permanent Ineff=
       F       F
#Block Obstruct= 2 ,-1
    -124     -18     980      40     140     980
Bank Sta=-13.123,13.123
XS Rating Curve= 0 ,0
Exp/Cntr=0.5,0.3