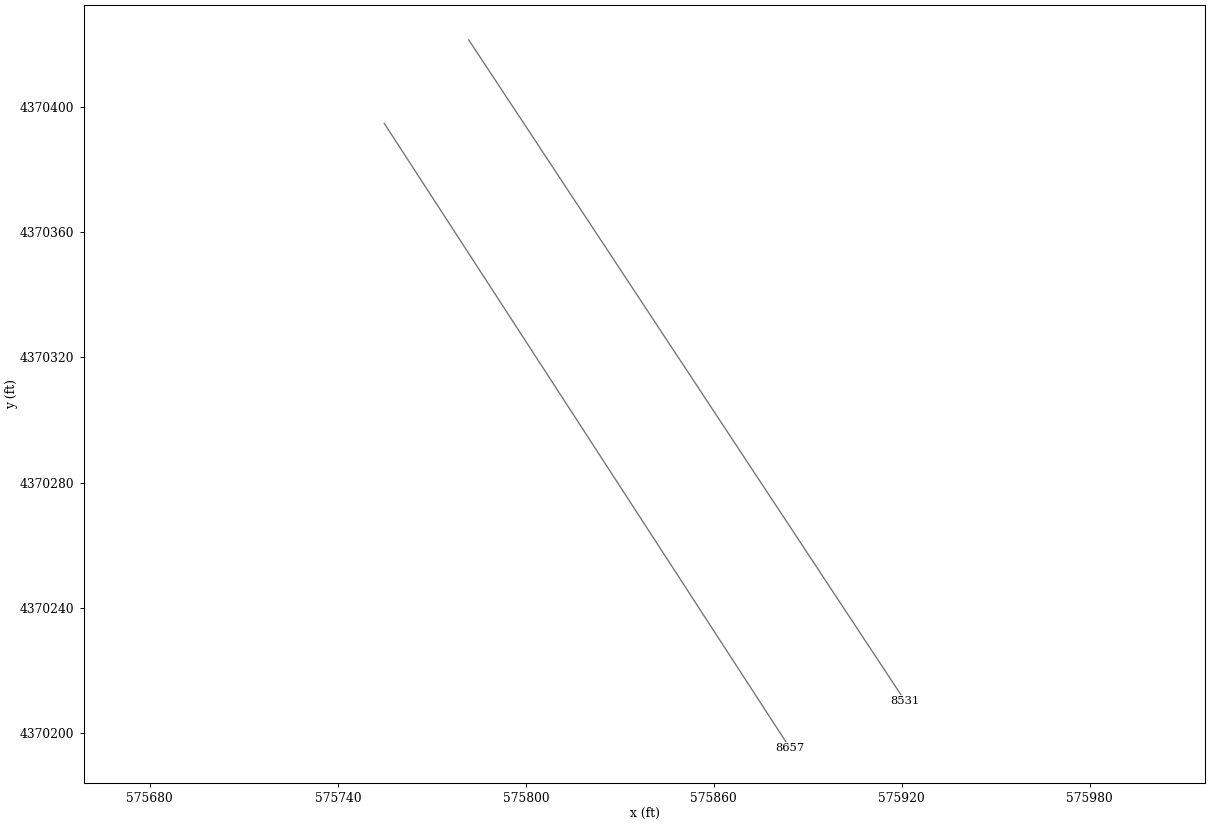
HEC-RAS study HickmanRun.prj: Hickman Run

--- HickmanRun.g02 (geometry) --- (continued)

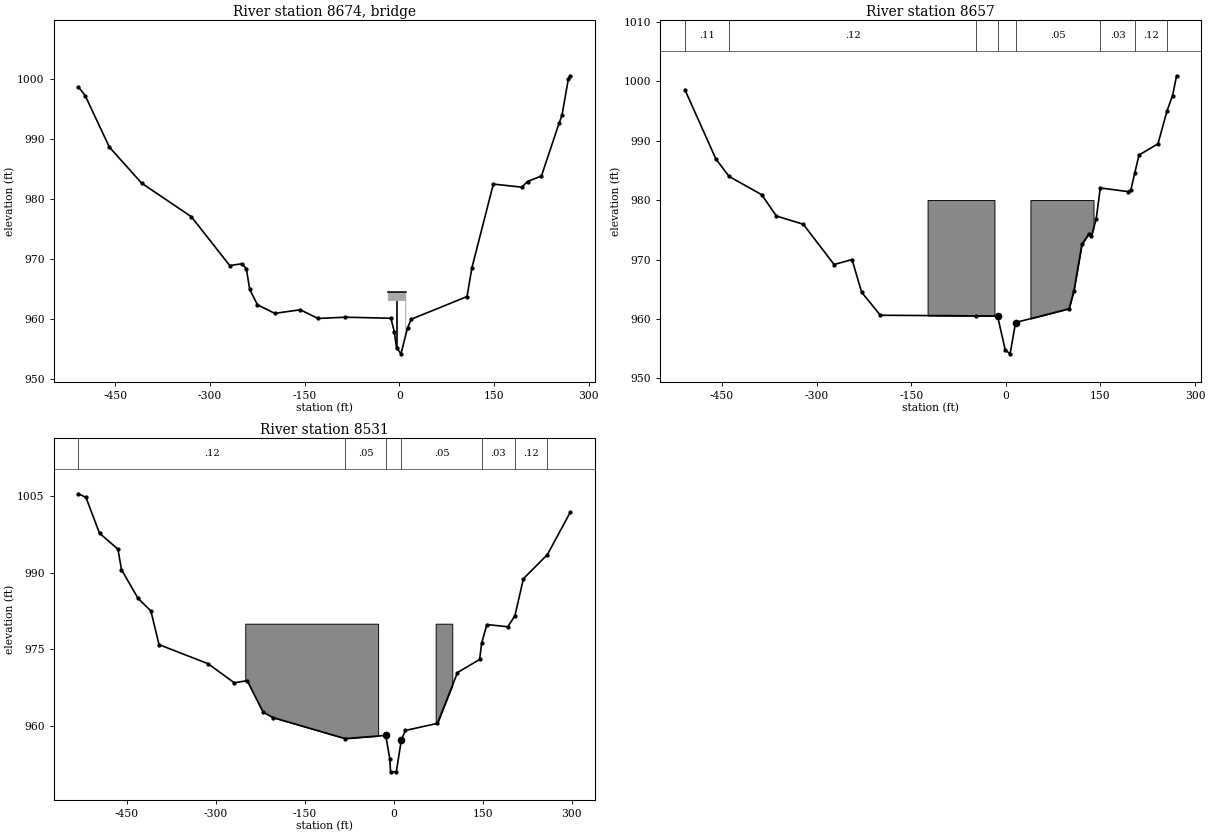
Type RM Length L Ch R = 3 ,8674    ,,,
BEGIN DESCRIPTION:
Loading dock bridge #1 (estimated from field recon)
END DESCRIPTION:
Bridge Culvert--1,0,-1,-1, 0
Deck Dist Width WeirC Skew NumUp NumDn MinLoCord MaxHiCord MaxSubmerge Is_Ogee
12,12.08,2.6,0, 4, 4, , , 0.98, 0, 0,0,,
     -18     9.5    9.51      11
   964.5   964.5   964.5   964.5
     963     963
     -18     9.5    9.51      11
   964.5   964.5   964.5   964.5
     963     963
Pier Skew, UpSta & Num, DnSta & Num=  ,-4.25, 2 ,-4.25, 2 , 0 , 0 , 0 ,,
      .5      .5
     950     963
      .5      .5
     950     963
BR Coef=-1 , 1 , 1 ,1.25, 0 ,,,0.8,0,1.2,0,
WSPro=,,,, 1 ,,,, 0 ,,,, 0 ,,,,-1 ,-1 ,-1 , 0 , 0 , 0 , 0 , 0
BC Design=,, 0 ,, 0 ,,,,,,
BC Use User HTab Curves=0
BC User HTab FreeFlow(D)= 0

Type RM Length L Ch R = 1 ,8657    ,125.81,126,126.19
BEGIN DESCRIPTION:
DS of Loading dock bridge #1
END DESCRIPTION:
XS GIS Cut Line= 2
575754.8139477354370394.63553357575884.1954533344370195.40605911
#Sta/Elev= 30
-508.727  998.59-459.482  986.91-438.484  983.97-386.844   980.9-363.648  977.32
-320.965  975.93-272.146  969.16-243.701  969.99-228.478  964.49-198.819  960.62
 -46.457  960.52 -13.123   960.5    -.82  954.76   6.791  954.13  15.486   959.4
 100.295  961.72 108.038  964.77 120.571  972.54 131.496   974.3 135.564  973.93
 143.209  976.78  149.77  982.04  193.34  981.43 198.228  981.72 204.528  984.62
 211.089  987.57 241.207  989.47 255.315  994.94 264.304  997.58 270.669 1000.91
#Mann= 8 ,-1 , 0
-508.727     .11       0-438.484     .12       0 -46.457     .05       0
 -13.123     .04       0  15.486     .05       0  149.77     .03       0
 204.528     .12       0 255.315     .13       0
#XS Ineff= 2 , 0
       0     -18                       0
Permanent Ineff=
       F       F
#Block Obstruct= 2 ,-1
    -124     -18     980      39     139     980
Bank Sta=-13.123,15.486
XS Rating Curve= 0 ,0
Exp/Cntr=0.5,0.3

Type RM Length L Ch R = 1 ,8531    ,344.351,347,349.812
BEGIN DESCRIPTION:
US of Culvert under building
END DESCRIPTION:
XS GIS Cut Line= 2
575781.797892069 4370421.2445739575920.9695737894370210.36869129
#Sta/Elev= 30
-531.168 1005.43-518.504 1004.72-495.669  997.71-464.633  994.59-458.596  990.58
-430.709  984.96-409.055   982.5-395.341   975.9-312.762  972.17-268.438  968.43
-246.752  968.85-220.046   962.7-203.346  961.63  -81.66  957.51 -13.189  958.13
   -6.43  953.61  -4.987     951   4.659     951  13.189  957.29  20.046   959.1
   73.95  960.49 107.776  970.43 145.112     973 148.392  976.13 157.283  979.83
 192.684   979.4 204.593  981.56 218.898   988.8 259.285  993.52 297.769 1001.78
#Mann= 7 ,-1 , 0
-531.168     .12       0  -81.66     .05       0 -13.189     .04       0
  13.189     .05       0 148.392     .03       0 204.593     .12       0
 259.285     .13       0
#XS Ineff= 2 , 0
       0     -26                       0
Permanent Ineff=
       F       F
#Block Obstruct= 2 ,-1
    -250     -26     980      71      99     980
Bank Sta=-13.189,13.189
XS Rating Curve= 0 ,0
Exp/Cntr=0.5,0.3