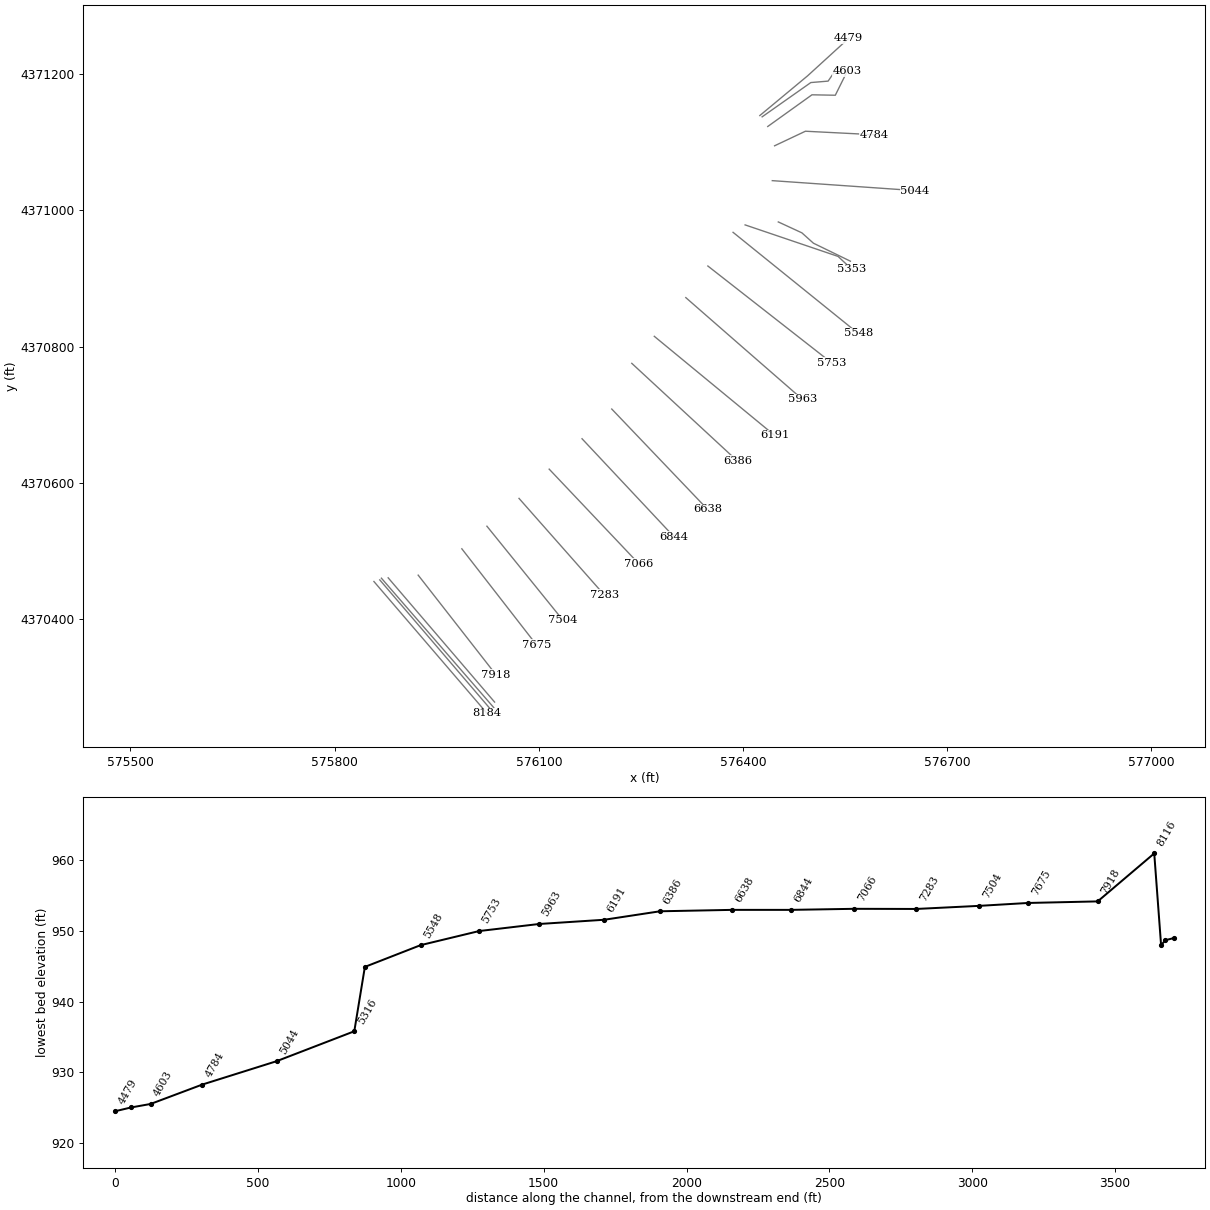
HEC-RAS study HickmanRun.prj: Hickman Run

--- HickmanRun.g02 (geometry) --- (continued)

Type RM Length L Ch R = 2 ,8485    ,,,
BEGIN DESCRIPTION:
Culvert under building (estimated from field recon)
END DESCRIPTION:
Bridge Culvert--1,0,-1,-1, 0
Deck Dist Width WeirC Skew NumUp NumDn MinLoCord MaxHiCord MaxSubmerge Is_Ogee
17,320,2.6,0, 60, 60, , , 0.98, 0, 0,0,,
-530.873-526.345-522.211 -507.48-488.878-466.667-460.892-457.776-455.577 -421.03
-407.743-400.295-353.117-337.402-310.531-297.835 -294.39 -272.31-262.434-246.194
-238.583-235.007-233.005-214.108-175.919 -165.65-133.301  -27.69  -26.01     -26
    13.3   13.31  21.818  26.739  56.791  63.156  67.651  75.722 105.545 119.783
 122.966 139.895 143.537 146.457 153.839 159.088 162.894 172.474 193.602 200.328
 209.678 216.109 224.147 231.102 269.193 273.228 284.678 291.995 298.064     423
 1000.05  998.84  996.69  996.05  996.09  994.93  991.54  990.19   990.2   983.6
  983.49   981.5  975.25   974.3  970.58  970.52  969.78  968.29  968.75  968.17
  966.38  964.66  964.31   964.8  960.73  960.08   958.7  956.94   956.5     980
     980  958.86   958.9  959.65  960.11  960.61  960.17  960.45  970.95  970.27
   970.7  970.75  971.39  972.69  977.56  979.16  978.65  979.01   978.7  980.26
  984.03  984.93  987.26  987.69  992.93  994.38  996.37  998.46  999.53  999.53
                                                                                
                                                                                
                                                                                
                                                                                
                                                                                
                                                                                
-530.873-526.345-522.211 -507.48-488.878-466.667-460.892-457.776-455.577 -421.03
-407.743-400.295-353.117-337.402-310.531-297.835 -294.39 -272.31-262.434-246.194
-238.583-235.007-233.005-214.108-175.919 -165.65-133.301  -27.69  -26.01     -26
    13.3   13.31  21.818  26.739  56.791  63.156  67.651  75.722 105.545 119.783
 122.966 139.895 143.537 146.457 153.839 159.088 162.894 172.474 193.602 200.328
 209.678 216.109 224.147 231.102 269.193 273.228 284.678 291.995 298.064     423
 1000.05  998.84  996.69  996.05  996.09  994.93  991.54  990.19   990.2   983.6
  983.49   981.5  975.25   974.3  970.58  970.52  969.78  968.29  968.75  968.17
  966.38  964.66  964.31   964.8  960.73  960.08   958.7  956.94   956.5     980
     980  958.86   958.9  959.65  960.11  960.61  960.17  960.45  970.95  970.27
   970.7  970.75  971.39  972.69  977.56  979.16  978.65  979.01   978.7  980.26
  984.03  984.93  987.26  987.69  992.93  994.38  996.37  998.46  999.53  999.53
                                                                                
                                                                                
                                                                                
                                                                                
                                                                                
                                                                                
BR Coef=-1 , 0 , 0 ,, 0 ,,,0.8,-1,,0,
WSPro=,,,, 1 ,,,, 0 ,,,, 0 ,,,,-1 ,-1 ,-1 , 0 , 0 , 0 , 0 , 0
Culvert=2,8,8,320,0.0125,0.5,1,58,1,951,0,949,0,Culvert #1  , 0 ,17
Culvert Bottom n=0.0125
BC Design=,, 0 ,, 0 ,,,,,,
BC Use User HTab Curves=0
BC User HTab FreeFlow(D)= 0

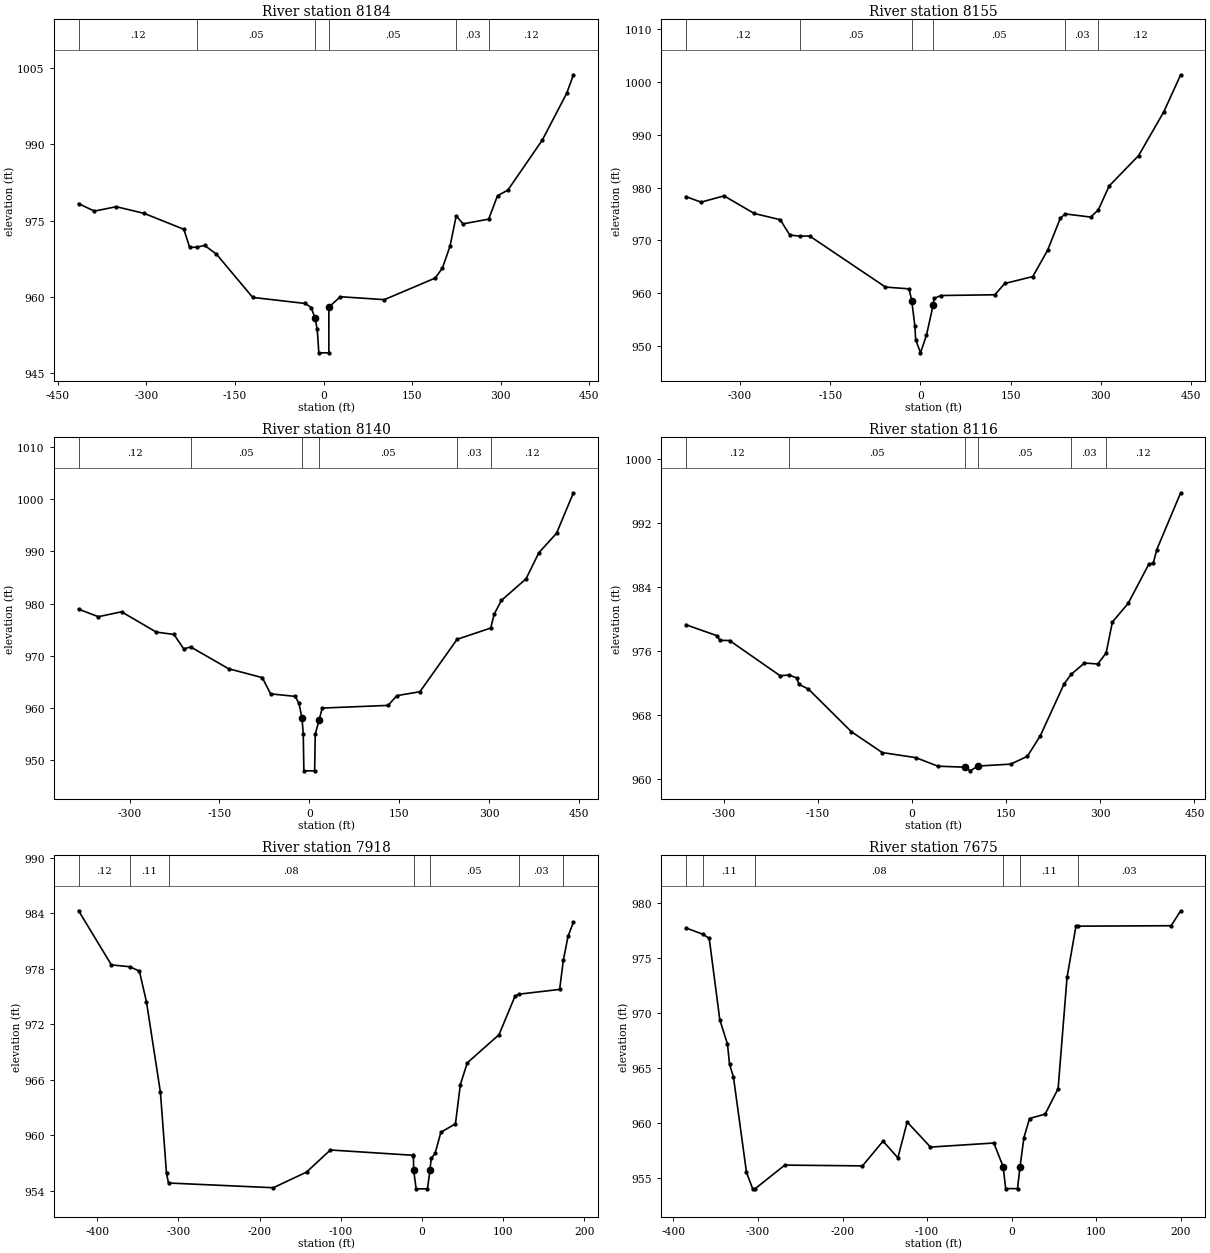
Type RM Length L Ch R = 1 ,8184    ,28.92,29,30.12
BEGIN DESCRIPTION:
DS of Culvert under building
END DESCRIPTION:
XS GIS Cut Line= 2
575857.7083330074370454.69332631576023.9553990624370260.93501192
#Sta/Elev= 30
  -414.6  978.36-387.894  976.89-350.919  977.76-304.167  976.46-236.549  973.32
-226.542  969.74-213.747  969.82-201.181  970.13-181.398  968.44-119.948  959.91
 -30.709  958.71 -20.932  957.92 -14.829  955.94 -10.663  953.65      -8     949
    8.99     949       9     958  28.543  960.04  102.92  959.47  189.14  963.72
  201.28  965.71 213.976  969.95 224.606  975.98 235.991  974.38 279.495  975.31
 294.488  979.93 311.909  981.01 370.374  990.89 411.581 1000.09 422.999 1003.72
#Mann= 6 ,-1 , 0
  -414.6     .12       0-213.747     .05       0 -14.829     .03       0
       9     .05       0 224.606     .03       0 279.495     .12       0
#XS Ineff= 2 , 0
       0     -35                       0
Permanent Ineff=
       F       F
Bank Sta=-14.829,9
XS Rating Curve= 0 ,0
Exp/Cntr=0.5,0.3

Type RM Length L Ch R = 1 ,8155    ,14.61,15,15.17
XS GIS Cut Line= 2
575866.2823571134370457.07686234 576029.478375134370266.57381199
#Sta/Elev= 30
-390.289   978.3-364.797  977.25-326.739  978.44-276.411   975.1-233.235  973.92
-217.454  971.03-201.214  970.81-184.318  970.83 -58.202  961.16 -18.898  960.82
 -14.469  958.47  -9.318  953.75  -8.038  951.22       0   948.7   9.908  952.03
  20.932  957.69  22.638     959  33.924  959.56 123.688   959.7 140.026  961.84
 186.713  963.15 211.286  968.11 232.513   974.2 240.518  975.02 283.104  974.42
 295.702  975.78  313.78  980.32 362.795  986.08 404.659  994.37 432.677 1001.38
#Mann= 6 ,-1 , 0
-390.289     .12       0-201.214     .05       0 -14.469     .03       0
  20.932     .05       0 240.518     .03       0 295.702     .12       0
Bank Sta=-14.469,20.932
XS Rating Curve= 0 ,0
Exp/Cntr=0.5,0.3

Type RM Length L Ch R = 1 ,8140    ,23.72,24,24.41
BEGIN DESCRIPTION:
US of Culvert #1
END DESCRIPTION:
XS GIS Cut Line= 2
575868.7085651434370459.58536637576033.7699591834370269.45722002
#Sta/Elev= 30
-385.039  978.96-352.133  977.51 -313.32  978.45-255.348  974.56-225.919  974.12
-209.514  971.35-197.933  971.72-134.646  967.55 -78.445  965.85 -64.534  962.74
 -23.819  962.26 -17.421  961.02 -12.139  958.15     -10     955      -9     948
       9     948      10     955  16.437  957.76  21.654  960.02  131.43  960.53
  146.49   962.4 184.744  963.15 246.785  973.18 302.887  975.34  308.76  978.02
 320.768  980.63 361.909  984.77 383.235  989.76  412.73  993.48 441.043 1001.24
#Mann= 6 ,-1 , 0
-385.039     .12       0-197.933     .05       0 -12.139     .03       0
  16.437     .05       0 246.785     .03       0 302.887     .12       0
Bank Sta=-12.139,16.437
XS Rating Curve= 0 ,0
Exp/Cntr=0.5,0.3

Type RM Length L Ch R = 1 ,8116    ,196.35,198,194.84
BEGIN DESCRIPTION:
Overland XS on King Street (TOR elevation estimated from terrain)
END DESCRIPTION:
XS GIS Cut Line= 2
575878.6480932664370460.11876638576035.0165911984370277.55575612
#Sta/Elev= 30
 -360.63   979.3 -310.86  977.92-306.332  977.34-290.945  977.32-210.367  972.91
-196.096     973-184.088  972.64-180.184  971.83-165.223  971.24 -96.883  965.91
 -47.638  963.29   6.102  962.65  41.175  961.58      85 961.457  92.454     961
     105 961.602 157.185  961.84 183.563  962.81 204.265  965.38  242.29   971.9
 253.806  973.11 274.738   974.5 295.965  974.38 309.285  975.77  319.16  979.63
 344.324  981.97 377.297  986.88 384.449  987.01 389.961  988.71 428.018  995.82
#Mann= 6 ,-1 , 0
 -360.63     .12       0-196.096     .05       0      85     .03       0
     105     .05       0 253.806     .03       0 309.285     .12       0
Bank Sta=85,105
XS Rating Curve= 0 ,0
Exp/Cntr=0.3,0.1

Type RM Length L Ch R = 1 ,7918    ,243.04,243,243.21
BEGIN DESCRIPTION:
Overland XS
END DESCRIPTION:
XS GIS Cut Line= 2
575922.7313178114370464.04763843576037.1623832254370317.53332462
#Sta/Elev= 30
-422.999  984.26-382.579  978.41-359.843  978.21-348.064  977.73-339.337  974.41
-322.178  964.65-314.633  955.86-312.172  954.83-183.038  954.32-142.093  956.01
-112.697   958.4 -11.024  957.83 -10.367   957.7     -10   956.2      -7   954.2
       7   954.2      10   956.2  11.647   957.5  16.339  958.03  23.556  960.32
   41.47  961.23  47.474  965.46  56.004  967.82  95.144  970.86 114.829  975.02
 119.291  975.24 169.882  975.76 174.409  978.91 180.249  981.51 186.909  983.03
#Mann= 7 ,-1 , 0
-422.999     .12       0-359.843     .11       0-312.172     .08       0
     -10     .04       0      10     .05       0 119.291     .03       0
 174.409     .12       0
#XS Ineff= 2 , 0
       0    -240                       0
Permanent Ineff=
       F       F
Bank Sta=-10,10
XS Rating Curve= 0 ,0
Exp/Cntr=0.3,0.1

Type RM Length L Ch R = 1 ,7675    ,170.35,171,171.34
BEGIN DESCRIPTION:
Overland XS
END DESCRIPTION:
XS GIS Cut Line= 2
575986.891718604 4370502.7419989576096.3636879574370361.85124516
#Sta/Elev= 30
-385.367  977.72-365.289  977.15-357.677  976.77-345.144  969.36-336.089  967.15
-333.661  965.33-329.003  964.15-313.583  955.47-306.234  953.98-303.576  953.98
-268.241  956.14-176.378  956.07-152.034  958.32-134.514   956.8-123.524  960.06
 -95.932  957.78 -20.997  958.15     -10     956      -7     954       7     954
      10     956    14.6  958.64   21.26  960.38  39.665  960.78   55.02  963.09
  65.584  973.22  76.148  977.89  78.084  977.88 188.747  977.92     200  979.28
#Mann= 6 ,-1 , 0
-385.367     .12       0-365.289     .11       0-303.576     .08       0
     -10     .04       0      10     .11       0  78.084     .03       0
Bank Sta=-10,10
XS Rating Curve= 0 ,0
Exp/Cntr=0.3,0.1

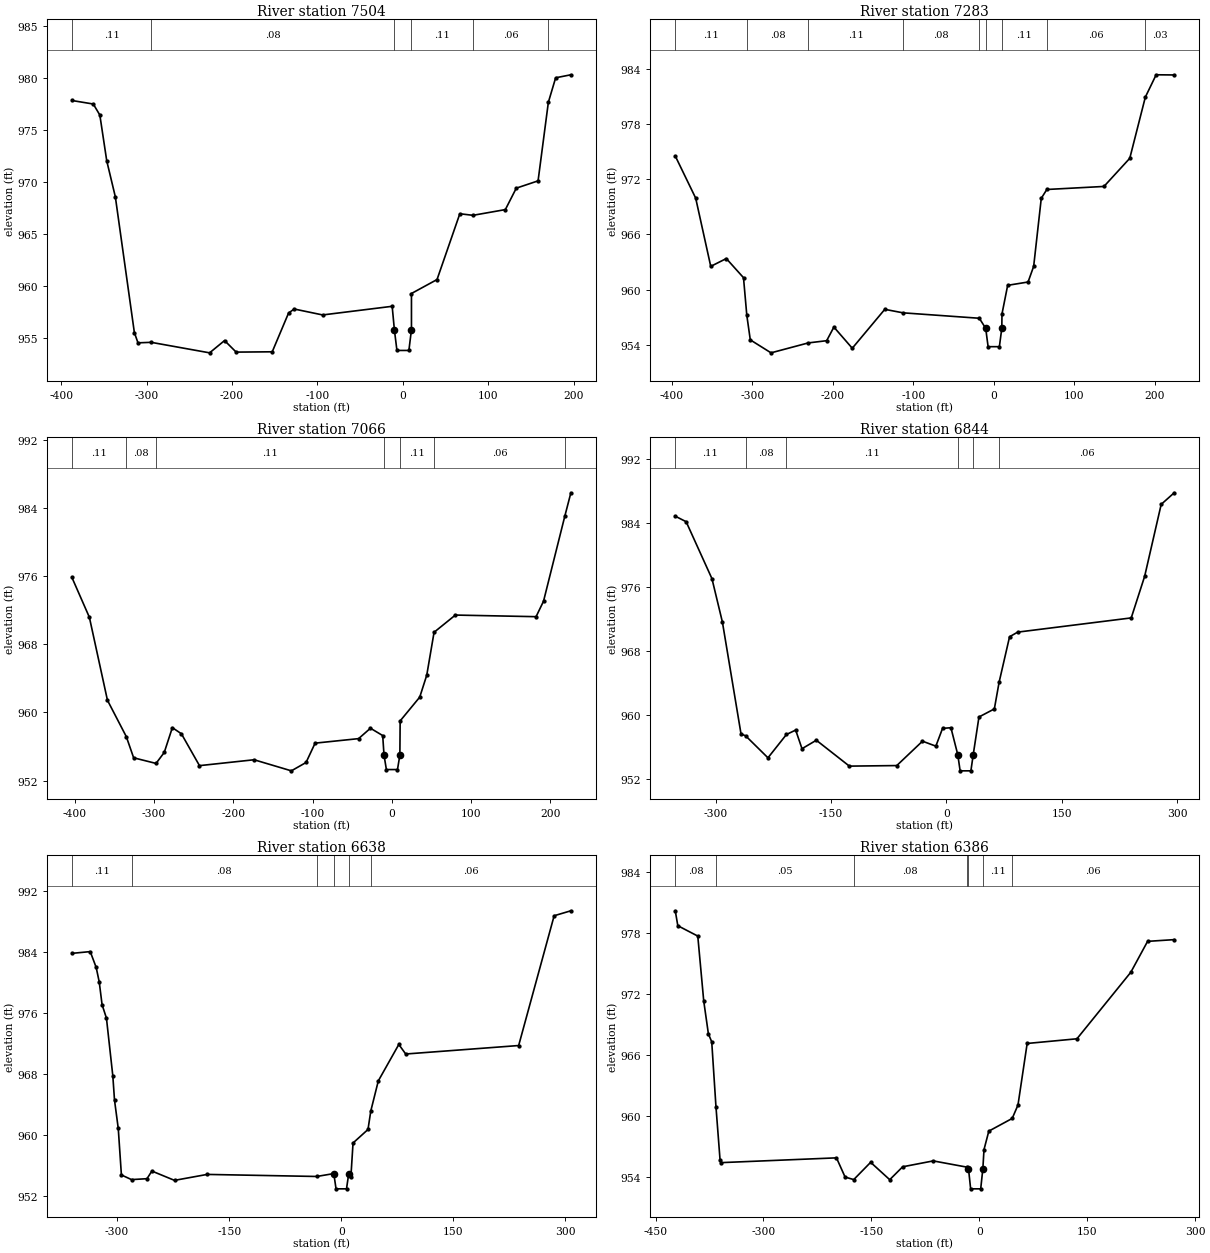
Type RM Length L Ch R = 1 ,7504    ,219.81,221,221.64
BEGIN DESCRIPTION:
Overland XS
END DESCRIPTION:
XS GIS Cut Line= 2
576023.7359430594370535.94691131576135.655456442 4370397.5707576
#Sta/Elev= 30
-387.336  977.81-362.336  977.47-354.659  976.41-346.588  972.01-336.516  968.55
-314.272  955.52-310.039  954.53-294.619  954.58-226.214  953.57-208.727  954.75
-195.144  953.64 -152.92  953.67-133.825  957.39-127.264  957.78  -93.93  957.21
 -12.566  958.04     -10   955.8      -7   953.8       7   953.8      10   955.8
  10.007  959.27  39.928  960.61  66.601  966.93  81.988  966.78 119.882  967.33
 132.677  969.39 158.169  970.09  170.21  977.64  178.74  979.99 196.555  980.28
#Mann= 6 ,-1 , 0
-387.336     .11       0-294.619     .08       0     -10     .04       0
      10     .11       0  81.988     .06       0  170.21     .03       0
Bank Sta=-10,10
XS Rating Curve= 0 ,0
Exp/Cntr=0.3,0.1

Type RM Length L Ch R = 1 ,7283    ,216.08,217,217.72
BEGIN DESCRIPTION:
Overland XS
END DESCRIPTION:
XS GIS Cut Line= 2
576070.8976476424370576.82668782576195.9144171874370435.27451807
#Sta/Elev= 30
-395.505  974.53-370.144  969.95-351.444  962.53-332.119  963.38-310.761   961.3
 -306.66  957.21-302.329  954.54-276.575  953.13-230.282  954.21 -207.48  954.45
-198.524  955.93-175.689  953.63-135.302  957.86 -112.73  957.48 -17.946  956.89
     -10   955.8      -7   953.8       7   953.8      10   955.8  10.236  957.36
   17.29  960.47  42.618  960.83  49.573  962.53  59.022  969.93  65.945  970.89
 136.877  971.22  168.93  974.28 188.255  980.93 201.673  983.36 224.114  983.34
#Mann= 9 ,-1 , 0
-395.505     .11       0 -306.66     .08       0-230.282     .11       0
 -112.73     .08       0 -17.946     .11       0     -10     .04       0
      10     .11       0  65.945     .06       0 188.255     .03       0
Bank Sta=-10,10
XS Rating Curve= 0 ,0
Exp/Cntr=0.3,0.1

Type RM Length L Ch R = 1 ,7066    ,227.65,222,219.46
BEGIN DESCRIPTION:
Overland XS
END DESCRIPTION:
XS GIS Cut Line= 2
 576115.215568194370619.82177635 576247.175681824370480.58303863
#Sta/Elev= 30
-403.675  975.84 -381.66  971.17-358.858  961.43-335.105  957.17 -325.82  954.68
-297.572  954.02-287.205  955.31-277.001  958.22-265.584   957.5-242.782  953.76
-173.885  954.45 -126.87  953.15-108.333  954.13 -96.916   956.4  -42.06  956.93
   -27.1  958.15 -11.647  957.29     -10     955      -7   953.3       7   953.3
      10     955  10.367  959.01  35.072   961.8   43.93  964.38   53.15  969.41
   80.02  971.43 181.824  971.24 191.207  973.05 217.979     983 225.722  985.78
#Mann= 7 ,-1 , 0
-403.675     .11       0-335.105     .08       0-297.572     .11       0
     -10     .04       0      10     .11       0   53.15     .06       0
 217.979     .03       0
Bank Sta=-10,10
XS Rating Curve= 0 ,0
Exp/Cntr=0.3,0.1

Type RM Length L Ch R = 1 ,6844    ,205.51,206,206.04
BEGIN DESCRIPTION:
Overland XS
END DESCRIPTION:
XS GIS Cut Line= 2
576163.501984786 4370664.4688809576298.7691784584370520.27104712
#Sta/Elev= 30
-352.329  984.87-338.189  984.18-304.626  977.05-291.043  971.62-266.831  957.61
-260.925  957.39-231.824  954.63-207.776  957.55-195.801   958.1-187.566  955.77
 -168.93  956.83-125.984  953.59 -64.337  953.66 -30.938  956.71  -13.55  956.09
  -4.856  958.31   6.037   958.4      15     955      18     953      32     953
      35     955  42.487  959.74    62.5  960.75  68.701   964.1  82.283  969.78
  92.815  970.36 240.453  972.14 257.907  977.35 279.396  986.35 296.325   987.8
#Mann= 6 ,-1 , 0
-352.329     .11       0-260.925     .08       0-207.776     .11       0
      15     .04       0      35     .11       0  68.701     .06       0
Bank Sta=15,35
XS Rating Curve= 0 ,0
Exp/Cntr=0.3,0.1

Type RM Length L Ch R = 1 ,6638    ,248.71,252,251.6
BEGIN DESCRIPTION:
Overland XS
END DESCRIPTION:
XS GIS Cut Line= 2
576207.1584893264370708.12538544576347.7200590634370560.94965562
#Sta/Elev= 30
-360.433  983.86-335.925  984.09-327.986  982.02-323.885  980.11-320.079  977.13
-314.239  975.37-305.709   967.8-303.445  964.62-298.425  960.91-294.226  954.82
-280.676  954.21-259.974  954.33-253.445  955.33-223.163  954.11-179.495  954.89
 -32.907  954.62     -10     955      -7     953       7     953      10     955
  12.828   954.5  15.748  959.01  35.761  960.78  39.501   963.2  49.573  967.15
  77.001  971.92   86.22  970.67 237.369  971.78 284.875  988.79 307.251  989.44
#Mann= 6 ,-1 , 0
-360.433     .11       0-280.676     .08       0 -32.907     .11       0
     -10     .04       0      10     .11       0  39.501     .06       0
Bank Sta=-10,10
XS Rating Curve= 0 ,0
Exp/Cntr=0.3,0.1

Type RM Length L Ch R = 1 ,6386    ,192.74,195,195.13
BEGIN DESCRIPTION:
Overland XS
END DESCRIPTION:
XS GIS Cut Line= 2
 576236.593025694370775.26368227576391.772803608 4370631.7272645
#Sta/Elev= 30
-422.572  980.17-419.029   978.7-391.273  977.68-383.005  971.29-376.509  968.05
-371.883  967.27-365.978  960.86-360.335  955.67-358.793  955.38-198.491  955.85
-186.516  953.96-174.508  953.71-150.984  955.41-124.475   953.7-106.496  954.97
 -63.976  955.55 -17.454  954.94     -15   954.8     -12   952.8       2   952.8
       5   954.8   6.562  956.66  13.255  958.48  45.768  959.73  53.806  961.05
  66.568  967.11 135.761  967.57 210.663  974.12 233.957  977.16 270.965  977.33
#Mann= 7 ,-1 , 0
-422.572     .08       0-365.978     .05       0-174.508     .08       0
 -17.454     .11       0     -15     .04       0       5     .11       0
  45.768     .06       0
#XS Ineff= 2 , 0
       0    -295                       0
Permanent Ineff=
       F       F
Bank Sta=-15,5
XS Rating Curve= 0 ,0
Exp/Cntr=0.3,0.1

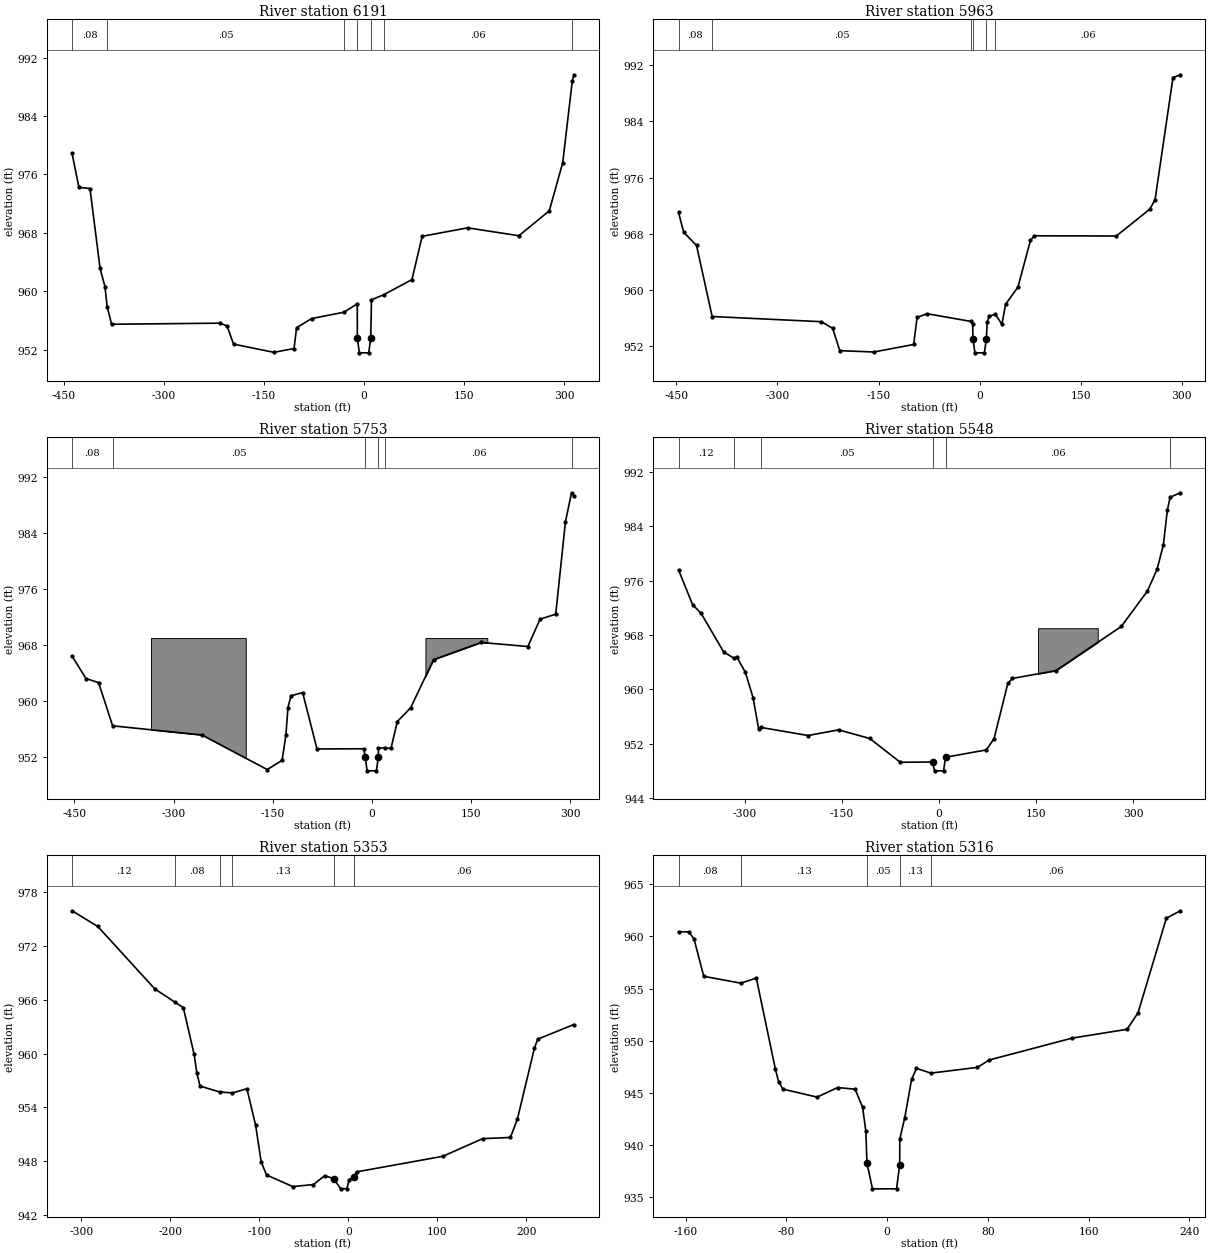
Type RM Length L Ch R = 1 ,6191    ,228.64,228,227.43
BEGIN DESCRIPTION:
Overland XS
END DESCRIPTION:
XS GIS Cut Line= 2
576269.6668740984370814.95169076576446.5392682844370669.29691296
#Sta/Elev= 30
-437.402  978.89-427.165  974.23-410.597  974.08-395.407  963.14-388.189  960.67
 -384.81  957.92-378.215  955.51-215.354  955.66-205.249  955.27 -195.44  952.79
-135.171  951.67-104.856  952.19-101.083  955.03 -78.609  956.29  -30.02  957.16
 -10.138  958.31     -10   953.6      -7   951.6       7   951.6      10   953.6
  11.155  958.86  29.298  959.54  71.785  961.62  87.041  967.54 155.249   968.7
 232.021  967.62 277.493  971.03 297.605  977.59 312.041  988.82 314.337  989.64
#Mann= 7 ,-1 , 0
-437.402     .08       0 -384.81     .05       0  -30.02     .11       0
     -10     .04       0      10     .11       0  29.298     .06       0
 312.041     .03       0
#XS Ineff= 2 , 0
       0    -157                       0
Permanent Ineff=
       F       F
Bank Sta=-10,10
XS Rating Curve= 0 ,0
Exp/Cntr=0.3,0.1

Type RM Length L Ch R = 1 ,5963    ,208.64,210,210.84
BEGIN DESCRIPTION:
Overland XS
END DESCRIPTION:
XS GIS Cut Line= 3
576315.9690426714370871.83651547 576400.075555714370798.38581056
576486.9557487844370722.67653762
#Sta/Elev= 30
-446.719  971.02-439.009  968.18-420.013  966.31 -396.85  956.18-234.678  955.44
-218.077  954.49-207.513  951.31-157.119  951.12 -97.933  952.19 -92.782  956.05
 -77.986  956.58 -12.959  955.48 -10.302  955.11     -10     953      -7     951
       7     951      10     953  11.089  955.33  14.075  956.24  23.425  956.49
  33.038  955.06  38.517  957.93  56.759  960.37  75.328  967.02  81.234  967.69
 202.789  967.66 252.461  971.49 260.203  972.83 286.811  990.24 297.703  990.65
#Mann= 6 ,-1 , 0
-446.719     .08       0 -396.85     .05       0 -12.959     .11       0
     -10     .04       0      10     .11       0  23.425     .06       0
#XS Ineff= 2 , 0
       0     -78                       0
Permanent Ineff=
       F       F
Bank Sta=-10,10
XS Rating Curve= 0 ,0
Exp/Cntr=0.3,0.1

Type RM Length L Ch R = 1 ,5753    ,207.65,205,204.05
BEGIN DESCRIPTION:
Overland XS
END DESCRIPTION:
XS GIS Cut Line= 2
576348.3814750714370918.26974804576530.6793093244370775.65992228
#Sta/Elev= 30
-453.543  966.41-432.349   963.2-413.451  962.63-392.159  956.44-256.759  955.13
-158.202  950.18-135.696   951.5-129.921  955.15 -126.87  959.03-122.277  960.74
-104.659   961.2 -82.874  953.13 -12.172  953.16     -10     952      -7     950
       7     950      10     952  10.105  953.26  20.604  953.28  29.101  953.21
  38.648  957.06  58.694     959  93.471  965.91 165.322  968.37 236.253  967.79
 254.626   971.7 278.346  972.42  293.11  985.66 302.329  989.79 305.807  989.32
#Mann= 6 ,-1 , 0
-453.543     .08       0-392.159     .05       0     -10     .04       0
      10     .11       0  20.604     .06       0 302.329     .03       0
#XS Ineff= 2 , 0
       0    -105                       0
Permanent Ineff=
       F       F
#Block Obstruct= 2 ,-1
  81.168 174.836     969-334.186-190.715     969
Bank Sta=-10,10
XS Rating Curve= 0 ,0
Exp/Cntr=0.3,0.1

Type RM Length L Ch R = 1 ,5548    ,195,195,195
BEGIN DESCRIPTION:
Overland XS
END DESCRIPTION:
XS GIS Cut Line= 2
576385.4207715294370967.74793265576569.3066138024370819.24937082
#Sta/Elev= 30
-402.592  977.57-380.807  972.45-367.717  971.18-332.776  965.49-316.568  964.56
-312.664  964.78-299.213  962.49-287.434  958.77-278.773  954.18-275.197  954.39
-202.526   953.2-155.315  954.03-107.251  952.77 -59.875  949.26     -10   949.3
      -7     948       7     948      10     950  73.097  951.08  85.007  952.74
 106.299  960.87  113.32   961.6 180.479  962.75  281.66  969.25 321.949  974.46
 337.041   977.7 346.686  981.27 352.789  986.35 357.054  988.27 372.867  988.93
#Mann= 6 ,-1 , 0
-402.592     .12       0-316.568     .08       0-275.197     .05       0
     -10     .04       0      10     .06       0 357.054     .03       0
#Block Obstruct= 1 ,-1
 153.051 245.243     969
Bank Sta=-10,10
XS Rating Curve= 0 ,0
Exp/Cntr=0.3,0.1

Type RM Length L Ch R = 1 ,5353    ,37,37,37
BEGIN DESCRIPTION:
Overland XS
END DESCRIPTION:
XS GIS Cut Line= 3
576403.1083157484370978.67501279576539.6983414364370932.37284421
576559.8730536854370913.52096398
#Sta/Elev= 30
-310.466  975.94-281.562  974.19-217.454  967.22-194.849  965.74-185.466  965.14
-173.327  959.92-170.276  957.86-166.667  956.38-144.619  955.73-130.249  955.62
-114.042  956.09-104.232  952.01 -97.999  947.93 -91.995  946.47 -62.434  945.17
 -39.272   945.4 -26.739  946.38 -16.699  946.07   -8.53  944.92  -1.804  944.94
    .984  945.94   6.004  946.28   9.121  946.81  106.07  948.55 150.951  950.52
 182.054  950.65 189.895  952.71  208.99  960.61 212.697  961.62 253.314  963.25
#Mann= 6 ,-1 , 0
-310.466     .12       0-194.849     .08       0-144.619     .05       0
-130.249     .13       0 -16.699     .04       0   6.004     .06       0
#XS Ineff= 2 , 0
       0     -50              23       0
Permanent Ineff=
       F       F
Bank Sta=-16.699,6.004
XS Rating Curve= 0 ,0
Exp/Cntr=0.3,0.1

Type RM Length L Ch R = 1 ,5316    ,272,272,272
BEGIN DESCRIPTION:
DS of Culvert #1
END DESCRIPTION:
XS GIS Cut Line= 4
 576451.870220354370983.03060484576486.5290287794370967.02250864
576503.4637169884370951.80994045 576557.836989664370925.35025213
#Sta/Elev= 30
-165.584  960.44-157.513  960.43-153.314  959.76-145.571  956.17-116.175  955.51
-103.839     956 -88.747  947.29 -86.188  946.08 -82.743  945.36 -55.577  944.59
 -39.272  945.51 -25.427  945.35 -19.455  943.61 -16.929  941.35     -16  938.28
 -11.647   935.8    7.48   935.8      10  938.13  10.039  940.58  14.009  942.63
  19.423  946.29  23.294  947.35  34.711  946.89  71.654  947.44   81.07  948.15
 146.982  950.25 190.486  951.09 199.213  952.68 221.654  961.74 232.743  962.45
#Mann= 5 ,-1 , 0
-165.584     .08       0-116.175     .13       0     -16     .05       0
      10     .13       0  34.711     .06       0
Bank Sta=-16,10
XS Rating Curve= 0 ,0
Exp/Cntr=0.5,0.3

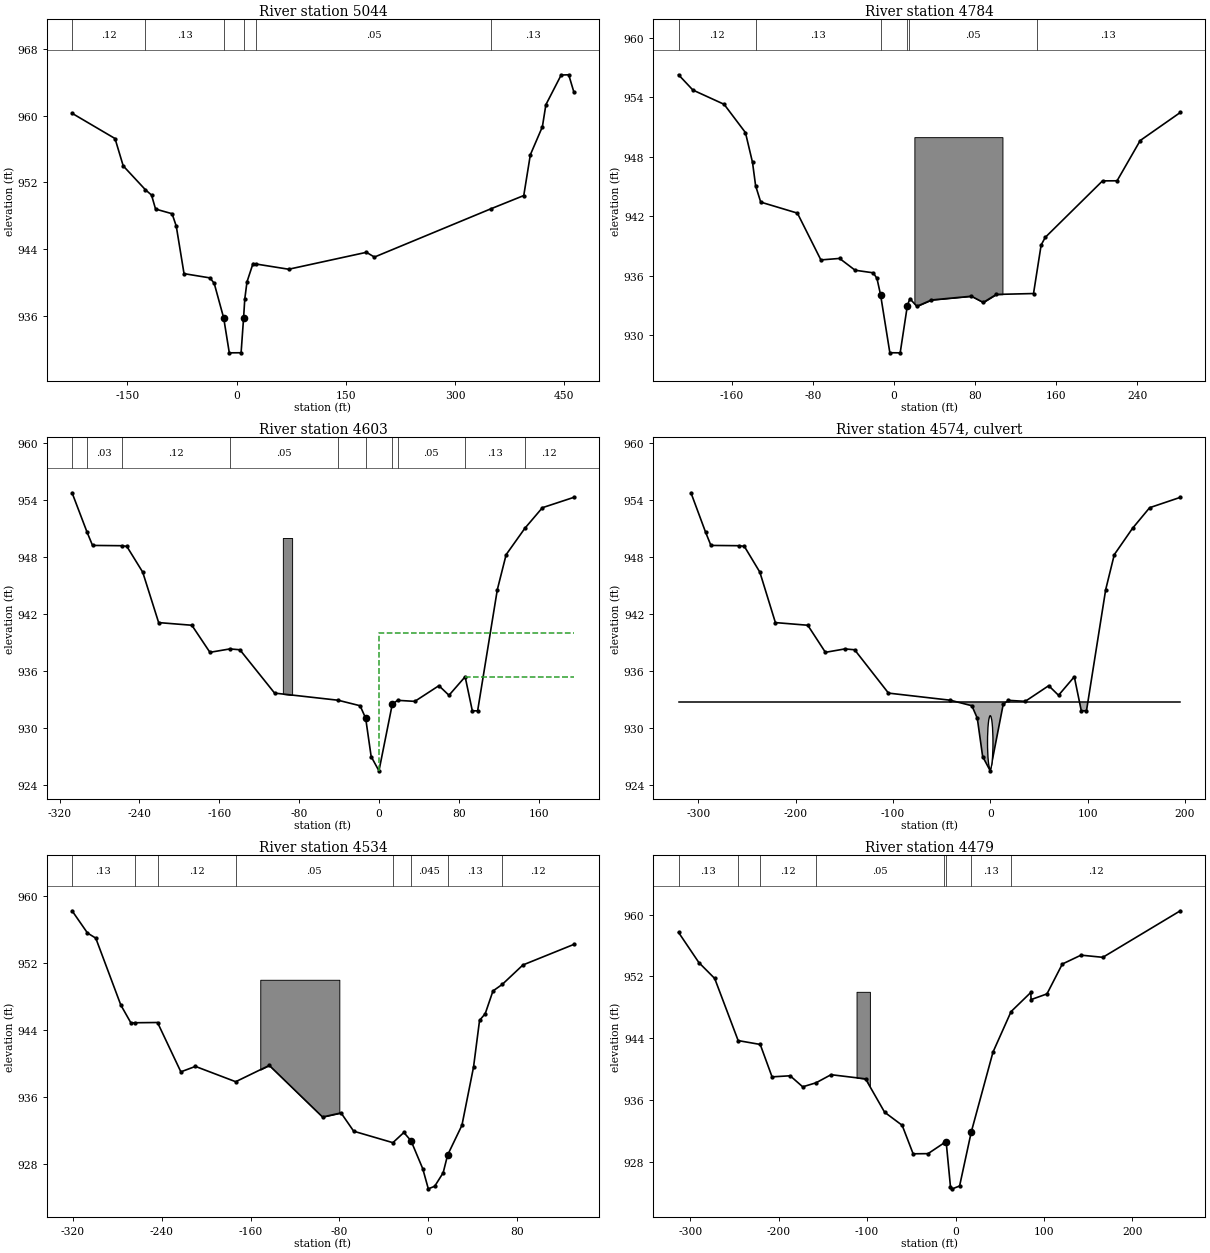
Type RM Length L Ch R = 1 ,5044    ,259.62,260,266.55
XS GIS Cut Line= 2
576443.0523562414371043.69494959576652.6023588314371029.08893341
#Sta/Elev= 30
-225.984   960.3-166.995  957.27-155.741  953.99-125.197  951.12-116.864  950.49
-111.319  948.81 -88.615  948.25 -82.907  946.77 -72.211  941.06 -36.516  940.55
 -30.741  939.89  -17.73 935.736 -10.039  931.56   6.168  931.57    9.57 935.735
   11.22  938.02  14.272  940.08  22.507  942.27  27.067  942.21  71.522  941.59
 178.281  943.62 189.272  943.05 349.508  948.85  394.39  950.43 403.412  955.32
 419.948  958.68  424.77  961.33 445.735  964.89 456.135  964.92 463.189  962.85
#Mann= 6 ,-1 , 0
-225.984     .12       0-125.197     .13       0  -17.73    .045       0
    9.57     .13       0  27.067     .05       0 349.508     .13       0
Bank Sta=-17.73,9.57
XS Rating Curve= 0 ,0
Exp/Cntr=0.3,0.1

Type RM Length L Ch R = 1 ,4784    ,180.16,181,181.86
XS GIS Cut Line= 3
576446.4386842834371094.91963822576491.7258688434371116.31659849
576592.4897020884371111.21729442
#Sta/Elev= 30
-212.697  956.29-198.524  954.75-167.684  953.31-146.654  950.46-139.665  947.45
-136.614   945.1-131.562  943.45 -95.374  942.34 -72.178  937.62 -53.707  937.77
 -38.386  936.58 -20.538  936.32 -16.831  935.76 -13.255   934.1  -4.101  928.26
   6.102  928.25  13.189  933.01  15.682  933.71  22.539  932.94  36.942  933.58
  76.411  933.96  88.091  933.33 100.919  934.14  137.73  934.23 145.243  939.12
 149.278  939.89  205.84  945.59  220.21   945.6 243.045  949.66 282.644  952.49
#Mann= 6 ,-1 , 0
-212.697     .12       0-136.089     .13       0 -13.255    .045       0
  13.189     .13       0  14.698     .05       0 140.682     .13       0
#Block Obstruct= 1 ,-1
  20.112 107.054     950
Bank Sta=-13.255,13.189
XS Rating Curve= 0 ,0
Exp/Cntr=0.5,0.3

Type RM Length L Ch R = 1 ,4603    ,70.048,69,67.548
BEGIN DESCRIPTION:
US of Access road
END DESCRIPTION:
XS GIS Cut Line= 4
576436.3680921594371123.26908657576501.3484049624371169.83643115
576535.6384053864371169.20244714  576552.99676564371204.12643157
#Sta/Elev= 30
 -307.48  954.76 -292.52  950.63-286.975  949.22 -257.71  949.19-252.625  949.12
-236.713  946.41-220.735   941.1-187.467  940.82-169.357  937.97-149.344  938.33
-139.337  938.24 -104.56  933.68 -40.945  932.93 -18.898  932.35  -13.32  931.04
  -7.808     927       0   925.5   13.32   932.5  18.668  932.92  35.892  932.81
  60.072  934.46  70.144  933.45  86.352   935.4  93.537  931.82  98.852  931.81
 118.602  944.57 127.428  948.25 146.161  951.02 163.747  953.19 195.276  954.28
#Mann= 10 ,-1 , 0
 -307.48     .13       0 -292.52     .03       0 -257.71     .12       0
-149.344     .05       0 -40.945     .13       0  -13.32    .045       0
   13.32     .13       0  18.668     .05       0  86.352     .13       0
 146.161     .12       0
#XS Ineff= 2 , 0
       0 -149.34     940   86.35       0   935.4
Permanent Ineff=
       F       T
#Block Obstruct= 1 ,-1
 -96.293 -87.008     950
Bank Sta=-13.32,13.32
XS Rating Curve= 0 ,0
Exp/Cntr=0.5,0.3

Type RM Length L Ch R = 2 ,4574    ,,,
BEGIN DESCRIPTION:
Access road (Structure from effective HEC-2 model and field recon)
END DESCRIPTION:
Bridge Culvert--1,0,-1,-1, 0
Deck Dist Width WeirC Skew NumUp NumDn MinLoCord MaxHiCord MaxSubmerge Is_Ogee
11,28.8,2.9,0, 6, 6, , , 0.98, 0, 0,0,,
-320.243     -40     -20      20      40  195.28
   932.7   932.7   932.7   932.7   932.7   932.7
                                                
-320.243     -40     -20      20      40  195.28
   932.7   932.7   932.7   932.7   932.7   932.7
                                                
BR Coef=-1 , 0 , 0 ,, 0 ,,,0.8,-1,,0,
WSPro=,,,, 1 ,,,, 0 ,,,, 0 ,,,,-1 ,-1 ,-1 , 0 , 0 , 0 , 0 , 0
Culvert=1,5.6,,28.8,0.0125,0.5,1,1,1,925.7,0,925.6,0,Culvert #1  , 0 ,11
Culvert Bottom n=0.0125
BC Design=,, 0 ,, 0 ,,,,,,
BC Use User HTab Curves=0
BC User HTab FreeFlow(D)= 0

Type RM Length L Ch R = 1 ,4534    ,35.14,55,79.81
BEGIN DESCRIPTION:
DS of Access road
END DESCRIPTION:
XS GIS Cut Line= 4
576428.1110600574371137.45143075576499.6567649414371187.82877537
576525.055749255 4371189.9440874576539.0247334274371210.26510365
#Sta/Elev= 30
-320.604  958.25-306.726  955.59-299.278  954.98-276.739  946.98-267.552  944.82
-264.403  944.86-243.701  944.89-222.703  938.99 -209.58  939.64 -173.36  937.81
-143.143  939.76  -95.21  933.59 -78.543  934.08 -67.159  931.89  -31.89  930.52
 -22.014  931.74 -15.551  930.74   -5.03  927.41       0     925    5.74  925.31
  13.353  926.92  17.356  929.04  30.249   932.6  40.682  939.56  46.096  945.14
  51.214  945.95  58.169  948.66  66.568  949.45  85.138  951.77 130.971  954.23
#Mann= 8 ,-1 , 0
-320.604     .13       0-264.403     .03       0-243.701     .12       0
 -173.36     .05       0  -31.89     .13       0 -15.551    .045       0
  17.356     .13       0  66.568     .12       0
#XS Ineff= 2 , 0
       0    -145                       0
Permanent Ineff=
       F       F
#Block Obstruct= 1 ,-1
-151.247 -80.085     950
Bank Sta=-15.551,17.356
XS Rating Curve= 0 ,0
Exp/Cntr=0.5,0.3

Type RM Length L Ch R = 1 ,4479    ,88.34,106,120.98
BEGIN DESCRIPTION:
(Surveyed XS HIC_02)
END DESCRIPTION:
XS GIS Cut Line= 3
576424.7247320154371139.35643077576494.9994208834371197.77744749
576555.3254376294371252.80908817
#Sta/Elev= 30
-313.353   957.7-290.354  953.79-272.441  951.73-245.899  943.68-220.932  943.18
-207.546  938.98-187.073  939.12-172.867  937.69-157.808  938.21-140.814  939.26
-101.772  938.72 -80.217   934.4 -60.335   932.7 -47.933  929.01  -31.07  929.03
  -13.55  930.37 -10.564  930.56  -5.676  924.72  -3.609  924.47   4.626  924.84
  17.782  931.81  42.421  942.19  62.894  947.44  85.236  949.92  85.466  948.99
 103.478  949.73 120.866   953.6 141.995  954.75 166.699  954.47 254.364   960.5
#Mann= 8 ,-1 , 0
-313.353     .13       0-245.899     .03       0-220.932     .12       0
-157.808     .05       0  -13.55     .13       0 -10.564    .045       0
  17.782     .13       0  62.894     .12       0
#XS Ineff= 2 , 0
       0    -125                       0
Permanent Ineff=
       F       F
#Block Obstruct= 1 ,-1
-111.975  -96.85     950
Bank Sta=-10.564,17.782
XS Rating Curve= 0 ,0
Exp/Cntr=0.3,0.1