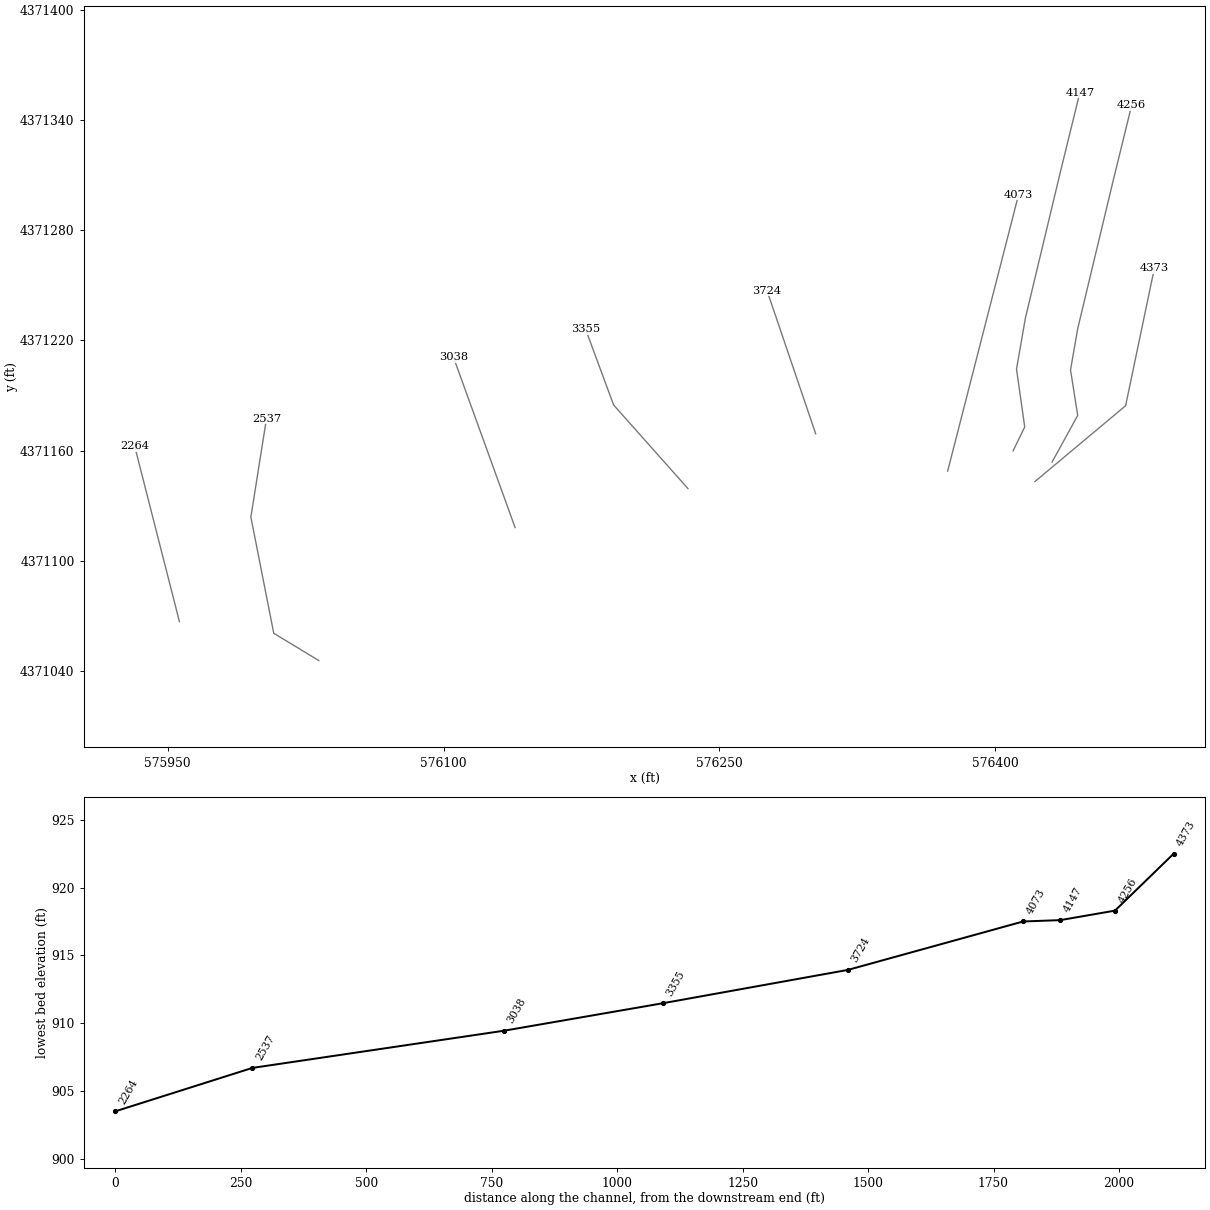
HEC-RAS study HickmanRun.prj: Hickman Run

--- HickmanRun.g02 (geometry) --- (continued)

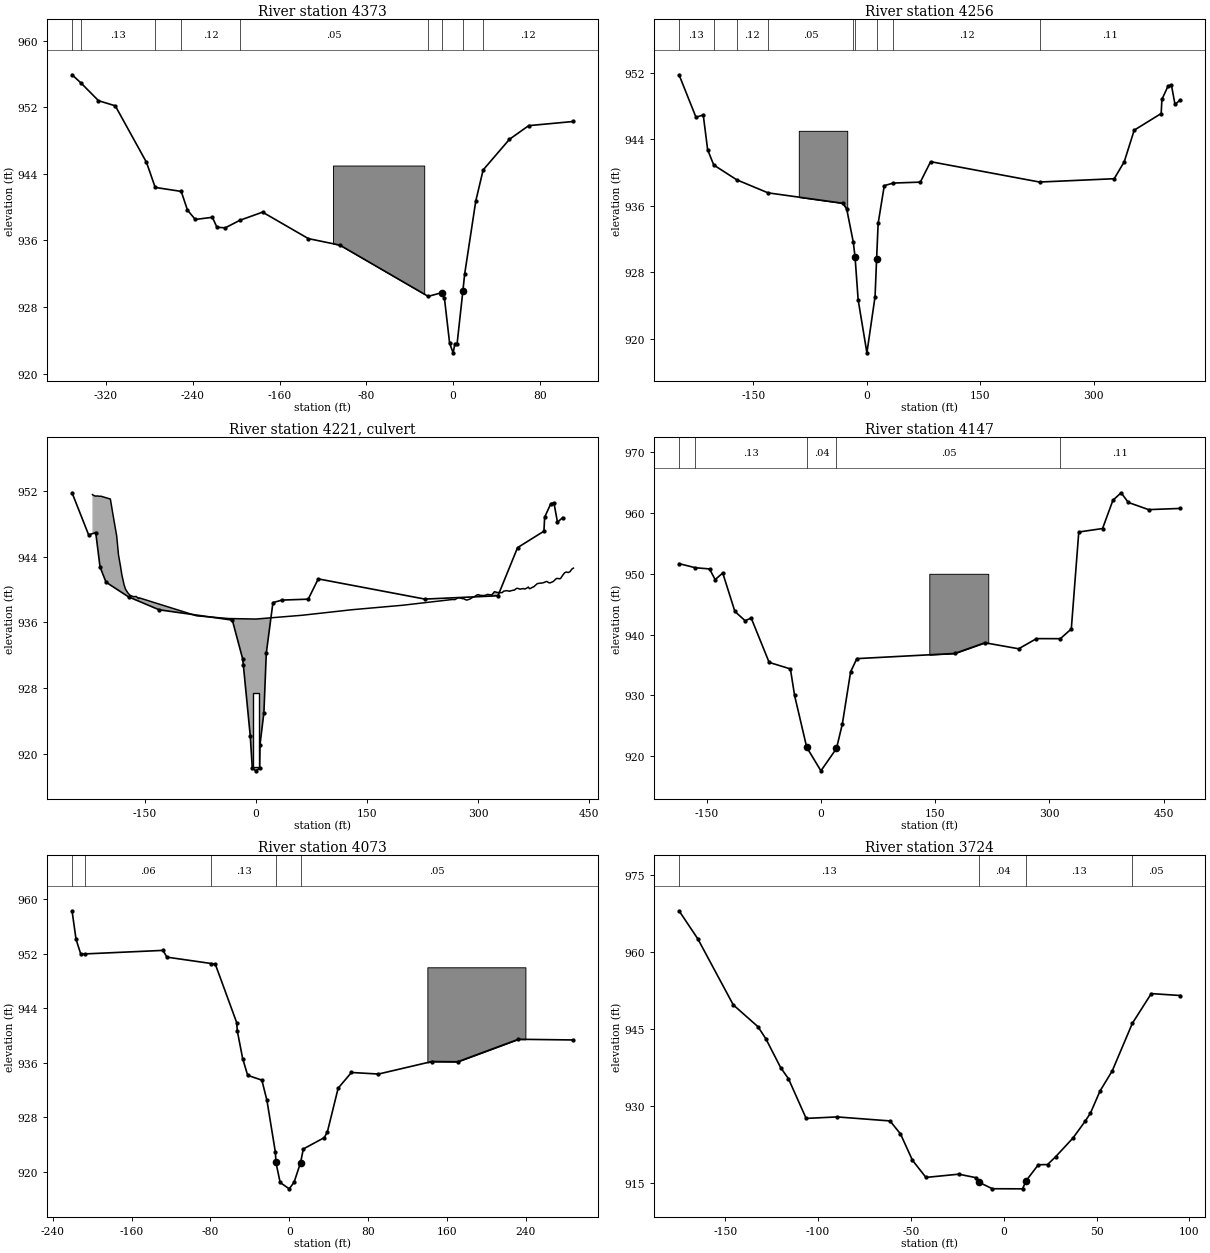
Type RM Length L Ch R = 1 ,4373    ,120.57,117,115.58
XS GIS Cut Line= 3
576421.4633719754371143.17862282576470.7830605844371184.45463933
576486.4436847784371259.38362426
#Sta/Elev= 30
-351.312   955.9 -343.11  954.92-326.936  952.79 -311.45  952.17-282.677  945.38
-274.639  942.37-250.656  941.89-244.915  939.65-237.697  938.52-221.949  938.78
-217.749  937.59-210.138  937.51-196.621  938.42-175.656   939.4-133.432  936.22
-104.429  935.44 -22.933  929.28 -10.466  929.73  -7.972  929.03  -3.215  923.65
       0   922.5   1.706  923.61   3.675  923.59       9  929.93  10.663  931.97
  20.899  940.74   27.69  944.47  51.936  948.15  69.685  949.79  110.86  950.29
#Mann= 9 ,-1 , 0
-351.312     .06       0 -343.11     .13       0-274.639     .03       0
-250.656     .12       0-196.621     .05       0 -22.933     .13       0
 -10.466    .045       0       9     .13       0   27.69     .12       0
#XS Ineff= 2 , 0
       0    -175                       0
Permanent Ineff=
       F       F
#Block Obstruct= 1 ,-1
-110.761  -26.64     945
Bank Sta=-10.466,9
XS Rating Curve= 0 ,0
Exp/Cntr=0.5,0.3

Type RM Length L Ch R = 1 ,4256    ,110.918,109,100.401
BEGIN DESCRIPTION:
US of Morgantown Avenue (Invert from survey data HIC_02)
END DESCRIPTION:
XS GIS Cut Line= 6
 576430.778060094371153.76127895576444.7470442624371179.16331126
576440.8303642144371203.92221557576444.7409482624371226.39816785
576463.7117004974371305.65531283576474.0749006254371347.96155335
#Sta/Elev= 30
-248.261  951.74-225.853  946.63-216.273  946.91-210.466  942.73-202.395  940.89
-172.014  939.11-130.643  937.54 -31.857  936.29 -26.706   935.6 -17.979  931.61
  -15.65  929.82 -11.549  924.67       0   918.3  10.794  925.07    12.8 929.576
  14.862  933.87  22.966  938.41  35.138  938.72  70.604  938.83  84.186  941.29
 228.182  938.84 326.804  939.24 340.059  941.28 353.248  945.08 388.878  947.08
 389.829  948.78  398.13  950.41 402.362  950.52 407.152  948.17 414.206  948.73
#Mann= 9 ,-1 , 0
-248.261     .13       0-202.395     .03       0-172.014     .12       0
-130.643     .05       0 -17.979     .13       0  -15.65     .04       0
    12.8     .13       0  35.138     .12       0 228.182     .11       0
#XS Ineff= 2 , 0
       0                      45       0
Permanent Ineff=
       F       F
#Block Obstruct= 1 ,-1
     -90     -26     945
Bank Sta=-15.65,12.8
XS Rating Curve= 0 ,0
Exp/Cntr=0.5,0.3

Type RM Length L Ch R = 2 ,4221    ,,,
BEGIN DESCRIPTION:
Morgantown Avenue (Surveyed Structure HIC_02)
END DESCRIPTION:
Bridge Culvert--1,0,-1,-1, 0
Deck Dist Width WeirC Skew NumUp NumDn MinLoCord MaxHiCord MaxSubmerge Is_Ogee
30,27,2.6,0, 109, 109, , , 0.98, 0, 0,0,,
-220.735-220.276-217.388-217.093-216.962-216.568-213.484-210.827-209.055-196.522
-192.815-187.959-185.564-182.841-181.037-178.051-176.706-176.083-172.769-170.276
-168.799-165.518-164.993-164.665 -161.68-159.121-158.333-157.513 -80.118 -36.975
       0  62.631 129.692 197.802 265.125 268.832 270.276 272.867 273.753 276.706
 278.839 280.512 283.858 285.367  285.63  288.78 289.239 293.537 294.652 298.228
 300.098 303.051 305.577 307.808 311.024 312.566 313.583 316.535  318.57  321.85
 322.047 323.524  326.28 327.264 330.348 332.808 334.383 338.255 338.353 338.615
 342.946 343.471 347.474 348.556 352.001 353.675 356.627 358.858 361.188 363.025
 365.354 367.946  369.16 370.407 374.344 375.033 379.462 379.626 380.807 384.055
 385.335  388.32 391.207  392.52 395.702 396.916 401.148 401.772 405.577  406.66
 410.367 411.614 414.829 416.798 419.094 421.522 424.114 426.509 428.609
  951.52  951.48  951.35  951.35  951.35  951.34  951.35  951.31  951.32  950.98
     949  946.49  944.22  942.82   941.8  940.59  940.22  940.04  939.58  939.33
  939.26  939.14  939.12  939.13  939.16  938.95   938.9  938.99  936.81  936.48
  936.42  936.88  937.55  938.09  938.79  938.78  938.86     939     939  938.95
  938.89  938.89  938.73  938.74  938.74  938.84  938.86   939.1  939.11  939.33
  939.38  939.29  939.28  939.27  939.34  939.41   939.4  939.36  939.35  939.72
  939.73  939.71  939.63  939.65  939.61  939.64   939.8  939.86  939.86  939.86
  939.79  939.83  939.92  939.91  940.14  940.14  940.04  940.09  940.12  940.05
  940.16   940.3  940.11  940.12  940.32  940.32  940.68   940.7  940.73  940.78
  940.78  940.83  940.94  940.99  940.82   940.8  940.96     941  941.33  941.35
   941.3  941.38  941.81  942.03  942.13  942.06  942.17  942.47   942.6
                                                                                
                                                                                
                                                                                
                                                                                
                                                                                
                                                                                
                                                                                
                                                                                
                                                                                
                                                                                
                                                                        
-220.735-220.276-217.388-217.093-216.962-216.568-213.484-210.827-209.055-196.522
-192.815-187.959-185.564-182.841-181.037-178.051-176.706-176.083-172.769-170.276
-168.799-165.518-164.993-164.665 -161.68-159.121-158.333-157.513 -80.118 -36.975
       0  62.631 129.692 197.802 265.125 268.832 270.276 272.867 273.753 276.706
 278.839 280.512 283.858 285.367  285.63  288.78 289.239 293.537 294.652 298.228
 300.098 303.051 305.577 307.808 311.024 312.566 313.583 316.535  318.57  321.85
 322.047 323.524  326.28 327.264 330.348 332.808 334.383 338.255 338.353 338.615
 342.946 343.471 347.474 348.556 352.001 353.675 356.627 358.858 361.188 363.025
 365.354 367.946  369.16 370.407 374.344 375.033 379.462 379.626 380.807 384.055
 385.335  388.32 391.207  392.52 395.702 396.916 401.148 401.772 405.577  406.66
 410.367 411.614 414.829 416.798 419.094 421.522 424.114 426.509 428.609
  951.52  951.48  951.35  951.35  951.35  951.34  951.35  951.31  951.32  950.98
     949  946.49  944.22  942.82   941.8  940.59  940.22  940.04  939.58  939.33
  939.26  939.14  939.12  939.13  939.16  938.95   938.9  938.99  936.81  936.48
  936.42  936.88  937.55  938.09  938.79  938.78  938.86     939     939  938.95
  938.89  938.89  938.73  938.74  938.74  938.84  938.86   939.1  939.11  939.33
  939.38  939.29  939.28  939.27  939.34  939.41   939.4  939.36  939.35  939.72
  939.73  939.71  939.63  939.65  939.61  939.64   939.8  939.86  939.86  939.86
  939.79  939.83  939.92  939.91  940.14  940.14  940.04  940.09  940.12  940.05
  940.16   940.3  940.11  940.12  940.32  940.32  940.68   940.7  940.73  940.78
  940.78  940.83  940.94  940.99  940.82   940.8  940.96     941  941.33  941.35
   941.3  941.38  941.81  942.03  942.13  942.06  942.17  942.47   942.6
                                                                                
                                                                                
                                                                                
                                                                                
                                                                                
                                                                                
                                                                                
                                                                                
                                                                                
                                                                                
                                                                        
BR Coef=-1 , 0 , 0 ,, 0 ,,,0.8,-1,,0,
WSPro=,,,, 1 ,,,, 0 ,,,, 0 ,,,,-1 ,-1 ,-1 , 0 , 0 , 0 , 0 , 0
Culvert=2,9,8,75.7,0.0125,0.5,1,58,2,918.42,0,917.95,0,Culvert #1  , 0 ,12
Culvert Bottom n=0.0125
BR U #Sta/Elev= 30
-248.261  951.74-225.853  946.63-216.273  946.91-210.466  942.73-202.395  940.89
-172.014  939.11-130.643  937.54 -31.857  936.29 -17.979  931.61 -17.028  930.88
  -7.644  922.24  -4.888  918.32       0     918   5.052  918.32   5.512  921.19
  10.794  925.07      14 932.271  22.966  938.41  35.138  938.72  70.604  938.83
  84.186  941.29 228.182  938.84 326.804  939.24 353.248  945.08 388.878  947.08
 389.829  948.78  398.13  950.41 402.362  950.52 407.152  948.17 414.206  948.73
BR U #Mann= 9
-248.261     .13-202.395     .03-172.014     .12-130.643     .05 -17.979     .13
 -17.028    .045      14     .13  35.138     .12 228.182     .11
BR U Banks=,14
BR D #Sta/Elev= 30
-186.352  951.67-164.731  950.99-146.293   950.8-138.911  949.04 -128.97  950.13
-112.992  943.81 -91.568  942.73 -68.012  935.43 -40.092  934.36  -34.58  929.99
 -18.668  921.47 -16.109   919.4       0  917.69  10.892  918.08   20.44  921.28
   28.15  925.32  39.009  933.89  47.211  936.05 175.525   936.9 215.354  938.66
 259.711  937.67 283.071  939.34 314.436  939.33 328.839  940.93 338.648  956.87
 369.882  957.44 383.465  962.08 394.226  963.32 430.381  960.55 472.047  960.75
BR D #Mann= 5
-186.352     .06-164.731     .13 -18.668    .045   20.44     .05 314.436     .11
BC Design=,, 0 ,, 0 ,,,,,,
BC Use User HTab Curves=0
BC User HTab FreeFlow(D)= 0

Type RM Length L Ch R = 1 ,4147    ,78.42,74,70.4
BEGIN DESCRIPTION:
DS of Morgantown Avenue
END DESCRIPTION:
XS GIS Cut Line= 6
576409.6096998284371159.89995103576415.9373479064371172.89357519
576411.4750758514371204.38246358576416.3244439114371232.26556792
576435.5237961484371312.47978491576445.9083322774371354.86222544
#Sta/Elev= 30
-186.352  951.67-164.731  950.99-146.293   950.8-138.911  949.04 -128.97  950.13
-112.992  943.81 -99.508  942.28 -91.568  942.73 -68.012  935.43 -40.092  934.36
  -34.58  929.99 -18.668  921.47       0   917.6   20.44  921.28   28.15  925.32
  39.009  933.89  47.211  936.05 175.525   936.9 215.354  938.66 259.711  937.67
 283.071  939.34 314.436  939.33 328.839  940.93 338.648  956.87 369.882  957.44
 383.465  962.08 394.226  963.32  403.74  961.73 430.381  960.55 472.047  960.75
#Mann= 5 ,-1 , 0
-186.352     .06       0-164.731     .13       0 -18.668     .04       0
   20.44     .05       0 314.436     .11       0
#XS Ineff= 2 , 0
       0                      45       0
Permanent Ineff=
       F       F
#Block Obstruct= 1 ,-1
 142.323 219.751     950
Bank Sta=-18.668,20.44
XS Rating Curve= 0 ,0
Exp/Cntr=0.5,0.3

Type RM Length L Ch R = 1 ,4073    ,333.24,349,369.8
XS GIS Cut Line= 2
576374.0486833894371148.89362289576412.5723558654371299.17831275
#Sta/Elev= 30
-220.505  958.29-216.437  954.09-211.614  951.93 -207.71  951.96-128.117  952.48
-124.245  951.49  -78.97  950.55     -75  950.44 -53.346  941.89  -52.69  940.66
 -47.277  936.62 -42.192  934.15 -27.789  933.45 -22.638  930.49     -14 922.836
   -13.5 921.373  -9.186  918.43       0   917.5   4.954  918.47    11.5 921.336
  14.337  923.35  35.597  925.01   38.78  925.87  49.705  932.27  63.189  934.57
  90.617  934.34 144.718  936.17 171.063  936.14 232.677  939.44 288.517  939.34
#Mann= 5 ,-1 , 0
-220.505     .13       0 -207.71     .06       0  -78.97     .13       0
   -13.5     .04       0    11.5     .05       0
#Block Obstruct= 2 ,-1
-184.711-126.837     950 140.289 239.829     950
Bank Sta=-13.5,11.5
XS Rating Curve= 0 ,0
Exp/Cntr=0.3,0.1

Type RM Length L Ch R = 1 ,3724    ,358.46,369,378.84
XS GIS Cut Line= 2
576302.2957145024371169.21463914576275.836026175 4371247.1062801
#Sta/Elev= 30
-174.836  967.98-164.764  962.55-145.636  949.69-132.316  945.44-128.018  943.05
-120.112  937.49-115.945  935.35-106.398  927.62 -89.698  927.91 -61.253  927.13
  -55.61  924.61 -49.147  919.48 -41.896  916.15 -24.213  916.78 -14.993   916.1
 -13.123  915.17  -6.168  913.95  10.138  913.93  12.008  915.49  18.602  918.61
  23.556  918.65  27.887  920.15   37.27  923.81  43.766  927.04  46.654  928.63
  51.804  932.93  58.432  936.88  69.259  946.12  79.429  951.88  95.079  951.51
#Mann= 4 ,-1 , 0
-174.836     .13       0 -13.123     .04       0  12.008     .13       0
  69.259     .05       0
Bank Sta=-13.123,12.008
XS Rating Curve= 0 ,0
Exp/Cntr=0.3,0.1

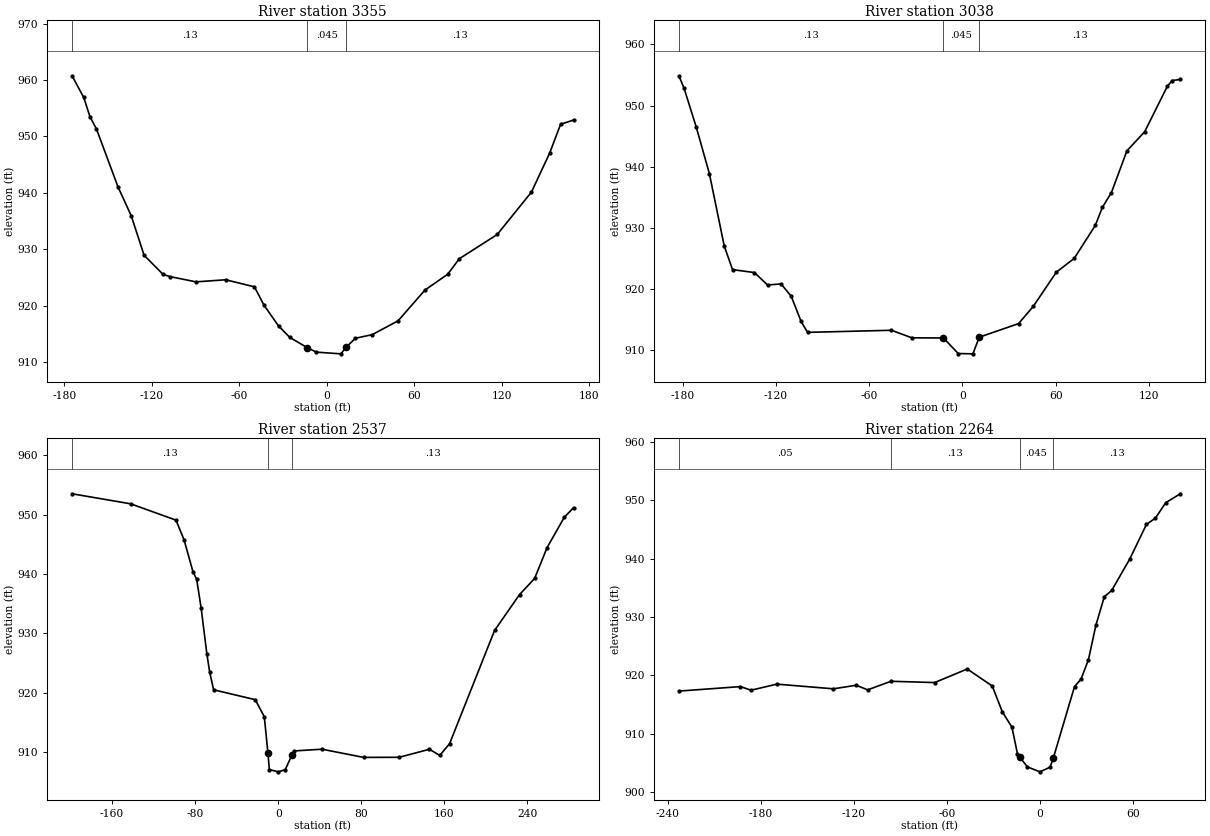
Type RM Length L Ch R = 1 ,3355    ,297.03,317,307.06
XS GIS Cut Line= 3
576232.8683696444371139.36862277576192.4396971444371184.87831134
576177.1996969564371226.15127985
#Sta/Elev= 30
-174.705  960.76-166.732  956.94-162.336  953.45-157.972  951.34-143.176  941.07
-134.088  935.94-125.295  928.95 -112.27  925.56-107.513  925.16 -89.633  924.23
 -69.324   924.6 -49.573  923.35 -43.012   920.1 -33.005  916.41 -25.328  914.39
 -13.287  912.56  -7.021  911.77   9.744  911.47  13.287  912.61  19.685  914.23
  31.266  914.87  49.016  917.32  67.454  922.78  83.071  925.58  90.978  928.32
  117.06  932.63 140.518  940.14 153.051  947.07 160.531  952.17  169.39  952.91
#Mann= 3 ,-1 , 0
-174.705     .13       0 -13.287    .045       0  13.287     .13       0
Bank Sta=-13.287,13.287
XS Rating Curve= 0 ,0
Exp/Cntr=0.3,0.1

Type RM Length L Ch R = 1 ,3038    ,488.63,501,497.05
XS GIS Cut Line= 2
576138.8863364824371118.20331051576105.4436800694371210.70096765
#Sta/Elev= 30
 -182.48  954.87-179.134  952.83-171.325  946.51-162.861  938.89-153.314  927.09
-147.966   923.2-133.858  922.72-125.427  920.69-116.732  920.86-110.203  918.86
-103.839  914.74 -99.672  912.95 -45.702  913.29 -32.579  912.06 -12.205  912.03
  -2.723  909.49   6.726  909.44  10.827  912.16  36.122  914.38  45.538  917.18
  60.433  922.78  71.949  925.04  85.499  930.42  90.026  933.36  95.866  935.79
 105.873  942.62 117.224  945.71 131.923  953.19 134.974  954.09 140.223  954.27
#Mann= 3 ,-1 , 0
 -182.48     .13       0 -12.205    .045       0  10.827     .13       0
Bank Sta=-12.205,10.827
XS Rating Curve= 0 ,0
Exp/Cntr=0.3,0.1

Type RM Length L Ch R = 1 ,2537    ,252.21,273,275.03
XS GIS Cut Line= 4
576032.2063351644371045.81026162576007.700414861 4371060.6448778
575995.2676227074371123.87868658576003.7319188124371177.32536724
#Sta/Elev= 30
-198.622  953.51-142.126  951.82 -98.524  949.07  -90.65  945.71 -82.185  940.39
 -78.576  939.09 -74.344  934.34 -68.734  926.48 -66.043  923.47  -62.27  920.51
 -22.211  918.85 -13.451  915.98     -10 909.921  -8.629  907.09       0   906.7
   6.726  907.07  13.123  909.52  15.387  910.22  42.028  910.51  82.283  909.13
  116.47  909.15 145.571   910.5 155.545  909.46 164.993  911.44 208.301   930.5
 232.415  936.55 246.883  939.25 258.891  944.45 275.492  949.56  284.35  951.16
#Mann= 3 ,-1 , 0
-198.622     .13       0     -10    .045       0  13.123     .13       0
Bank Sta=-10,13.123
XS Rating Curve= 0 ,0
Exp/Cntr=0.3,0.1

Type RM Length L Ch R = 1 ,2264    ,78.7,107,123.52
XS GIS Cut Line= 2
575956.4300062274371066.97862188575932.0886779264371162.43893506
#Sta/Elev= 30
 -232.71  917.32-193.012  918.09 -186.22  917.47-169.554  918.51-133.136  917.71
-118.406  918.32-111.024  917.53 -95.997     919 -67.848  918.78  -46.85   921.1
 -30.709  918.19 -24.213  913.75 -18.045  911.15 -14.469  906.59 -13.156  906.09
  -8.104  904.35       0   903.5   6.562   904.3   8.727  905.94   22.31  918.09
  26.476  919.35  31.266  922.67  36.089   928.6  41.503  933.46   46.26  934.54
   57.94  939.94  68.668  945.85  74.475  946.93  81.102  949.57  90.518  951.09
#Mann= 4 ,-1 , 0
 -232.71     .05       0 -95.997     .13       0 -13.156    .045       0
   8.727     .13       0
Bank Sta=-13.156,8.727
XS Rating Curve= 0 ,0
Exp/Cntr=0.3,0.1