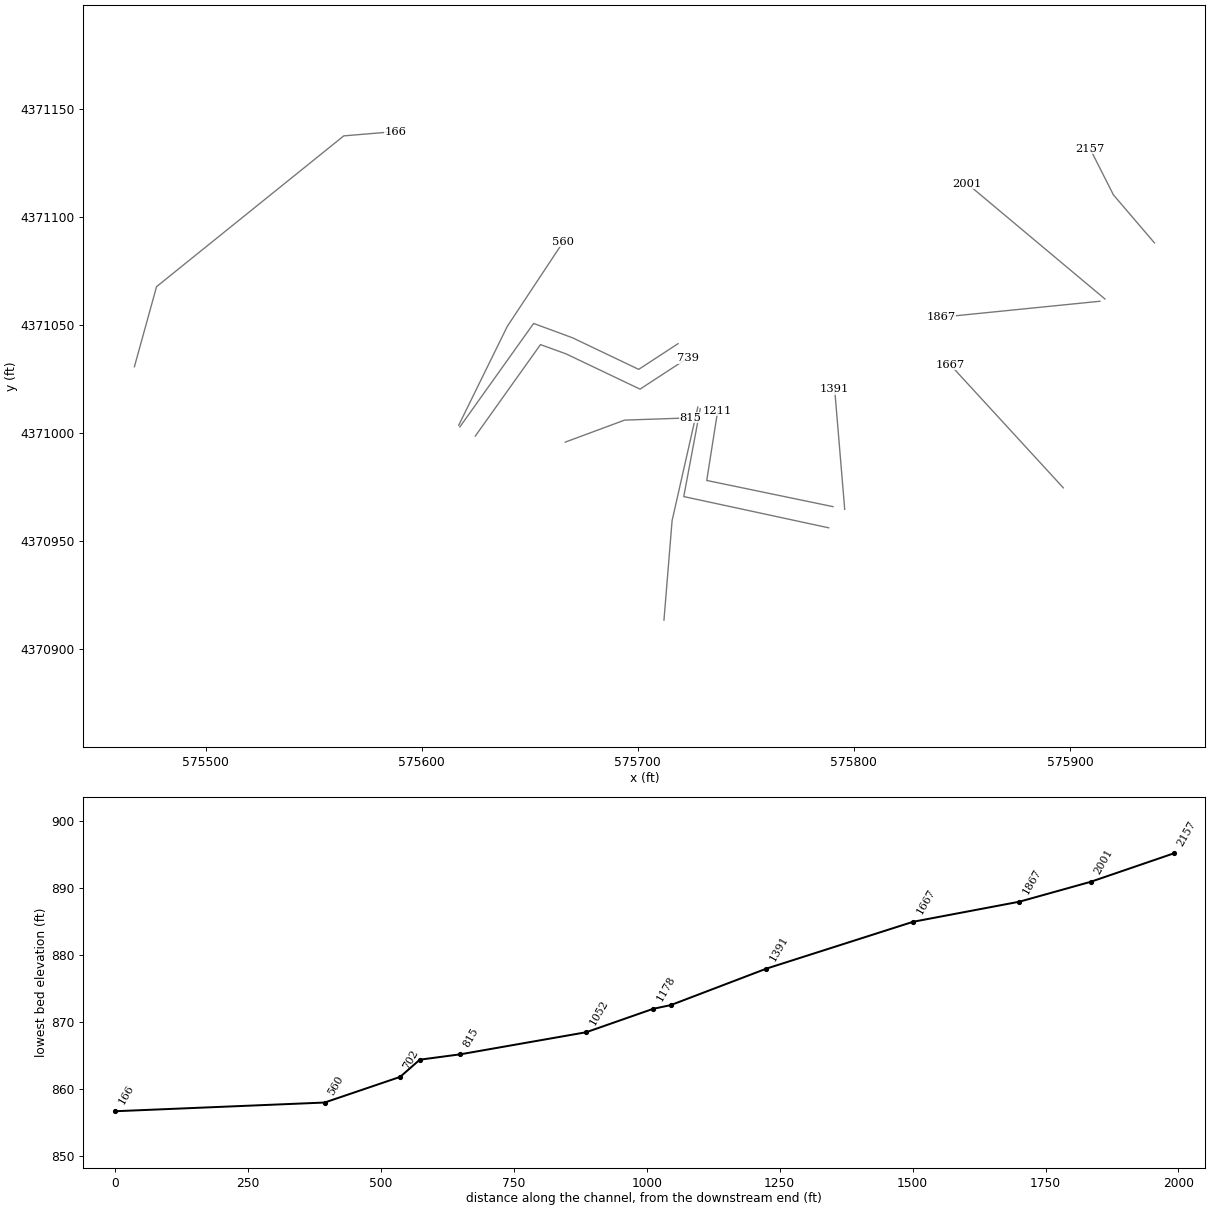
HEC-RAS study HickmanRun.prj: Hickman Run

--- HickmanRun.g02 (geometry) --- (continued)

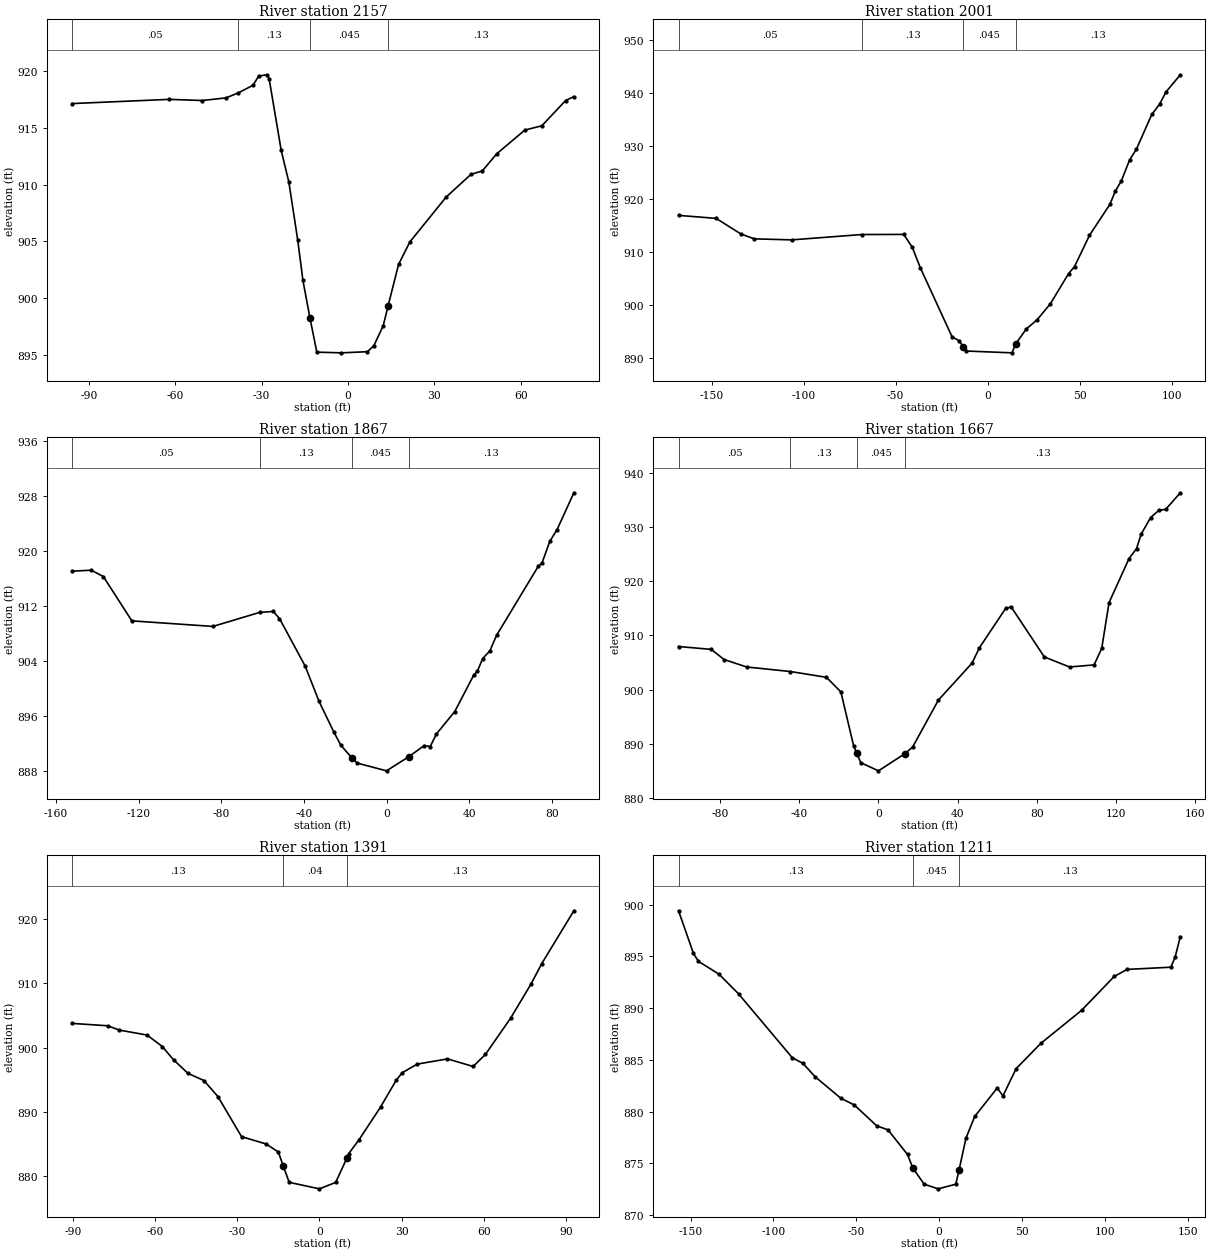
Type RM Length L Ch R = 1 ,2157    ,151.66,156,167.05
XS GIS Cut Line= 3
575939.1234620134371088.08602214575920.1557577794371110.28460641
575909.3566936454371131.60841468
#Sta/Elev= 30
 -95.801  917.11 -62.106  917.48 -50.591  917.38 -42.356  917.61 -38.156  918.04
 -32.972  918.72 -31.004  919.53 -28.084  919.64 -27.395  919.31 -23.196     913
 -20.538  910.22 -17.454  905.11  -15.65  901.57 -13.189  898.24 -10.827  895.27
  -2.264  895.21   6.759  895.31   8.957  895.83  12.238   897.6  13.944  899.36
  17.552  902.98   21.49  904.96  34.088   908.9  42.684  910.89  46.621  911.19
   51.64   912.7  61.385  914.78   67.29  915.16  75.558  917.38  78.412  917.72
#Mann= 4 ,-1 , 0
 -95.801     .05       0 -38.156     .13       0 -13.189    .045       0
  13.944     .13       0
Bank Sta=-13.189,13.944
XS Rating Curve= 0 ,0
Exp/Cntr=0.3,0.1

Type RM Length L Ch R = 1 ,2001    ,112.91,134,155.09
XS GIS Cut Line= 2
 575916.214693734371062.11096582575852.5023489434371115.45096648
#Sta/Elev= 30
-167.979  916.95-147.572  916.38-134.121  913.44-126.804  912.51 -106.43  912.32
 -68.373  913.33 -45.604  913.35  -41.01  910.92 -36.614  907.04 -19.324  893.96
 -15.715  893.29 -13.287  892.16 -11.614  891.31  13.189  890.97  15.092  892.61
  20.932  895.48  26.706  897.18   33.99  900.22  43.898  905.93  47.146  907.27
  55.282  913.18  66.404  919.05  69.291  921.51  72.605  923.48    77.1  927.45
  80.741  929.44   89.14  936.03  93.406  937.99  96.883   940.3 104.626  943.52
#Mann= 4 ,-1 , 0
-167.979     .05       0 -68.373     .13       0 -13.287    .045       0
  15.092     .13       0
Bank Sta=-13.287,15.092
XS Rating Curve= 0 ,0
Exp/Cntr=0.3,0.1

Type RM Length L Ch R = 1 ,1867    ,224.99,200,174.09
XS GIS Cut Line= 2
575913.886021701 4371061.0502618575840.2250047914371053.64362171
#Sta/Elev= 30
-152.198  917.09-142.913  917.23-137.073  916.31-123.261  909.85 -84.055  909.04
 -61.417  911.08 -54.823  911.22 -51.804  910.19 -39.403  903.28 -32.677  898.14
 -25.591  893.71 -22.047   891.7 -16.765  889.89 -14.075  889.12       0     888
  10.892  890.08  18.274  891.69  21.161  891.53  24.114  893.36  33.038  896.64
  42.159  901.91  43.963   902.5  46.555  904.36  50.066  905.49  53.248  907.73
  73.458   917.8  75.295  918.31  79.068  921.45  82.579  923.16  90.682  928.51
#Mann= 4 ,-1 , 0
-152.198     .05       0 -61.417     .13       0 -16.765    .045       0
  10.892     .13       0
Bank Sta=-16.765,10.892
XS Rating Curve= 0 ,0
Exp/Cntr=0.3,0.1

Type RM Length L Ch R = 1 ,1667    ,293.84,276,259.08
XS GIS Cut Line= 2
575896.9513334924370974.69127674575844.6689888464371031.63096544
#Sta/Elev= 30
 -101.05  907.96 -84.514  907.43 -78.051  905.56 -66.634  904.18 -44.488  903.34
  -26.28  902.27 -18.996  899.57 -12.566  889.63     -11 888.276  -8.957  886.51
       0     885  13.189  888.13  17.257  889.39  30.315  898.08   47.31   904.9
  51.017  907.73  64.239  914.98   67.06  915.28  83.825  906.03  96.555  904.18
 108.957  904.56 112.828  907.61 116.535  916.06  126.64   924.2 130.446  926.05
  132.71  928.67 137.533  931.77 141.634  933.09 145.144  933.29 152.559  936.35
#Mann= 4 ,-1 , 0
 -101.05     .05       0 -44.488     .13       0     -11    .045       0
  13.189     .13       0
Bank Sta=-11,13.189
XS Rating Curve= 0 ,0
Exp/Cntr=0.3,0.1

Type RM Length L Ch R = 1 ,1391    ,135.36,180,233.5
XS GIS Cut Line= 2
575795.7760202424370964.74260461575791.118676184 4371020.4112773
#Sta/Elev= 30
 -90.354  903.77 -77.362   903.4 -73.097  902.73 -62.927  901.95 -57.415  900.17
 -53.281   898.1 -48.031  895.99 -42.192  894.87 -37.073  892.37 -28.445  886.13
 -19.488  884.99 -14.993  883.74 -13.156  881.48 -11.024  879.01       0     878
   5.938     879      10 882.752  10.696  883.49  14.337  885.56  22.343  890.75
  28.084  894.94  30.282   896.1  35.761  897.43  46.785  898.24  56.168  897.06
  60.663  898.95  69.849  904.59  77.198  909.83  81.201  913.07  92.946  921.31
#Mann= 3 ,-1 , 0
 -90.354     .13       0 -13.156     .04       0      10     .13       0
Bank Sta=-13.156,10
XS Rating Curve= 0 ,0
Exp/Cntr=0.5,0.3

Type RM Length L Ch R = 1 ,1211    ,34.375,33,33.823
BEGIN DESCRIPTION:
US of Private drive (Invert from survey data HIC_01A)
END DESCRIPTION:
XS GIS Cut Line= 3
575790.3780121754370965.98009263575731.9143234524370978.11113278
575736.9953395154371010.33763718
#Sta/Elev= 30
-157.283   899.4-148.261  895.28-145.243  894.51-132.874  893.28-121.063  891.38
 -88.615  885.21 -82.152  884.66 -74.803  883.37 -59.252  881.29 -51.181  880.65
 -37.598  878.63 -30.873  878.25 -19.062  875.87 -15.879  874.57      -9     873
   -.525  872.55  10.105     873  12.008  874.33  16.207  877.43  21.522  879.54
  35.072  882.28  38.583  881.53   46.49  884.15  61.352  886.59  85.991  889.78
 105.741  893.06 113.517  893.74 139.928  893.95 142.487  894.92 145.636  896.91
#Mann= 3 ,-1 , 0
-157.283     .13       0 -15.879    .045       0  12.008     .13       0
Bank Sta=-15.879,12.008
XS Rating Curve= 0 ,0
Exp/Cntr=0.5,0.3

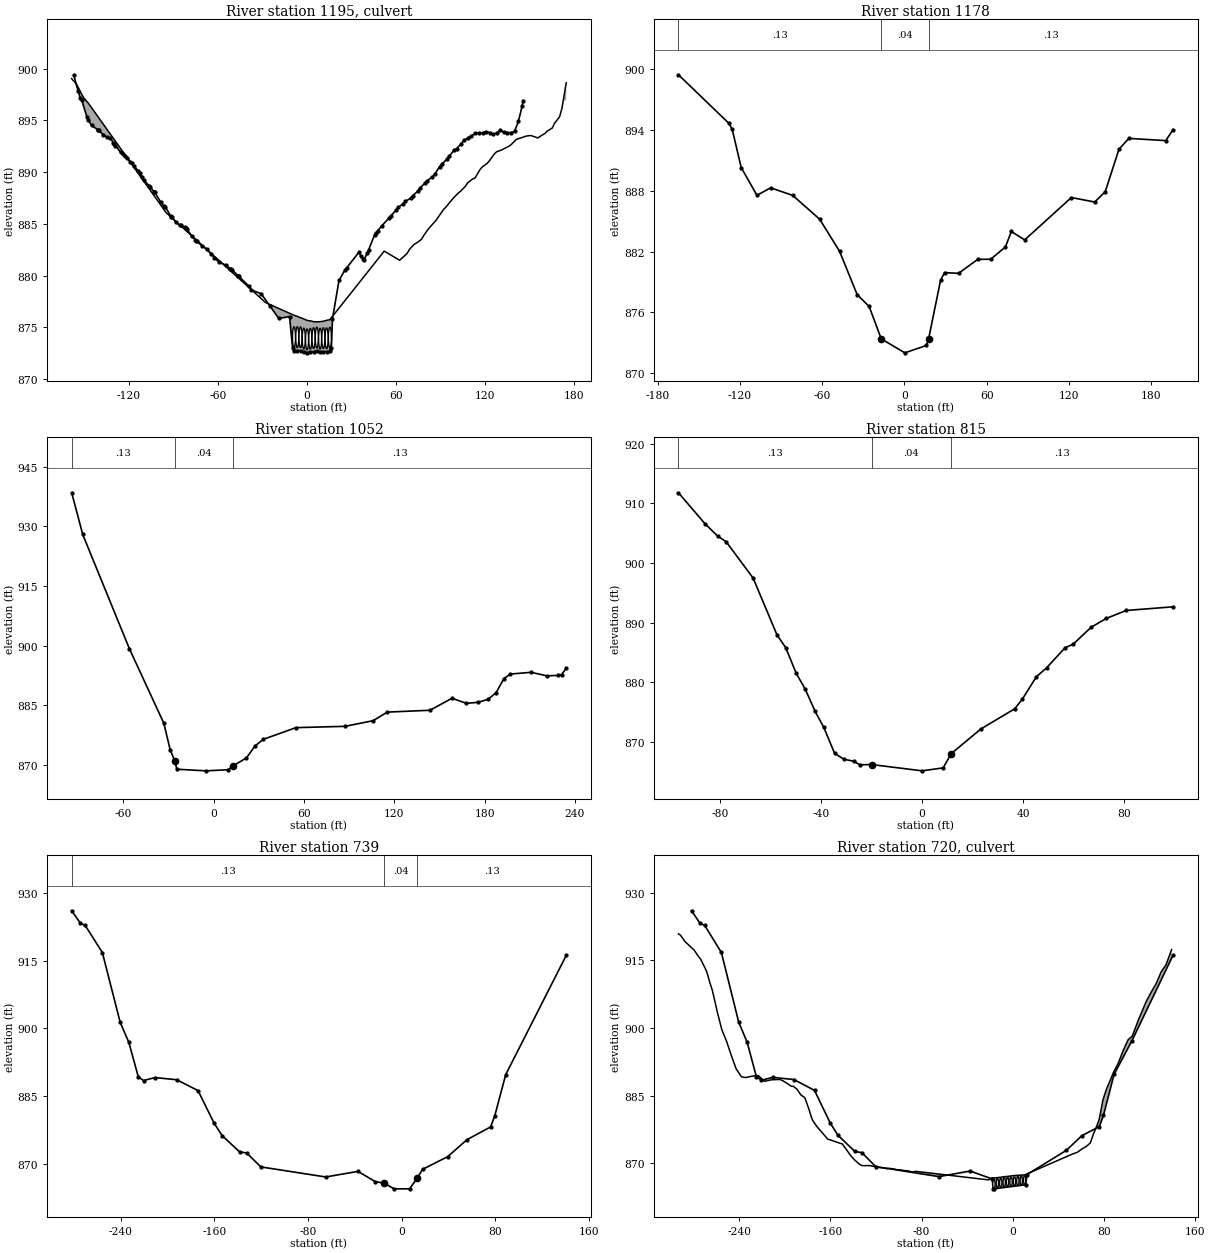
Type RM Length L Ch R = 2 ,1195    ,,,
BEGIN DESCRIPTION:
Private drive (Surveyed Structure HIC_01A)
END DESCRIPTION:
Bridge Culvert--1,0,-1,-1, 0
Deck Dist Width WeirC Skew NumUp NumDn MinLoCord MaxHiCord MaxSubmerge Is_Ogee
8,19.7,2.6,0, 70, 70, , , 0.98, 0, 0,0,,
-158.629 -157.94 -156.89-154.954-152.067-150.361-148.064-147.507     -95     -28
    -8.8    -6.6    -4.4    -2.2       0     2.2     4.4     6.6     8.8      11
    13.2    15.4      52  62.434  64.239  67.356  69.127  72.244  74.016  77.133
  78.904  82.119  83.825  87.008  88.681  91.929  93.602   96.85  98.524 101.772
 103.412 106.726 108.301 111.647 113.222  116.47 118.045 121.325 122.933  126.28
 127.822 131.201  132.71 136.056 137.598 140.978 142.552 145.833 147.343 150.689
 152.231 155.545 157.087 160.367 161.942 165.289 166.831 170.177 171.752 174.705
  899.03  898.89  898.75  898.38  897.56  897.14  896.76  896.68  886.09  877.41
  876.18  876.07  875.94  875.83  875.68  875.64  875.56  875.54  875.56   875.6
  875.69  875.76  882.37  881.49  881.73  882.13  882.56  883.03  883.18  883.51
  883.94  884.57  884.85  885.35  885.71  886.38  886.63  887.19  887.48  887.96
  888.15  888.63  888.98  889.34  889.43  890.22   890.5  890.83   891.1  891.76
  891.97  892.14  892.26   892.5  892.66  893.15  893.24  893.38  893.47  893.54
  893.47   893.3  893.45  893.74  893.97  894.26  894.72  895.33  896.12  898.63
                                                                                
                                                                                
                                                                                
                                                                                
                                                                                
                                                                                
                                                                                
-158.629 -157.94 -156.89-154.954-152.067-150.361-148.064-147.507     -95     -28
    -8.8    -6.6    -4.4    -2.2       0     2.2     4.4     6.6     8.8      11
    13.2    15.4      52  62.434  64.239  67.356  69.127  72.244  74.016  77.133
  78.904  82.119  83.825  87.008  88.681  91.929  93.602   96.85  98.524 101.772
 103.412 106.726 108.301 111.647 113.222  116.47 118.045 121.325 122.933  126.28
 127.822 131.201  132.71 136.056 137.598 140.978 142.552 145.833 147.343 150.689
 152.231 155.545 157.087 160.367 161.942 165.289 166.831 170.177 171.752 174.705
  899.03  898.89  898.75  898.38  897.56  897.14  896.76  896.68  886.09  877.41
  876.18  876.07  875.94  875.83  875.68  875.64  875.56  875.54  875.56   875.6
  875.69  875.76  882.37  881.49  881.73  882.13  882.56  883.03  883.18  883.51
  883.94  884.57  884.85  885.35  885.71  886.38  886.63  887.19  887.48  887.96
  888.15  888.63  888.98  889.34  889.43  890.22   890.5  890.83   891.1  891.76
  891.97  892.14  892.26   892.5  892.66  893.15  893.24  893.38  893.47  893.54
  893.47   893.3  893.45  893.74  893.97  894.26  894.72  895.33  896.12  898.63
                                                                                
                                                                                
                                                                                
                                                                                
                                                                                
                                                                                
                                                                                
BR Coef=-1 , 0 , 0 ,, 0 ,,,0.8,-1,,0,
WSPro=,,,, 1 ,,,, 0 ,,,, 0 ,,,,-1 ,-1 ,-1 , 0 , 0 , 0 , 0 , 0
Multiple Barrel Culv=1,2,,19.6,0.0125,0.5,1,1,1,873.06,873.02, 3,Culvert #1  , 0 ,8
    -8.8    -8.8    -6.6    -6.6    -4.4    -4.4
Culvert Bottom n=0.0125
Culvert=1,2,,19.6,0.0125,0.5,1,1,1,872.93,-2.2,872.89,-2.2,Culvert #4  , 0 ,8
Culvert Bottom n=0.0125
Culvert=1,2,,19.6,0.0125,0.5,1,1,1,872.85,0,872.76,0,Culvert #5  , 0 ,8
Culvert Bottom n=0.0125
Culvert=1,2,,19.6,0.0125,0.5,1,1,1,872.91,2.2,872.76,2.2,Culvert #6  , 0 ,8
Culvert Bottom n=0.0125
Culvert=1,2,,19.6,0.0125,0.5,1,1,1,872.97,4.4,872.67,4.4,Culvert #7  , 0 ,8
Culvert Bottom n=0.0125
Culvert=1,2,,19.6,0.0125,0.5,1,1,1,873.02,6.6,872.76,6.6,Culvert #8  , 0 ,8
Culvert Bottom n=0.0125
Culvert=1,2,,19.6,0.0125,0.5,1,1,1,872.92,8.8,872.76,8.8,Culvert #9  , 0 ,8
Culvert Bottom n=0.0125
Culvert=1,2,,19.6,0.0125,0.5,1,1,1,872.97,11,872.76,11,Culvert #10 , 0 ,8
Culvert Bottom n=0.0125
Culvert=1,2,,19.6,0.0125,0.5,1,1,1,872.95,13.2,872.76,13.2,Culvert #11 , 0 ,8
Culvert Bottom n=0.0125
Culvert=1,2,,19.6,0.0125,0.5,1,1,1,873.02,15.4,872.76,15.4,Culvert #12 , 0 ,8
Culvert Bottom n=0.0125
BR U #Sta/Elev= 133
-157.283   899.4-154.364  897.85-152.822  897.14-151.903  896.95-148.261  895.28
 -147.31  895.02-145.243  894.51-140.912  894.08-140.584  894.07-140.387  894.03
-137.467  893.61-135.138  893.38-132.874  893.28-130.512  892.85-129.921   892.7
-129.167  892.56-125.722  891.91-124.213  891.74  -122.9  891.53-121.063  891.38
-119.226  891.01-118.274  890.87-116.535  890.55-113.944  890.15 -112.73  889.87
-111.286  889.56-110.007  889.21-106.529   888.7-106.004  888.58-102.986  888.09
-102.887  888.06-102.657  888.05 -98.655  887.11 -96.325   886.7 -95.571  886.67
 -91.896  885.74 -91.601   885.7 -91.273  885.66 -88.615  885.21 -85.892  884.86
 -84.678  884.85 -82.152  884.66 -81.759  884.57 -80.709  884.46 -77.756  883.84
 -75.394  883.47 -74.803  883.37 -74.344  883.34 -70.472  882.84  -67.52  882.55
 -64.895  882.13   -62.5  881.73 -59.252  881.29 -54.528  881.01 -51.772  880.68
 -51.181  880.65  -50.82  880.59 -46.457     880 -46.293  879.98 -45.932  879.93
 -39.009  878.96 -37.598  878.63 -30.873  878.25 -24.869  877.04 -19.062  875.87
   -11.8  876.05    -9.8  873.06    -8.8  872.76    -6.6  872.76    -4.4  872.76
    -2.2  872.63       0  872.55     2.2  872.61     4.4  872.67     6.6  872.72
     8.8  872.62      11  872.67    13.2  872.65    15.4  872.72    16.4  873.02
   17.15  875.83  21.522  879.54  25.689  880.58   26.64  880.75  35.072  882.28
  36.319  881.87  37.992  881.64  38.583  881.53  40.584  882.23  41.503  882.49
  45.505  883.94   46.49  884.15  47.507  884.31  50.295   884.8  55.249  885.57
  56.365  885.75  60.138  886.35  61.352  886.59  64.993  886.97  66.306  887.18
  69.882  887.49   71.26  887.73  74.738  888.17  76.148  888.46   79.56  888.96
   81.07  889.18  84.383  889.55  85.991  889.78  89.304  890.52  90.978  890.79
  94.094  891.23  95.866  891.54   98.95  892.09 100.787  892.27 103.806  892.72
 105.741  893.06 108.694  893.32 110.663   893.5 113.517  893.74 115.584  893.78
 118.373   893.8  120.44  893.91 123.163  893.82 125.295  893.65 128.018   893.8
 130.217  894.02 132.841  893.84 135.072  893.81 137.631  893.81 139.928  893.95
 142.487  894.92  144.98  896.37 145.636  896.91
BR U #Mann= 3
-157.283     .13   -11.8     .04   17.15     .13
BR U Banks=-11.8,17.15
BR D #Sta/Elev= 163
-164.829  899.45-162.008  898.76-161.909  898.75-160.827   898.6-157.316  898.15
-157.119  898.14-154.396  898.11-152.034  897.98-149.672  897.79-148.261  897.53
-146.588  897.14 -145.21  896.98-141.929  896.44-139.862  896.22-139.042  896.18
-137.533  896.11-134.777  895.86-132.907   895.6 -130.84  894.98-128.281   894.7
-127.986  894.65-125.623  894.06 -121.85  891.83-121.752   891.8-121.621  891.73
-119.029  890.28-116.962  889.66-114.961   889.4-113.058   889.2-111.909  888.74
-108.793  887.81-107.579  887.55-106.037  887.57 -104.56  887.64 -103.97  887.69
-100.591  888.16 -98.917  888.27 -97.605  888.29 -96.588  888.25 -93.635  888.06
 -92.192  888.01 -90.814  887.74 -86.778  887.47 -86.745  887.47 -83.825   887.4
 -81.562  887.55 -79.462  887.41 -77.887   887.3 -76.115  886.98 -72.736  886.68
 -71.457  886.61 -70.702  886.49  -68.34  886.27  -65.65  885.82 -63.484  885.42
 -61.811  885.19 -60.171  884.74 -59.514   884.5 -55.381  883.87 -54.396  883.69
  -47.31  882.03 -47.047  881.93 -46.883  881.86 -43.898  880.91 -39.633  879.43
 -39.009  879.16 -38.845  879.11 -35.597  878.04 -34.482  877.75 -30.741  877.24
 -28.937  877.03 -25.722  876.58 -22.933  875.59 -21.227  874.83   -11.8     875
    -8.8   872.2    -2.2   872.2    .328  872.55   8.366  872.57  12.992  872.51
  16.109  872.73  17.684   873.4  20.079  874.56  22.408  876.27  26.115  878.97
  26.411  879.17  26.903  879.33  29.265  879.92  30.151  879.96  33.038  879.62
  34.482  879.76  35.827  879.71  37.402  879.79  39.501  879.85   40.65  880.03
  42.257  880.16  44.127  880.14  46.358  880.19   48.72  880.46  49.541  880.55
  50.558   880.6   53.51  881.23  54.724  881.09  56.824  880.92  59.219  881.12
  60.302  881.14  62.598  881.23  62.959  881.24  63.222   881.3  67.749  881.87
  68.209  881.93  72.539  882.41  73.294  882.39  73.688  882.45  78.018  883.98
  82.185  883.97   82.94  883.95  86.877  883.09  87.762  883.15  91.699  883.85
  92.684  883.95  96.457  884.22  97.572  884.33  101.28  885.06 102.493  885.22
  106.07  885.38 107.415  885.61 110.958  886.08 112.402  886.29 115.715  886.64
 117.257  886.86 120.505  887.24 121.785  887.33 123.885  887.41 127.034  887.11
 128.773  886.93 132.776  886.75 136.089  886.68 138.878  886.89 141.634  887.17
 144.259  887.45 146.555  887.92 149.114  888.67 151.542  889.72 154.101  891.31
 156.529   892.1 158.924   892.5  161.45  892.87  163.78  893.17 166.371  893.18
 168.504  893.28 171.227  893.38 173.261  893.27 176.115  893.29 178.018  893.16
 181.004  893.02 182.677   892.9 185.794  892.87 187.402   892.9 190.682  892.95
 192.159  893.06 195.604  893.86 195.965  894.03
BR D #Mann= 3
-164.829     .13   -11.8     .04  22.408     .13
BR D Banks=-11.8,
BC Design=,, 0 ,, 0 ,,,,,,
BC Use User HTab Curves=0
BC User HTab FreeFlow(D)= 0

Type RM Length L Ch R = 1 ,1178    ,166.14,126,85.06
BEGIN DESCRIPTION:
DS of Private drive
END DESCRIPTION:
XS GIS Cut Line= 3
 575788.363284154370956.18686851575721.2798513214370970.64962869
575728.8998514154371011.28861319
#Sta/Elev= 30
-164.829  899.45-127.986  894.65-125.623  894.06-119.029  890.28-107.579  887.55
 -97.605  888.29 -81.562  887.55 -61.811  885.19  -47.31  882.03 -34.482  877.75
 -25.722  876.58 -16.896  873.38    .328     872  16.109  872.73  17.684   873.4
  26.411  879.17  29.265  879.92  39.501  879.85   53.51  881.23  62.959  881.24
  73.688  882.45  78.018  883.98  87.762  883.15 121.785  887.33 138.878  886.89
 146.555  887.92 156.529   892.1  163.78  893.17 190.682  892.95 195.965  894.03
#Mann= 3 ,-1 , 0
-164.829     .13       0 -16.896     .04       0  17.684     .13       0
Bank Sta=-16.896,17.684
XS Rating Curve= 0 ,0
Exp/Cntr=0.5,0.3

Type RM Length L Ch R = 1 ,1052    ,262.48,237,198.15
XS GIS Cut Line= 3
575712.1114672084370913.46000398575715.8818432544370959.53662055
575727.787331401 4371012.0810932
#Sta/Elev= 30
 -94.259  938.46 -86.942  927.97 -55.938  899.22 -33.104   880.5 -28.871  873.83
 -25.853  871.06 -24.409   868.9      -5   868.5   9.613  868.78  13.156  869.79
  21.818  871.76  27.461  874.73   32.94  876.42  54.659  879.37  87.336   879.7
 105.938  881.12 115.354  883.28 143.668  883.74 158.333  886.76 167.815  885.49
 175.656  885.74 182.316   886.5 187.664   888.2 192.749  891.69  197.08  892.85
 210.892  893.29 221.293   892.4 228.642  892.51 231.102  892.71 234.186  894.32
#Mann= 3 ,-1 , 0
 -94.259     .13       0 -25.853     .04       0  13.156     .13       0
Bank Sta=-25.853,13.156
XS Rating Curve= 0 ,0
Exp/Cntr=0.3,0.1

Type RM Length L Ch R = 1 ,815     ,122.13,76,54.99
XS GIS Cut Line= 3
575666.446330643  4370995.859637575693.9057629834371006.03690912
575724.2333633574371007.07627714
#Sta/Elev= 30
 -96.391  911.77 -85.925   906.6 -80.873  904.51 -77.526  903.57 -66.864  897.49
 -57.415  887.96  -53.97  885.85 -49.869  881.58 -46.194  878.84 -42.323  875.15
 -38.878  872.46 -34.613  868.11 -31.004  867.16 -26.772  866.77 -24.672  866.21
     -20 866.256       0   865.2   8.333   865.7  11.483  868.07  23.196   872.2
  36.614  875.59  39.567  877.16   45.21  880.97  49.213  882.44  56.496   885.8
   59.81  886.43  66.831  889.24  72.867  890.73  80.741  892.06  99.245  892.67
#Mann= 3 ,-1 , 0
 -96.391     .13       0     -20     .04       0  11.483     .13       0
Bank Sta=-20,11.483
XS Rating Curve= 0 ,0
Exp/Cntr=0.5,0.3

Type RM Length L Ch R = 1 ,739     ,47.849,37,36.353
BEGIN DESCRIPTION:
US of Private drive
END DESCRIPTION:
XS GIS Cut Line= 5
575624.7984581294370998.65465303575654.9614665014371040.98832556
575666.857810648 4371036.6723575575701.025891071 4371020.3716533
575723.0141633424371034.72163748
#Sta/Elev= 30
-281.791  926.03 -274.31  923.26-270.308   922.8-255.609  916.78-240.421  901.34
-232.971  896.84-224.902  889.21-220.407  888.41 -210.63  889.06 -192.06  888.58
-173.885  886.17-160.138  878.94-153.247  876.18 -138.45  872.61-132.316  872.35
-120.243  869.26 -64.797  867.03  -37.27  868.27 -22.343  865.98 -14.928  865.68
  -6.463   864.4   6.791   864.4  13.123   866.7  17.881  868.72  39.403  871.54
  55.839   875.3  75.983  878.12  79.593  880.61  88.911  889.71 140.617  916.14
#Mann= 3 ,-1 , 0
-281.791     .13       0 -14.928     .04       0  13.123     .13       0
#XS Ineff= 2 , 0
       0     -45                       0
Permanent Ineff=
       F       F
Bank Sta=-14.928,13.123
XS Rating Curve= 0 ,0
Exp/Cntr=0.5,0.3

Type RM Length L Ch R = 2 ,720     ,,,
BEGIN DESCRIPTION:
Private drive (Surveyed Structure HIC_01)
END DESCRIPTION:
Bridge Culvert--1,0,-1,-1, 0
Deck Dist Width WeirC Skew NumUp NumDn MinLoCord MaxHiCord MaxSubmerge Is_Ogee
8,19.8,2.8,0, 163, 163, , , 0.98, 0, 0,0,,
-293.241-291.667-287.369-286.909 -286.45-283.104 -279.56-279.396-279.299-275.887
-273.786-269.947-269.029-268.176-265.977-263.516-262.795-262.238-259.054-255.741
-255.315-254.757-251.246-247.867-247.113-246.391-242.651-238.747-238.189-237.435
-234.285-231.857-230.479-229.626-225.132-223.491-223.162-222.671-219.783-217.684
 -216.47-214.797-212.598-210.696-208.301-205.577-203.969-201.378-199.377-198.917
-194.226-192.617-189.436-189.403-185.892-182.579-182.317-182.054-178.872-176.804
-175.492-173.492-171.293-166.306-166.175-166.077-162.041-160.564-151.411-149.409
-149.213-149.016-141.634-138.812-134.614-132.644-131.661-129.003-125.459-125.394
-125.262 -120.44 -118.11-115.814-113.583-111.517-111.188  -110.4-109.646 -107.02
-104.692-103.018-101.312 -99.605 -96.391 -95.866 -92.585 -92.421 -92.159 -88.615
 -86.647 -85.499   -21.4   -17.9   -16.5 -13.501   -10.5    -7.5    -4.5    -1.5
     1.5     4.5     7.5    10.5  52.499  56.726  59.186  60.597  60.828  61.287
  62.041  64.075  65.289  68.142  70.833  72.538  75.427   75.95  76.739  79.199
  80.906  82.185  84.417  85.007  85.368   88.55  90.813  92.388  95.209  96.883
 100.722  101.28 103.018 104.692 105.217 108.793 110.498 110.696 111.089 113.615
 114.993 117.028 120.342 120.965 121.588  125.82 130.249 130.576 132.054 134.021
 134.482 136.975  139.37
   920.9  920.67  919.16  919.07  918.95  918.17  917.33  917.28  917.25  915.94
   915.3  913.36  912.85  912.31  910.32  908.35  907.62  906.98  903.44  900.15
  899.76  899.35   897.2  894.65  894.12  893.56  890.96  889.48  889.26  889.15
  889.02  889.16  889.22  889.27  889.46  889.44  889.47  889.34  888.64  888.17
  888.28  888.35  888.48  888.54  888.55  888.59  888.57  888.26  887.95  887.88
  887.08  887.08  886.49  886.48  885.17  884.58  884.47  884.31  882.06  880.35
  879.49  878.75  877.98  876.53  876.49  876.45   875.3  875.23  874.42  874.28
  874.24   874.1  871.53  870.76   869.8  869.52  869.47  869.47  869.49  869.49
  869.48  869.23   869.1  869.02  868.97  868.91  868.82  868.76  868.86  868.83
  868.74  868.66  868.55  868.57  868.42   868.4  868.32  868.31  868.31   868.1
  868.05  868.22  866.31  866.77  866.73   866.8  866.89  867.02  867.08  867.19
  867.27  867.32  867.38  867.43  872.05  872.43  872.91  873.16  873.19  873.24
  873.35  873.69  873.88  874.54  876.52  877.51  879.38  879.85  880.87   884.1
  885.46  886.42  887.72  888.04  888.29  890.26  891.33   892.1  893.88     895
  897.17  897.44   897.8  898.16  898.45  900.84  902.01   902.1   902.3   903.8
  904.56  905.86  907.41  907.69  908.02  909.85  912.49   912.6  913.15  913.85
  914.06  915.75   917.4
                                                                                
                                                                                
                                                                                
                                                                                
                                                                                
                                                                                
                                                                                
                                                                                
                                                                                
                                                                                
                                                                                
                                                                                
                                                                                
                                                                                
                                                                                
                                                                                
                        
-293.241-291.667-287.369-286.909 -286.45-283.104 -279.56-279.396-279.299-275.887
-273.786-269.947-269.029-268.176-265.977-263.516-262.795-262.238-259.054-255.741
-255.315-254.757-251.246-247.867-247.113-246.391-242.651-238.747-238.189-237.435
-234.285-231.857-230.479-229.626-225.132-223.491-223.162-222.671-219.783-217.684
 -216.47-214.797-212.598-210.696-208.301-205.577-203.969-201.378-199.377-198.917
-194.226-192.617-189.436-189.403-185.892-182.579-182.317-182.054-178.872-176.804
-175.492-173.492-171.293-166.306-166.175-166.077-162.041-160.564-151.411-149.409
-149.213-149.016-141.634-138.812-134.614-132.644-131.661-129.003-125.459-125.394
-125.262 -120.44 -118.11-115.814-113.583-111.517-111.188  -110.4-109.646 -107.02
-104.692-103.018-101.312 -99.605 -96.391 -95.866 -92.585 -92.421 -92.159 -88.615
 -86.647 -85.499   -21.4   -17.9   -16.5 -13.501   -10.5    -7.5    -4.5    -1.5
     1.5     4.5     7.5    10.5  52.499  56.726  59.186  60.597  60.828  61.287
  62.041  64.075  65.289  68.142  70.833  72.538  75.427   75.95  76.739  79.199
  80.906  82.185  84.417  85.007  85.368   88.55  90.813  92.388  95.209  96.883
 100.722  101.28 103.018 104.692 105.217 108.793 110.498 110.696 111.089 113.615
 114.993 117.028 120.342 120.965 121.588  125.82 130.249 130.576 132.054 134.021
 134.482 136.975  139.37
   920.9  920.67  919.16  919.07  918.95  918.17  917.33  917.28  917.25  915.94
   915.3  913.36  912.85  912.31  910.32  908.35  907.62  906.98  903.44  900.15
  899.76  899.35   897.2  894.65  894.12  893.56  890.96  889.48  889.26  889.15
  889.02  889.16  889.22  889.27  889.46  889.44  889.47  889.34  888.64  888.17
  888.28  888.35  888.48  888.54  888.55  888.59  888.57  888.26  887.95  887.88
  887.08  887.08  886.49  886.48  885.17  884.58  884.47  884.31  882.06  880.35
  879.49  878.75  877.98  876.53  876.49  876.45   875.3  875.23  874.42  874.28
  874.24   874.1  871.53  870.76   869.8  869.52  869.47  869.47  869.49  869.49
  869.48  869.23   869.1  869.02  868.97  868.91  868.82  868.76  868.86  868.83
  868.74  868.66  868.55  868.57  868.42   868.4  868.32  868.31  868.31   868.1
  868.05  868.22  866.31  866.77  866.73   866.8  866.89  867.02  867.08  867.19
  867.27  867.32  867.38  867.43  872.05  872.43  872.91  873.16  873.19  873.24
  873.35  873.69  873.88  874.54  876.52  877.51  879.38  879.85  880.87   884.1
  885.46  886.42  887.72  888.04  888.29  890.26  891.33   892.1  893.88     895
  897.17  897.44   897.8  898.16  898.45  900.84  902.01   902.1   902.3   903.8
  904.56  905.86  907.41  907.69  908.02  909.85  912.49   912.6  913.15  913.85
  914.06  915.75   917.4
                                                                                
                                                                                
                                                                                
                                                                                
                                                                                
                                                                                
                                                                                
                                                                                
                                                                                
                                                                                
                                                                                
                                                                                
                                                                                
                                                                                
                                                                                
                                                                                
                        
BR Coef=-1 , 0 , 0 ,, 0 ,,,0.8,-1,,0,
WSPro=,,,, 1 ,,,, 0 ,,,, 0 ,,,,-1 ,-1 ,-1 , 0 , 0 , 0 , 0 , 0
Culvert=1,2,,19.5,0.024,0.9,1,2,3,864.37,-16.5,864.24,-16.5,Culvert #1  , 0 ,8
Culvert Bottom n=0.024
Culvert=1,2,,19.5,0.024,0.9,1,2,3,864.59,-13.5,864.29,-13.5,Culvert #2  , 0 ,8
Culvert Bottom n=0.024
Culvert=1,2,,19.5,0.024,0.9,1,2,3,864.63,-10.5,864.31,-10.5,Culvert #3  , 0 ,8
Culvert Bottom n=0.024
Culvert=1,2,,19.5,0.024,0.9,1,2,3,864.77,-7.5,864.36,-7.5,Culvert #4  , 0 ,8
Culvert Bottom n=0.024
Culvert=1,2,,19.5,0.024,0.9,1,2,3,864.84,-4.5,864.33,-4.5,Culvert #5  , 0 ,8
Culvert Bottom n=0.024
Culvert=1,2,,19.5,0.024,0.9,1,2,3,864.89,-1.5,864.39,-1.5,Culvert #6  , 0 ,8
Culvert Bottom n=0.024
Culvert=1,2,,19.5,0.024,0.9,1,2,3,864.95,1.5,864.44,1.5,Culvert #7  , 0 ,8
Culvert Bottom n=0.024
Culvert=1,2,,19.5,0.024,0.9,1,2,3,865.06,4.5,864.5,4.5,Culvert #8  , 0 ,8
Culvert Bottom n=0.024
Culvert=1,2,,19.5,0.024,0.9,1,2,3,865.14,7.5,864.45,7.5,Culvert #9  , 0 ,8
Culvert Bottom n=0.024
Culvert=1,2,,19.5,0.024,0.9,1,2,3,865.23,10.5,864.47,10.5,Culvert #10 , 0 ,8
Culvert Bottom n=0.024
BR U #Sta/Elev= 30
-281.791  926.03 -274.31  923.26-270.308   922.8-255.609  916.78-240.421  901.34
-232.971  896.84-224.902  889.21-220.407  888.41 -210.63  889.06 -192.06  888.58
-173.885  886.17-160.138  878.94-153.247  876.18 -138.45  872.61-132.316  872.35
-120.243  869.26 -64.797  867.03  -37.27  868.27   -17.9   866.5   -17.3  864.37
   -16.5  864.32    11.3  865.23    12.6   867.5   47.08  872.87   60.63  876.12
  75.983  878.12  79.593  880.61  88.911  889.71 104.659  897.22 140.617  916.14
BR U #Mann= 3
-281.791     .13   -17.9     .04    12.6     .13
BR U Banks=-17.9,12.6
BR D #Sta/Elev= 30
-301.083     913-297.113  913.07-277.526  908.67-262.467  896.01-259.054  892.15
-252.164  889.21-215.978   887.9-201.608  886.07-194.521   884.1-186.056  879.51
-176.575  876.07-165.517  874.35-154.495  874.35-143.964  869.76-121.817  869.11
-108.136  865.48  -96.49   865.3 -88.944   866.5  -26.87  862.18 -23.851  863.54
  -19.16  863.55   2.953  861.83      12  862.21    14.6   864.5   23.72  866.69
  28.576  870.67  66.142  874.86  72.703  881.29  81.332  887.47 137.532  918.27
BR D #Mann= 3
-301.083     .13  -19.16     .04    14.6     .13
BR D Banks=-19.16,
BC Design=,, 0 ,, 0 ,,,,,,
BC Use User HTab Curves=0
BC User HTab FreeFlow(D)= 0

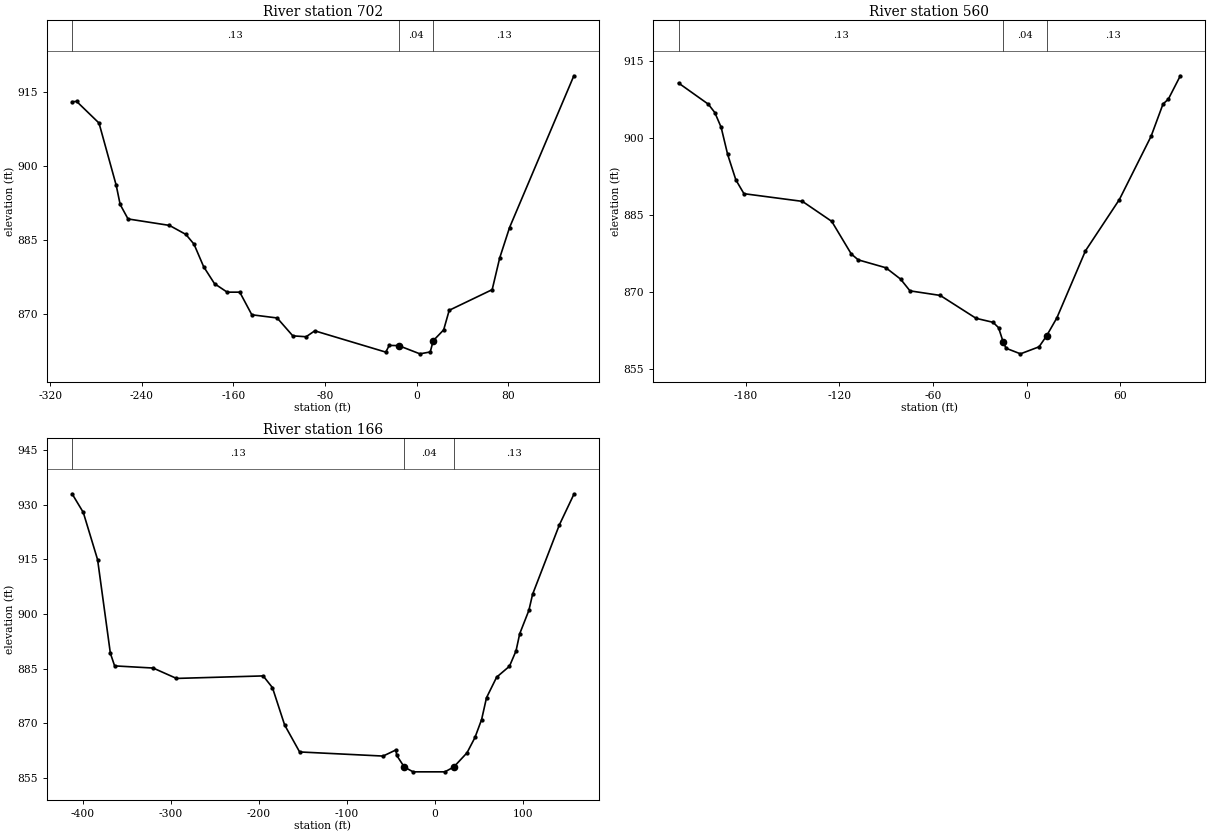
Type RM Length L Ch R = 1 ,702     ,58.61,142,188.44
BEGIN DESCRIPTION:
DS of Private drive (Invert from survey data HIC_01)
END DESCRIPTION:
XS GIS Cut Line= 5
 575617.653946044371002.88832509575651.7854504624371050.77850168
575669.814370685 4371044.1277656575700.4162910634371029.52479741
575718.6433312884371041.42114156
#Sta/Elev= 30
-301.083     913-297.113  913.07-277.526  908.67-262.467  896.01-259.054  892.15
-252.164  889.21-215.978   887.9-201.608  886.07-194.521   884.1-186.056  879.51
-176.575  876.07-165.517  874.35-154.495  874.35-143.964  869.76-121.817  869.11
-108.136  865.48  -96.49   865.3 -88.944   866.5  -26.87  862.18 -23.851  863.54
 -15.617   863.5   2.953  861.83      12  862.21    14.6   864.5   23.72  866.69
  28.576  870.67  66.142  874.86  72.703  881.29  81.332  887.47 137.532  918.27
#Mann= 3 ,-1 , 0
-301.083     .13       0 -15.617     .04       0    14.6     .13       0
#XS Ineff= 2 , 0
       0     -40                       0
Permanent Ineff=
       F       F
Bank Sta=-15.617,14.6
XS Rating Curve= 0 ,0
Exp/Cntr=0.5,0.3

Type RM Length L Ch R = 1 ,560     ,402.06,394,385.89
XS GIS Cut Line= 3
575617.126642034 4371003.6808051575639.6147863124371049.45566966
575665.5441226324371088.61332615
#Sta/Elev= 30
  -222.9  910.76-203.839  906.64-199.672  905.01-195.604  902.13-191.437  896.84
-186.188  891.89-181.004   889.2-143.537   887.7 -124.77  883.81-112.238  877.45
-107.808  876.31 -90.092  874.77 -80.676  872.56 -74.639  870.27 -55.282  869.38
 -32.316  864.92 -21.424  864.14 -17.913   863.1     -15 860.361 -13.123  859.09
  -3.871     858   8.038  859.37  12.828  861.49  19.455  865.01  37.762  878.07
  59.482  888.06   79.79  900.38  87.434  906.67  90.814   907.6  98.524  912.17
#Mann= 3 ,-1 , 0
  -222.9     .13       0     -15     .04       0  12.828     .13       0
Bank Sta=-15,12.828
XS Rating Curve= 0 ,0
Exp/Cntr=0.3,0.1

Type RM Length L Ch R = 1 ,166     ,166,166,166
BEGIN DESCRIPTION:
(Channel invert from effective FIS)
END DESCRIPTION:
XS GIS Cut Line= 4
575467.0126401794371030.77447743575477.2661123054371067.81682189
575563.9177053764371137.60078275 575587.731729674371139.58503078
#Sta/Elev= 30
-412.106  933.02-399.377   927.9-383.136  914.94-368.635  889.24-363.812  885.78
-320.112  885.19-293.602  882.34 -195.21  883.03-184.678  879.81-170.866  869.57
-153.839  862.16 -59.121  861.03 -44.455  862.72 -43.766  861.26     -35     858
     -25   856.7      11   856.7      21     858  36.122  861.92  45.177  866.13
  52.723  871.06  58.268  877.04  69.751  882.68   84.35  885.69  91.765  889.89
  95.965  894.61 106.332     901 110.564  905.42  141.01  924.51 157.415  932.87
#Mann= 3 ,-1 , 0
-412.106     .13       0     -35     .04       0      21     .13       0
Bank Sta=-35,21
XS Rating Curve= 0 ,0
Exp/Cntr=0.3,0.1
Stream Node=Hickman Run     ,Reach 1         , 0 , 0 ,Upstream end
Stream Node=Hickman Run     ,Reach 1         , 0 , 1 ,Downstream end

Chan Stop Cuts=-1
Use User Specified Reach Order=0
Composite Channel Slope=5