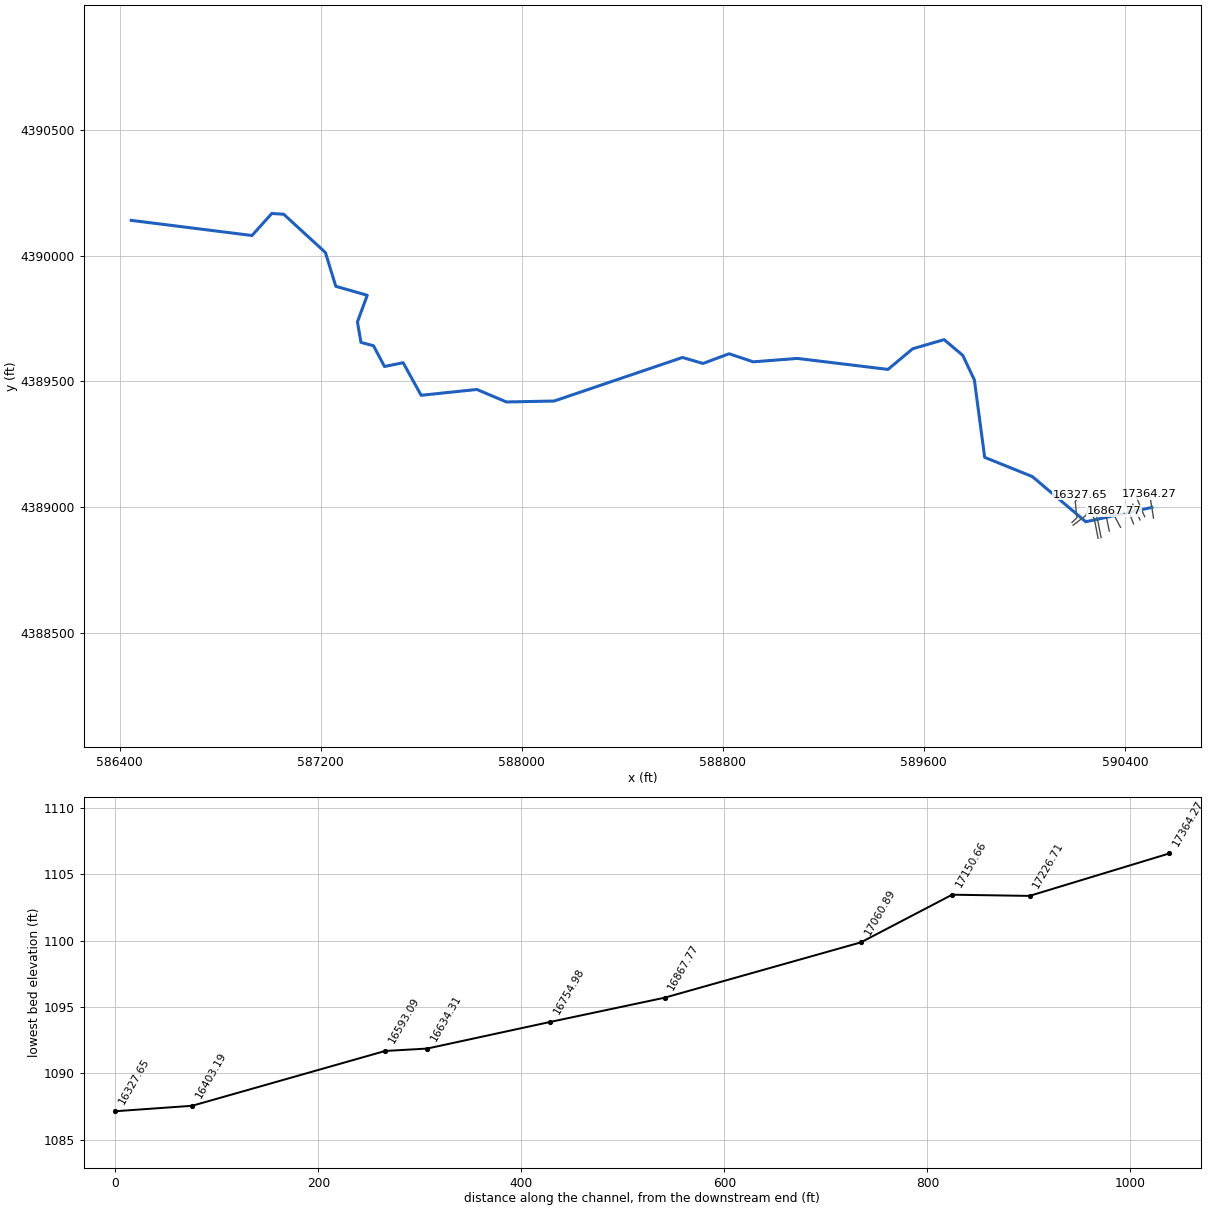
--- Pompono_Run_Detail_Study.prj (project) ---

Proj Title=Pompono_Run_Detail_Study
Current Plan=p01
Default Exp/Contr=0.3,0.1
English Units
Geom File=g01
Flow File=f01
Flow File=f02
Plan File=p01
Plan File=p03
Y Axis Title=Elevation
X Axis Title(PF)=Main Channel Distance
X Axis Title(XS)=Station
BEGIN DESCRIPTION:
Detailed Study for Pompono Run
Upper Monongahela Watershed, Monongalia County, WV
Submitted by RAMPP for FEMA Region III
Model date: October 2015
HEC-RAS version 4.1.0
Vertical Datum: NAVD88 (feet)
Horizontal Datum: NAD_1983_UTM_Zone_17N
END DESCRIPTION:
DSS Export Rating Curves= 0
DSS Export Rating Curve Sorted= 0
DSS Export Volume Flow Curves= 0
DXF Filename=..\..\..\..\..\..\..\..\..\GTB_TEMP\SVK\Upper_mon\PreRAS\Pompano_Run.
DXF OffsetX= 0
DXF OffsetY= 0
DXF ScaleX= 1
DXF ScaleY= 10

--- Pompono_Run_Detail_Study.p01 (plan) ---

Plan Title=Multi Profile
Program Version=4.10
Short Identifier=Multi
Geom File=g01
Flow File=f01
Subcritical Flow
K Sum by GR= 0
Std Step Tol= 0.01
Critical Tol= 0.01
Num of Std Step Trials= 20
Max Error Tol= 0.3
Flow Tol Ratio= 0.001
Split Flow NTrial= 30
Split Flow Tol= 0.02
Split Flow Ratio= 0.02
Log Output Level= 0
Friction Slope Method= 1
Unsteady Friction Slope Method= 2
Unsteady Bridges Friction Slope Method= 1
Parabolic Critical Depth
Global Vel Dist= 0 , 0 , 0
Global Log Level= 0
CheckData=True
Encroach Param=-1 ,0,0, 0
Computation Interval=1HOUR
Output Interval=1HOUR
Run HTab= 0
Run UNet= 0
Run PostProcess= 0
Run WQNet= 0
UNET Theta= 1
UNET Theta Warmup= 1
UNET ZTol= 0.02
UNET ZSATol= 0.05
UNET MxIter= 20
UNET MaxInSteps= 0
UNET DtIC= 0
UNET DtMin= 0
UNET MaxCRTS= 20
UNET WFStab= 2
UNET SFStab= 1
UNET WFX= 1
UNET SFX= 1
UNET DSS MLevel= 4
UNET DZMax Abort= 98.43
UNET Convert EG Bridges= 0
UNET Use Existing IB Tables=-1
UNET Froude Reduction=False
UNET Froude Limit= 1
UNET Froude Power= 10
UNET Time Slicing=0,0, 5
UNET Junction Losses=0
Instantaneous Interval=1HOUR
Write IC File= 0
Write IC File at Sim End=0
Echo Input=False
Echo Parameters=False
Echo Output=False
Write Detailed= 0
WQ AD Non Conservative
WQ ULTIMATE=-1
WQ Max Comp Step=1HOUR
WQ Output Interval=15MIN
WQ Output Selected Increments= 0
WQ Output face flow=0
WQ Output face velocity=0
WQ Output face area=0
WQ Output face dispersion=0
WQ Output cell volume=0
WQ Output cell surface area=0
WQ Output cell continuity=0
WQ Output cumulative cell continuity=0
WQ Output face conc=0
WQ Output face dconc_dx=0
WQ Output face courant=0
WQ Output face peclet=0
WQ Output face adv mass=0
WQ Output face disp mass=0
WQ Output cell mass=0
WQ Output cell source sink temp=0
WQ Output cell source sink nsm=0
WQ Output MaxMinRange=-1
WQ Daily Max Min Mean=-1
WQ Daily Range=0
WQ Daily Time=0
WQ Create Restart=0
WQ Fixed Restart=0
WQ System Summary=0
WQ Use Fixed Temperature=0
Sorting and Armoring Iterations= 10
XS Update Threshold= 0.02
Hydraulics Update Threshold= 0.02
Energy Slope Method= 1
Volume Change Method= 0
XS Weighting Method= 0
Number of US Weighted Cross Sections= 1
Number of DS Weighted Cross Sections= 1
Upstream XS Weight=0.25
Main XS Weight=0.5
Downstream XS Weight=0.25
Number of DS XS's Weighted with US Boundary= 1
Upstream Boundary Weight= 1
Weight of XSs Associated with US Boundary= 0
Number of US XS's Weighted with DS Boundary= 1
Downstream Boundary Weight= 0.5
Weight of XSs Associated with DS Boundary= 0.5
Sediment Output Level= 4
Mass or Volume Output= 0
Output Increment Type= 1
Profile and TS Output Increment= 10
XS Output Flag= 0
XS Output Increment= 10
Disregard all LS=0
Disregard all Conn=0
Disregard all Breaches=0
Disregard all Pumps=0

--- Pompono_Run_Detail_Study.p03 (plan) ---

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Plan Title=Floodway
Short Identifier=FW
Geom File=g01
Flow File=f02
Encroach Param=-1 ,10,10, 2
Encroach River=Pompano Run
Encroach Reach=1
Encroach Node=17364.27
       1    -5.5      11
Encroach Node=17226.71
       1     -24      14
Encroach Node=17150.66
       1     -25       5
Encroach Node=17060.89
       1     -25   14.92
Encroach Node=16867.77
       1      -7      16
Encroach Node=16754.98
       1     -23      15
Encroach Node=16634.31
       1     -25   15.02
Encroach Node=16593.09
       1     -20      30
Encroach Node=16403.19
       1     -19   23.06
Encroach Node=16327.65
       1     -15      15
Encroach Node=16262.53
       1      -5    4.92
Encroach Node=16078.3
       1  -14.92      13
Encroach Node=15750.79
       1     -10      10
Encroach Node=15534.98
       1     -11      24
Encroach Node=15342.21
       1     -50     6.7
Encroach Node=15164.56
       1     -55       9
Encroach Node=15026.88
       1     -70      25
Encroach Node=14839.24
       1     -30      40
Encroach Node=14768.2
       1     -28      18
Encroach Node=14619.27
       1     -25      35
Encroach Node=14473.54
       1     -50      27
Encroach Node=11978.2
       1     -16      13
Encroach Node=11945.01
       1  -15.05      12
Encroach Node=11820.46
       1     -25       7
Encroach Node=11681.43
       1     -25      14
Encroach Node=11654.16
       1     -23      14
Encroach Node=11630.88
       1     -30      15
Encroach Node=11521.52
       1   -19.5      14
Encroach Node=11188.94
       1     -14      18
Encroach Node=10842.42
       1  -19.83      11
Encroach Node=10368.34
       1     -19    7.15
Encroach Node=10282.87
       1     -21      22
Encroach Node=10119.39
       1     -50      45
Encroach Node=10016.05
       1     -45      65
Encroach Node=10001.92
       1     -50      63
Encroach Node=9958.451
       1     -70      70
Encroach Node=9798.186
       1    -120      95
Encroach Node=9707.625
       1     -40      85
Encroach Node=9495.94
       1     -45      62
Encroach Node=9300.029
       1     -42      55
Encroach Node=9082.674
       1     -35      40
Encroach Node=8872.72
       1  -30.28   40.21
Encroach Node=8788.141
       1  -34.25   39.04
Encroach Node=8602.517
       1     -43      16
Encroach Node=8456.063
       1     -28      55
Encroach Node=8391.08
       1     -25      75
Encroach Node=8235.926
       1     -17     115
Encroach Node=8163.714
       1     -10      95
Encroach Node=7867.349
       1   -6.36   56.76
Encroach Node=7695.04
       1   -7.04     145
Encroach Node=7664.872
       1     -16   152.1
Encroach Node=7085.672
       1     -25      30
Encroach Node=6886.601
       1  -20.45   19.38
Encroach Node=6788.537
       1   -9.91      13
Encroach Node=6612.913
       1     -40      27
Encroach Node=6299.223
       1     -50      43
Encroach Node=6146.841
       1     -66      14
Encroach Node=6098.868
       1     -80       8
Encroach Node=6061.673
       1   -72.5    10.6
Encroach Node=6029.341
       1     -70   11.85
Encroach Node=5816.788
       1     -22    5.15
Encroach Node=5561.729
       1     -29      14
Encroach Node=5392.549
       1     -29      17
Encroach Node=5057.809
       1     -10      31
Encroach Node=4755.961
       1     -30    9.02
Encroach Node=4478.064
       1   -18.5      24
Encroach Node=4097.277
       1     -30      50
Encroach Node=4009.852
       1     -40      20
Encroach Node=3976.319
       1     -45   13.55
Encroach Node=3954.902
       1     -45      20
Encroach Node=3906.421
       1     -28   14.11
Encroach Node=3582.375
       1     -12      28
Encroach Node=3419.226
       1     -12      15
Encroach Node=3216.608
       1      -9       9
Encroach Node=2941.517
       1  -14.92      20
Encroach Node=2639.432
       1  -14.92      11
Encroach Node=2456.117
       1     -20      15
Encroach Node=2386.734
       1    -8.5       9
Encroach Node=2359.093
       1     -12    4.49
Encroach Node=2252.767
       1     -15      10
Encroach Node=1965.16
       1     -55      30
Encroach Node=1789.541
       1     -19      10
Encroach Node=1705.592
       1     -28      20
Encroach Node=1580.157
       1     -55      55
Encroach Node=120.93
       1     -15      30
UNET DZMax Abort= 100

--- Pompono_Run_Detail_Study.f01 (steady flow) ---

Flow Title=Basic Flow File
Program Version=4.10
Number of Profiles= 6
Profile Names=10PCT,4PCT,2PCT,1PCT,0_2PCT,1PCT_PLUS
River Rch & RM=Pompano Run,1               ,17364.27
   150.6   193.2   229.1   263.3   349.1   348.9
River Rch & RM=Pompano Run,1               ,16078.3
   183.1   234.9   278.6   320.3   424.3   424.4
River Rch & RM=Pompano Run,1               ,15164.56
   240.5   308.8   366.3   421.2   558.1   558.1
River Rch & RM=Pompano Run,1               ,14768.2
   282.3   360.2   425.5   487.8   642.9   646.3
River Rch & RM=Pompano Run,1               ,14473.54
   417.8   532.2   627.3     718   942.5   951.4
River Rch & RM=Pompano Run,1               ,11978.2
   505.1   641.3   754.4   862.5  1129.4  1142.8
River Rch & RM=Pompano Run,1               ,11681.43
   515.5   654.1   769.3   879.3  1150.8  1165.1
River Rch & RM=Pompano Run,1               ,11654.16
   564.4   714.9   839.8   957.8    1251  1269.1
River Rch & RM=Pompano Run,1               ,10842.42
   670.2   847.9  1000.1  1138.9  1484.3    1509
River Rch & RM=Pompano Run,1               ,9495.94
       1       2   141.1   279.9   625.3     650
River Rch & RM=Pompano Run,1               ,9300.029
       1    22.9   188.7   336.3   702.4   724.8
River Rch & RM=Pompano Run,1               ,8602.517
       1   101.5   281.5   441.5   839.6   864.2
River Rch & RM=Pompano Run,1               ,8391.08
   753.2   960.5  1140.5  1300.5  1698.6  1723.2
River Rch & RM=Pompano Run,1               ,7867.349
   770.4   990.7  1180.7  1351.1    1772  1790.2
River Rch & RM=Pompano Run,1               ,7695.04
   792.2  1018.4  1213.5  1388.1  1820.3  1839.2
River Rch & RM=Pompano Run,1               ,7085.672
     797  1030.8    1230  1410.3  1854.7  1868.6
River Rch & RM=Pompano Run,1               ,6612.913
   818.8  1064.1  1272.2  1460.1  1924.6  1934.6
River Rch & RM=Pompano Run,1               ,4755.961
   855.3    1115  1333.9  1531.9  2021.8  2029.8
River Rch & RM=Pompano Run,1               ,4097.277
   861.3    1125  1348.1  1550.7  2052.2  2054.7
River Rch & RM=Pompano Run,1               ,3216.608
   869.4  1140.1  1369.6  1578.3  2094.9  2091.2
River Rch & RM=Pompano Run,1               ,2456.117
   988.5  1314.3  1582.5  1828.5  2429.3  2422.8
River Rch & RM=Pompano Run,1               ,1580.157
  1056.9    1405  1690.8  1952.9  2593.8  2587.6
River Rch & RM=Pompano Run,1               ,120.93
  1051.5  1282.7  1402.1  1473.4  1623.2  1952.3
Boundary for River Rch & Prof#=Pompano Run,1               , 1
Up Type= 0
Dn Type= 3
Dn Slope=0.001
Boundary for River Rch & Prof#=Pompano Run,1               , 2
Up Type= 0
Dn Type= 3
Dn Slope=0.001
Boundary for River Rch & Prof#=Pompano Run,1               , 3
Up Type= 0
Dn Type= 3
Dn Slope=0.001
Boundary for River Rch & Prof#=Pompano Run,1               , 4
Up Type= 0
Dn Type= 3
Dn Slope=0.001
Boundary for River Rch & Prof#=Pompano Run,1               , 5
Up Type= 0
Dn Type= 3
Dn Slope=0.001
Boundary for River Rch & Prof#=Pompano Run,1               , 6
Up Type= 0
Dn Type= 3
Dn Slope=0.001
Set Internal Change=Pompano Run     ,1               ,9707.625, 6 , 3 ,1016.95
Set Internal Change=Pompano Run     ,1               ,9707.625, 5 , 3 ,1016.9
Set Internal Change=Pompano Run     ,1               ,9707.625, 4 , 3 ,1016.4
Set Internal Change=Pompano Run     ,1               ,9707.625, 3 , 3 ,1016.2
Set Internal Change=Pompano Run     ,1               ,9707.625, 2 , 3 ,1016
Set Internal Change=Pompano Run     ,1               ,9707.625, 1 , 3 ,1015.5
Set Internal Change=Pompano Run     ,1               ,1580.157, 6 , 3 ,884.5
Set Internal Change=Pompano Run     ,1               ,1580.157, 5 , 3 ,888
Set Internal Change=Pompano Run     ,1               ,1580.157, 4 , 3 ,874.2
Set Internal Change=Pompano Run     ,1               ,1580.157, 3 , 3 ,867.7
Set Internal Change=Pompano Run     ,1               ,1580.157, 2 , 3 ,857.5
Set Internal Change=Pompano Run     ,1               ,1580.157, 1 , 3 ,845.5
DSS Import GetInterval= 0
DSS Import GetPeak= 0
DSS Import FillOption= 0

--- Pompono_Run_Detail_Study.f02 (steady flow) ---

Flow Title=floodway
Program Version=4.10
Number of Profiles= 2
Profile Names=1PCT,FWY
River Rch & RM=Pompano Run,1               ,17364.27
   263.3   263.3
River Rch & RM=Pompano Run,1               ,16078.3
   320.3   320.3
River Rch & RM=Pompano Run,1               ,15164.56
   421.2   421.2
River Rch & RM=Pompano Run,1               ,14768.2
   487.8   487.8
River Rch & RM=Pompano Run,1               ,14473.54
     718     718
River Rch & RM=Pompano Run,1               ,11978.2
   862.5   862.5
River Rch & RM=Pompano Run,1               ,11681.43
   879.3   879.3
River Rch & RM=Pompano Run,1               ,11654.16
   957.8   957.8
River Rch & RM=Pompano Run,1               ,10842.42
  1138.9  1138.9
River Rch & RM=Pompano Run,1               ,9495.94
   279.9   279.9
River Rch & RM=Pompano Run,1               ,9300.029
   336.3   336.3
River Rch & RM=Pompano Run,1               ,8602.517
   441.5   441.5
River Rch & RM=Pompano Run,1               ,8391.08
  1300.5  1300.5
River Rch & RM=Pompano Run,1               ,7867.349
  1351.1  1351.1
River Rch & RM=Pompano Run,1               ,7695.04
  1388.1  1388.1
River Rch & RM=Pompano Run,1               ,7085.672
  1410.3  1410.3
River Rch & RM=Pompano Run,1               ,6612.913
  1460.1  1460.1
River Rch & RM=Pompano Run,1               ,4755.961
  1531.9  1531.9
River Rch & RM=Pompano Run,1               ,4097.277
  1550.7  1550.7
River Rch & RM=Pompano Run,1               ,3216.608
  1578.3  1578.3
River Rch & RM=Pompano Run,1               ,2456.117
  1828.5  1828.5
River Rch & RM=Pompano Run,1               ,1580.157
  1952.9  1952.9
River Rch & RM=Pompano Run,1               ,120.93
  1473.4  1473.4
Boundary for River Rch & Prof#=Pompano Run,1               , 1
Up Type= 0
Dn Type= 3
Dn Slope=0.001
Boundary for River Rch & Prof#=Pompano Run,1               , 2
Up Type= 0
Dn Type= 1
Dn Known WS=805.28
Set Internal Change=Pompano Run     ,1               ,9707.625, 2 , 3 ,1016.4
Set Internal Change=Pompano Run     ,1               ,9707.625, 1 , 3 ,1016.4
Set Internal Change=Pompano Run     ,1               ,1580.157, 2 , 3 ,874.2
Set Internal Change=Pompano Run     ,1               ,1580.157, 1 , 3 ,874.2
DSS Import GetInterval= 0
DSS Import GetPeak= 0
DSS Import FillOption= 0

--- Pompono_Run_Detail_Study.g01 (geometry) ---

Geom Title=Pompano_Run_Detail_Study
Program Version=4.10

River Reach=Pompano Run     ,1
Reach XY= 30
     590507.4664    4388998.0916     590244.4026    4388941.0025
     590031.5273    4389120.8559     589841.9721    4389197.3058
     589800.8759    4389505.7299     589754.8359    4389603.0982
     589680.5531    4389665.7346     589555.8046    4389629.5335
     589457.1164    4389547.2497     589096.3856    4389590.9459
     588920.9122    4389577.3548      588824.885    4389609.5021
     588720.9269    4389570.8961     588639.3349    4389594.7467
     588128.9656    4389421.4801     587939.0021    4389417.6762
     587821.1024    4389467.4196     587599.4854    4389444.2304
     587527.8482    4389573.8131     587453.5014    4389558.8626
     587409.8693    4389641.3933     587359.8516    4389654.8015
       587345.91    4389736.5092     587384.9366    4389842.1956
     587259.7309    4389878.0126     587218.5615    4390012.3075
     587052.5461     4390164.738     587005.0491    4390167.6915
     586926.3284    4390080.1072     586445.6131    4390140.3723

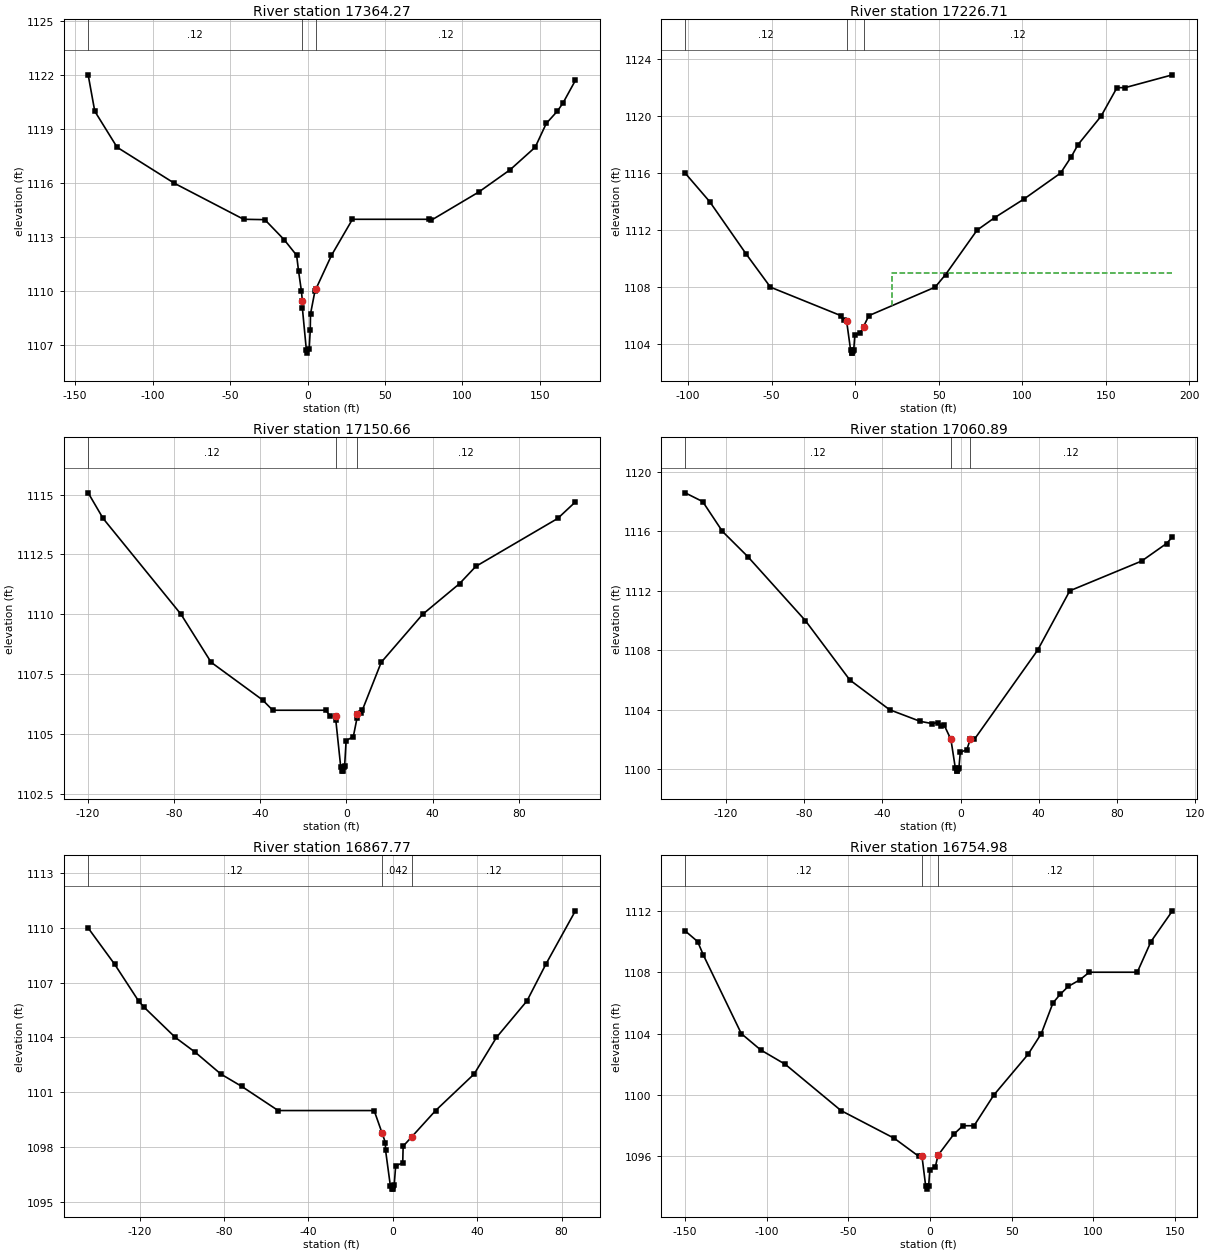
Type RM Length L Ch R = 1 ,17364.27,133.693,137.794,137.794
Node Name=AZ
XS GIS Cut Line= 3
     590513.7597    4388955.2508     590508.9404    4388987.4636
     590498.4249    4389049.8641
#Sta/Elev= 30
-141.568 1122.02-137.303    1120  -122.9    1118 -85.925    1116 -41.207    1114
 -27.559 1113.98 -15.092 1112.87  -7.021    1112  -5.774 1111.13  -3.904    1110
  -3.314 1109.46  -3.282 1109.05   -.756 1106.76   -.002 1106.57   1.081  1106.8
    1.77 1107.84   1.936 1108.74   4.757    1110   5.545 1110.15  15.486    1112
  29.003    1114  78.478    1114  79.724 1113.94 110.466 1115.51 130.774 1116.75
 146.949    1118 154.101 1119.32  161.22    1120 164.797 1120.44   172.9 1121.71
#Mann= 3 ,-1 , 0
-141.568     .12       0  -3.314    .042       0   5.545     .12       0
Bank Sta=-3.314,5.545
XS Rating Curve= 0 ,0
Exp/Cntr=0.3,0.1

Type RM Length L Ch R = 1 ,17226.71,75.669,76.175,76.734
Node Name=AY
XS GIS Cut Line= 3
590478.6261857074388961.13761903590466.4067535564388989.55412338
590444.2264572814389043.08614804
#Sta/Elev= 28
-101.673    1116 -87.008    1114 -65.092 1110.31 -50.656    1108  -8.497    1106
  -6.759 1105.68  -5.052 1105.61  -2.656 1103.56  -1.902 1103.37  -1.606 1103.38
  -1.344 1103.53   -.819  1103.6    -.13 1104.64   3.217 1104.81   5.052 1105.23
   8.235    1106    47.9    1108  54.134 1108.88  72.999    1112  83.563 1112.88
 101.017 1114.18 122.933    1116 129.429 1117.16 133.399    1118 147.211    1120
 156.726    1122 161.549    1122 189.895  1122.9
#Mann= 3 ,-1 , 0
-101.673     .12       0  -5.052    .042       0   5.052     .12       0
#XS Ineff= 2 , 0
       0                      22       0    1109
Permanent Ineff=
       F       F
Bank Sta=-5.052,5.052
XS Rating Curve= 0 ,0
Exp/Cntr=0.3,0.1

Type RM Length L Ch R = 1 ,17150.66,91.086,89.933,88.953
Node Name=AX
XS GIS Cut Line= 3
     590460.2079    4388948.2951     590444.7138    4388981.3053
     590431.2095    4389010.8824
#Sta/Elev= 27
 -119.95 1115.07 -112.99    1114   -76.8    1110  -62.83    1108  -38.94 1106.43
  -34.22    1106   -9.55    1106   -7.41 1105.74   -4.99 1105.76  -4.921 1105.59
  -2.656 1103.65  -1.902 1103.46  -1.606 1103.47  -1.344 1103.62   -.819 1103.69
    -.13 1104.73   3.217  1104.9   4.921 1105.67    4.99 1105.85    6.56 1105.87
    7.38    1106   16.17    1108    35.4    1110   52.53 1111.28    60.1    1112
   98.13    1114  106.36 1114.69
#Mann= 3 ,-1 , 0
 -119.95     .12       0   -4.99    .042       0    4.99     .12       0
Bank Sta=-4.99,4.99
XS Rating Curve= 0 ,0
Exp/Cntr=0.3,0.1

Type RM Length L Ch R = 1 ,17060.89,191.348,193.443,190.707
Node Name=AW
XS GIS Cut Line= 2
590434.2290171584388932.69977868590406.7756808194389003.52920355
#Sta/Elev= 27
-140.846 1118.59 -131.89    1118-121.818    1116-108.825  1114.3 -79.396    1110
 -56.627    1106 -36.286    1104 -20.669 1103.22 -14.665 1103.07 -11.483 1103.14
 -10.105 1102.91  -8.366 1102.96  -4.921    1102  -2.656 1100.06  -1.902 1099.87
  -1.606 1099.88  -1.344 1100.03   -.819  1100.1    -.13 1101.14   3.217 1101.31
   4.921    1102   7.021    1102  39.403    1108  55.873    1112  92.618    1114
 105.348 1115.18 108.366 1115.62
#Mann= 3 ,-1 , 0
-140.846     .12       0  -4.921    .042       0   4.921     .12       0
Bank Sta=-4.921,4.921
XS Rating Curve= 0 ,0
Exp/Cntr=0.3,0.1

Type RM Length L Ch R = 1 ,16867.77,117.815,112.981,112.977
Node Name=AV
XS GIS Cut Line= 3
     590382.5876    4388918.9831     590361.7421    4388957.7528
     590356.4077     4388983.599
#Sta/Elev= 28
 -144.42 1109.99 -131.82    1108 -120.54    1106 -117.95 1105.66 -103.08    1104
  -93.54 1103.18  -81.53    1102  -71.59 1101.32  -54.33    1100   -8.83    1100
   -5.05 1098.76   -3.51 1098.25  -3.421 1097.83  -1.156 1095.89   -.402  1095.7
   -.106 1095.71    .156 1095.86    .681 1095.93    1.37 1096.97   4.717 1097.14
    4.92 1098.05    9.06 1098.57   20.31    1100   38.58    1102   49.15    1104
   63.62    1106   72.54    1108   86.58 1110.93
#Mann= 3 ,-1 , 0
 -144.42     .12       0   -5.05    .042       0    9.06     .12       0
Bank Sta=-5.05,9.06
XS Rating Curve= 0 ,0
Exp/Cntr=0.3,0.1

Type RM Length L Ch R = 1 ,16754.98,120.068,120.88,122.056
Node Name=AU
XS GIS Cut Line= 3
590337.8207759664388903.93885032590322.4954317774388978.18203524
590327.2564078364388993.33059543
#Sta/Elev= 30
-149.967 1110.69-142.356    1110-138.747  1109.1-115.584    1104 -103.74 1102.94
 -88.648    1102  -54.56 1098.99 -21.883 1097.18  -6.824    1096  -4.921    1096
  -2.656 1094.06  -1.902 1093.87   -.819  1094.1    -.13 1095.14   3.217 1095.31
   4.921 1096.08    14.6 1097.45  20.112    1098  26.969    1098  39.075    1100
  60.039 1102.65  68.143    1104  75.295    1106  79.724 1106.56  84.711 1107.08
  91.699  1107.5  97.539    1108 126.936    1108 135.335    1110 148.458    1112
#Mann= 3 ,-1 , 0
-149.967     .12       0  -4.921    .042       0   4.921     .12       0
Bank Sta=-4.921,4.921
XS Rating Curve= 0 ,0
Exp/Cntr=0.5,0.3

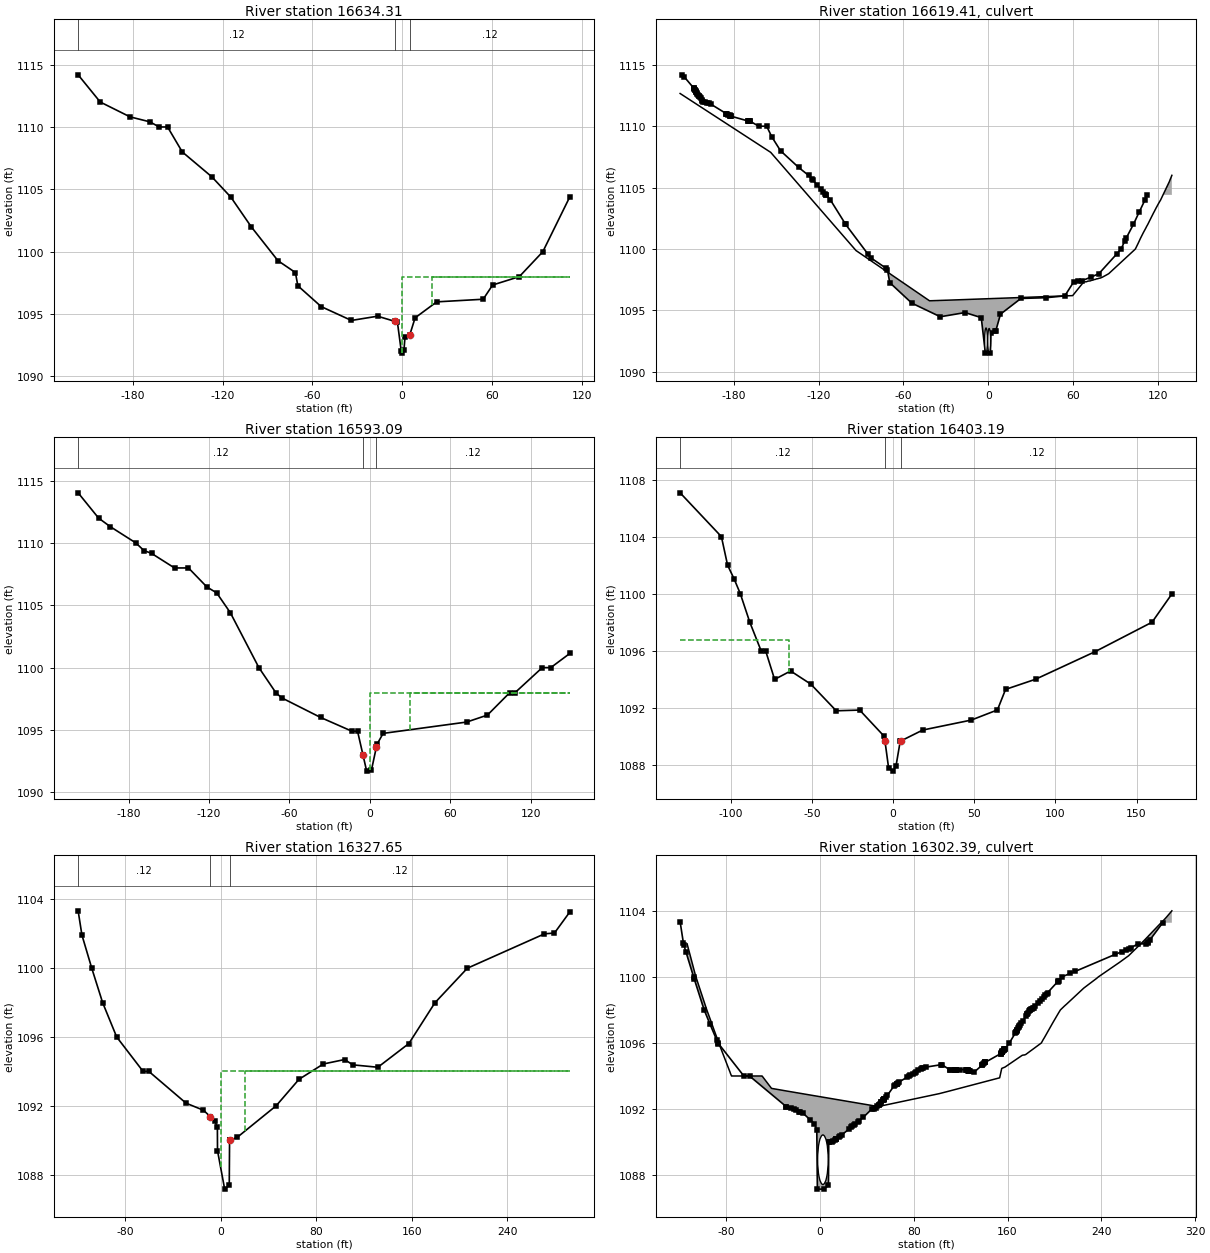
Type RM Length L Ch R = 1 ,16634.31,40.68,41.287,41.531
BEGIN DESCRIPTION:
POP_16 - Bradley Street - US
END DESCRIPTION:
XS GIS Cut Line= 4
590305.158407563  4388877.729098590294.1398874274388935.43383471
590286.8003033364388963.95092307 590291.17723139 4388975.0395472
#Sta/Elev= 30
-216.437 1114.18-201.673    1112-181.759 1110.81-168.471 1110.41-162.336    1110
-156.693    1110-146.883    1108  -127.1    1106-114.403 1104.37 -100.82    1102
 -82.972 1099.28 -71.325 1098.33 -69.685 1097.27 -54.101  1095.6 -33.924 1094.49
 -16.437 1094.83  -4.987 1094.42  -3.182 1094.35   -.656 1092.06    .098 1091.87
   1.181  1092.1    1.87 1093.14   4.987  1093.3   8.629  1094.7  23.064 1095.98
  54.101 1096.19    60.4 1097.33  78.215    1098   93.93    1100 112.008 1104.41
#Mann= 3 ,-1 , 0
-216.437     .12       0  -4.987    .042       0   4.987     .12       0
#XS Ineff= 2 , 0
       0     -30    1098      20       0    1098
Permanent Ineff=
       F       F
Bank Sta=-4.987,4.987
XS Rating Curve= 0 ,0
Exp/Cntr=0.5,0.3

Type RM Length L Ch R = 2 ,16619.41,,,
BEGIN DESCRIPTION:
POP_16 - Bradley Street
END DESCRIPTION:
Bridge Culvert--1,0,-1,-1, 0
Deck Dist Width WeirC Skew NumUp NumDn MinLoCord MaxHiCord MaxSubmerge Is_Ogee
11,20,2.6,0, 58, 58, , , 0.98, 0, 0,0,,
-217.881-153.839 -93.537 -41.568 -26.181  59.646  67.421  69.423   70.44  72.146
  73.163  73.917  74.967  75.656  76.706  77.297  78.412  78.937   80.02  80.052
  80.807  82.874  83.202  85.203  85.269  103.97 105.971 106.496 107.579 108.366
 109.547 111.614 111.844  112.73 115.026 116.864 117.487 117.946 118.241  118.57
 118.865  119.16  119.39 119.652 119.816 120.112 120.243 120.538 120.636 120.932
 121.227 121.555 121.719  121.85 128.018  128.51 129.101  129.79
 1112.66 1107.87 1099.88 1095.79 1095.85 1096.21 1097.32 1097.34 1097.39 1097.41
 1097.46 1097.47 1097.52 1097.53 1097.58 1097.58 1097.63 1097.63 1097.68 1097.68
 1097.72 1097.85 1097.87    1098 1098.01    1100 1100.47  1100.6 1100.87 1101.05
 1101.32 1101.76 1101.82    1102 1102.53 1102.95 1103.08 1103.19 1103.25 1103.33
 1103.39 1103.45  1103.5 1103.56 1103.59 1103.66 1103.68 1103.74 1103.76 1103.82
 1103.88 1103.94 1103.97    1104 1105.49 1105.64  1105.8    1106
                                                                                
                                                                                
                                                                                
                                                                                
                                                                                
                                                                
-217.881-153.839 -93.537 -41.568 -26.181  59.646  67.421  69.423   70.44  72.146
  73.163  73.917  74.967  75.656  76.706  77.297  78.412  78.937   80.02  80.052
  80.807  82.874  83.202  85.203  85.269  103.97 105.971 106.496 107.579 108.366
 109.547 111.614 111.844  112.73 115.026 116.864 117.487 117.946 118.241  118.57
 118.865  119.16  119.39 119.652 119.816 120.112 120.243 120.538 120.636 120.932
 121.227 121.555 121.719  121.85 128.018  128.51 129.101  129.79
 1112.66 1107.87 1099.88 1095.79 1095.85 1096.21 1097.32 1097.34 1097.39 1097.41
 1097.46 1097.47 1097.52 1097.53 1097.58 1097.58 1097.63 1097.63 1097.68 1097.68
 1097.72 1097.85 1097.87    1098 1098.01    1100 1100.47  1100.6 1100.87 1101.05
 1101.32 1101.76 1101.82    1102 1102.53 1102.95 1103.08 1103.19 1103.25 1103.33
 1103.39 1103.45  1103.5 1103.56 1103.59 1103.66 1103.68 1103.74 1103.76 1103.82
 1103.88 1103.94 1103.97    1104 1105.49 1105.64  1105.8    1106
                                                                                
                                                                                
                                                                                
                                                                                
                                                                                
                                                                
BR Coef=-1 , 0 , 0 ,, 0 ,,,0.8,-1,,0,
WSPro=,,,, 1 ,,,, 0 ,,,, 0 ,,,,-1 ,-1 ,-1 , 0 , 0 , 0 , 0 , 0
Culvert=1,2,,20,0.024,0.9,1,1,1,1091.57,-1.6,1091.33,-1.4,Culvert #1  , 0 ,10.5
Culvert Bottom n=0.024
Culvert=1,2,,20,0.024,0.9,1,1,1,1091.53,0.6,1091.43,0.8,Culvert #2  , 0 ,10.5
Culvert Bottom n=0.024
BR U #Sta/Elev= 86
-216.437 1114.18-214.862    1114-208.399 1113.12-208.333  1113.1-208.038 1113.05
-207.579 1112.98-207.152 1112.91-206.824 1112.85-206.594 1112.81-206.332 1112.77
-205.906  1112.7 -205.61 1112.65-204.921 1112.54 -204.56 1112.47-204.331 1112.43
-203.871 1112.36-203.314 1112.27-202.428 1112.12-202.067 1112.06-201.673    1112
-200.558    1112-198.786 1111.89-197.605 1111.85-195.965 1111.78-185.367 1111.03
-185.171 1111.02 -184.81    1111 -183.99 1110.95-182.644 1110.87-182.382 1110.85
-182.283 1110.85-182.054 1110.83-181.759 1110.81-170.079 1110.43-169.554 1110.43
-169.259 1110.42-168.734 1110.41-168.471 1110.41-162.336    1110-156.693    1110
-153.051 1109.13-146.883    1108-134.055 1106.64  -127.1    1106-124.902 1105.72
-124.049 1105.61-120.997 1105.23-118.373 1104.88-116.601 1104.66-115.584 1104.52
-114.895 1104.43-114.403 1104.37-111.647    1104-101.017 1102.04 -100.82    1102
 -85.007 1099.58 -82.972 1099.28 -72.671 1098.47 -71.325 1098.33 -69.685 1097.27
 -54.101  1095.6 -33.924 1094.49 -16.437 1094.83  -4.987 1094.42  -2.098 1091.57
   1.481 1091.53    1.87 1093.14   4.987  1093.3   5.217 1093.31   8.629  1094.7
  23.064 1095.98  40.748 1096.04  54.101 1096.19    60.4 1097.33  63.353 1097.42
  66.535 1097.44    72.9 1097.73  78.215    1098  90.814  1099.6   93.93    1100
   96.49 1100.67  97.507 1100.89 102.559    1102 106.594 1102.99 110.794    1104
 112.008 1104.41
BR U #Mann= 3
-216.437     .12  -4.987    .035   4.987     .12
BR D #Sta/Elev= 136
-217.585 1114.03-217.093    1114-214.895  1113.7-202.297    1112-193.668 1111.32
-191.699 1111.19 -190.42 1111.11-188.878    1111-186.942 1110.87 -184.35 1110.69
-179.692 1110.39-174.409    1110-169.948 1109.55-168.537  1109.4-162.828 1109.17
-159.646 1108.94-145.669    1108-135.236    1108-121.489 1106.47-120.341  1106.4
-119.587 1106.31-118.406 1106.25-117.126 1106.17-115.781 1106.09-115.584 1106.07
-114.206    1106-109.843 1105.39-109.383 1105.31-108.727 1105.21-108.563 1105.18
-108.366 1105.15-107.579 1105.02-107.448 1104.99-105.643 1104.69-105.315 1104.63
-104.954 1104.57-104.528 1104.49-104.035 1104.41 -102.92 1104.19-102.198 1104.05
-102.034 1104.02-101.936    1104-101.608 1103.94-101.542 1103.92-101.476 1103.91
-101.411  1103.9-101.345 1103.88-101.214 1103.86 -95.112 1102.61 -94.652 1102.51
 -94.127 1102.39 -92.487    1102 -92.257 1101.95 -92.192 1101.95 -92.126 1101.93
  -92.06 1101.92 -89.928 1101.51 -88.517 1101.25  -82.71    1100 -82.185 1099.93
 -80.446 1099.69 -70.144    1098 -65.814 1097.58 -43.602 1096.44 -43.307 1096.43
 -43.012 1096.41 -42.749 1096.39  -42.52 1096.38 -42.323 1096.36 -42.126 1096.35
 -38.714 1096.15  -36.68    1096  -34.81    1096 -26.903 1095.63 -24.114 1095.49
 -21.916 1095.33 -13.419  1094.9  -9.088 1094.89   -5.02 1092.98  -2.297 1091.33
   -.394 1091.33    2.28 1091.43    5.02 1093.65   5.413 1093.84  10.007 1094.72
  12.467 1094.72  13.583 1094.73  14.731 1094.73  16.962 1094.74  17.323 1094.73
  17.487 1094.73  26.542 1094.87  26.706 1094.88  27.034 1094.88  31.234    1095
  32.218 1095.02  34.941 1095.06  35.925 1095.09  38.911 1095.14  41.798  1095.2
  45.079 1095.26  47.047 1095.29  50.591 1095.36  52.297 1095.38  53.904 1095.38
  57.448 1095.46  59.416  1095.5  60.728  1095.5  64.764 1095.58  69.259 1095.66
  72.375 1095.63  74.311 1095.69  76.378 1095.76  82.251    1096    87.5 1096.18
  87.631 1096.18   87.73 1096.19  87.828 1096.19  87.927  1096.2  88.419 1096.23
  88.681 1096.25   88.78 1096.26  88.911 1096.27  90.157 1096.41  104.56    1098
  108.53    1098 117.848 1098.95  128.74    1100 135.105    1100 135.991 1100.12
 136.122 1100.12  136.22 1100.13 136.286 1100.13 138.025 1100.22 147.474 1100.96
 149.344 1101.14
BR D #Mann= 3
-217.585     .12   -5.02    .035    5.02     .12
BC Design=,, 0 ,, 0 ,,,,,,
BC Use User HTab Curves=0
BC User HTab FreeFlow(D)= 0

Type RM Length L Ch R = 1 ,16593.09,209.913,190.223,170.532
BEGIN DESCRIPTION:
POP_16 - Bradley Street - DS
END DESCRIPTION:
XS GIS Cut Line= 4
590293.1462394144388875.49186597 590282.246591284388932.57785868
590273.443967171 4388966.7672751590280.2044312544388983.89703531
#Sta/Elev= 30
-217.585 1114.03-202.297    1112-193.668 1111.32-174.409    1110-168.537  1109.4
-162.828 1109.17-145.669    1108-135.236    1108-121.489 1106.47-114.206    1106
-104.035 1104.41  -82.71    1100 -70.144    1098 -65.814 1097.58  -36.68    1096
 -13.419  1094.9  -9.088 1094.89   -5.02 1092.98  -2.297 1091.69    1.28 1091.77
    5.02 1093.65   5.413 1093.84  10.007 1094.72  72.375 1095.63  87.828 1096.19
  104.56    1098  108.53    1098  128.74    1100 135.105    1100 149.344 1101.14
#Mann= 3 ,-1 , 0
-217.585     .12       0   -5.02    .042       0    5.02     .12       0
#XS Ineff= 2 , 0
       0     -20    1098      30       0    1098
Permanent Ineff=
       F       F
Bank Sta=-5.02,5.02
XS Rating Curve= 0 ,0
Exp/Cntr=0.5,0.3

Type RM Length L Ch R = 1 ,16403.19,50.245,75.665,98.898
Node Name=AT
XS GIS Cut Line= 3
590193.7601021864388927.38406661590244.9604068194388966.15462709
590253.3454549224388992.97093142
#Sta/Elev= 28
-131.102 1107.07-105.676    1104 -101.87    1102 -97.867 1101.04 -94.029    1100
 -88.189    1098 -81.234    1096 -78.445    1096   -72.9 1093.99 -63.025 1094.58
 -50.623 1093.66 -34.941 1091.79 -20.505 1091.84  -5.315 1089.99  -4.921 1089.66
  -2.657 1087.76       0 1087.56   1.837  1087.9   4.462 1089.65   4.921 1089.68
   18.34 1090.44  48.261 1091.14  64.337 1091.85  69.357 1093.29  87.795    1094
 124.409 1095.93  159.58    1098 171.785 1099.98
#Mann= 3 ,-1 , 0
-131.102     .12       0  -4.921    .042       0   4.921     .12       0
#XS Ineff= 2 , 0
          -64.21 1096.73
Permanent Ineff=
       F       F
Bank Sta=-4.921,4.921
XS Rating Curve= 0 ,0
Exp/Cntr=0.5,0.3

Type RM Length L Ch R = 1 ,16327.65,89.131,65.232,48.964
BEGIN DESCRIPTION:
POP_15 - Hoffman Avenue - US
END DESCRIPTION:
XS GIS Cut Line= 6
590189.5660541344388938.19227475590209.3689103794388957.33066698
590206.461118343 4388975.0182112590204.4768703184389002.27037954
 590202.215254294389021.22589177590221.7072145314389048.57864411
#Sta/Elev= 30
-119.291 1103.34-116.109 1101.93-107.874    1100 -98.786    1098 -87.008    1096
 -64.928    1094 -60.105    1094 -28.937 1092.15  -14.37 1091.74   -8.53 1091.36
  -4.856 1091.12  -2.723 1090.74  -2.625 1089.39   3.379 1087.15   7.218 1087.37
    7.48    1090   7.972    1090  14.009 1090.17   46.49    1092  65.617 1093.54
  85.991 1094.43 103.871 1094.69 110.564 1094.38 131.627 1094.24 157.579 1095.62
 179.364 1097.99 206.496    1100 271.063    1102 279.462 1102.05 292.356 1103.28
#Mann= 3 ,-1 , 0
-119.291     .12       0   -8.53    .042       0   7.972     .12       0
#XS Ineff= 2 , 0
       0     -20    1094      20       0    1094
Permanent Ineff=
       F       F
Bank Sta=-8.53,7.972
XS Rating Curve= 0 ,0
Exp/Cntr=0.5,0.3

Type RM Length L Ch R = 2 ,16302.39,,,
BEGIN DESCRIPTION:
POP_15 - Hoffman Avenue
END DESCRIPTION:
Bridge Culvert--1,0,-1,-1, 0
Deck Dist Width WeirC Skew NumUp NumDn MinLoCord MaxHiCord MaxSubmerge Is_Ogee
4,52,2.6,0, 77, 77, , , , 0, 0,0,,
 -113.32 -106.07-105.774-104.856-103.445 -96.522  -93.11 -90.715 -88.353 -86.352
 -78.248 -76.706  -76.28 -75.427 -75.295 -74.934 -74.672 -74.213 -73.917 -73.852
 -73.819 -73.786 -73.753 -72.375 -69.685 -65.879 -53.642 -53.314 -53.018  -52.69
 -52.395 -51.739  -51.28  -50.23 -49.803 -49.377 -41.339 -30.052  -6.004  49.705
  101.64 109.318 153.248  155.02 157.808 172.441 173.031 173.622 174.213 175.459
 179.265 180.217 181.004 188.812 189.895 190.354  191.47 198.885  203.51 204.199
 205.052 208.563 210.466 224.967 230.906 235.958 237.434 255.479 263.222 273.589
 277.231 287.992 291.404 293.373 294.685 295.571 300.131
    1102 1100.06    1100  1099.8 1099.49    1098 1097.34 1096.86  1096.4    1096
 1094.51 1094.23 1094.14    1094    1094    1094    1094    1094    1094    1094
    1094    1094    1094    1094    1094    1094    1094    1094    1094    1094
    1094    1094    1094    1094    1094    1094 1093.25 1093.11 1092.82 1092.15
 1092.93 1093.07 1093.89 1094.46 1094.54 1095.25 1095.26 1095.27 1095.27  1095.3
  1095.5 1095.55 1095.59    1096 1096.14  1096.2 1096.33 1097.26 1097.82  1097.9
    1098 1098.24 1098.36 1099.32 1099.64 1099.91    1100 1100.88 1101.28    1102
 1102.26 1103.06 1103.31 1103.45 1103.55 1103.62    1104
                                                                                
                                                                                
                                                                                
                                                                                
                                                                                
                                                                                
                                                                                
                                                        
 -113.32 -106.07-105.774-104.856-103.445 -96.522  -93.11 -90.715 -88.353 -86.352
 -78.248 -76.706  -76.28 -75.427 -75.295 -74.934 -74.672 -74.213 -73.917 -73.852
 -73.819 -73.786 -73.753 -72.375 -69.685 -65.879 -53.642 -53.314 -53.018  -52.69
 -52.395 -51.739  -51.28  -50.23 -49.803 -49.377 -41.339 -30.052  -6.004  49.705
  101.64 109.318 153.248  155.02 157.808 172.441 173.031 173.622 174.213 175.459
 179.265 180.217 181.004 188.812 189.895 190.354  191.47 198.885  203.51 204.199
 205.052 208.563 210.466 224.967 230.906 235.958 237.434 255.479 263.222 273.589
 277.231 287.992 291.404 293.373 294.685 295.571 300.131
    1102 1100.06    1100  1099.8 1099.49    1098 1097.34 1096.86  1096.4    1096
 1094.51 1094.23 1094.14    1094    1094    1094    1094    1094    1094    1094
    1094    1094    1094    1094    1094    1094    1094    1094    1094    1094
    1094    1094    1094    1094    1094    1094 1093.25 1093.11 1092.82 1092.15
 1092.93 1093.07 1093.89 1094.46 1094.54 1095.25 1095.26 1095.27 1095.27  1095.3
  1095.5 1095.55 1095.59    1096 1096.14  1096.2 1096.33 1097.26 1097.82  1097.9
    1098 1098.24 1098.36 1099.32 1099.64 1099.91    1100 1100.88 1101.28    1102
 1102.26 1103.06 1103.31 1103.45 1103.55 1103.62    1104
                                                                                
                                                                                
                                                                                
                                                                                
                                                                                
                                                                                
                                                                                
                                                        
Culvert=5,3,9,52.6,0.024,0.9,1,41,3,1087.43,2.5,1085.76,0,Culvert #1  , 1 ,3
Culvert Bottom n=0.024
BR U #Sta/Elev= 175
-119.291 1103.34 -116.47 1102.04-116.109 1101.93-114.173 1101.48-107.874    1100
-107.185 1099.86 -98.786    1098  -93.93 1097.16 -87.992 1096.16 -87.008    1096
 -86.581 1095.96 -64.928    1094 -60.105    1094 -28.937 1092.15 -28.707 1092.14
 -24.705 1092.05 -21.752    1092 -20.768 1091.96 -17.717 1091.84 -17.323 1091.83
  -14.37 1091.74   -8.53 1091.36  -4.856 1091.12  -2.723 1090.74  -2.225 1087.15
   3.379 1087.15   7.218 1087.37    7.48    1090   7.972    1090  10.367    1090
  11.516 1090.05  12.894 1090.12   13.78 1090.16  13.911 1090.17  14.009 1090.17
  16.273  1090.3  17.421 1090.35  18.537 1090.43      25  1090.8  26.542  1090.9
  27.362 1090.95  29.232 1091.06  29.888 1091.09  32.119 1091.22  33.038 1091.28
  37.008  1091.5  44.193    1092   46.49    1092  47.408 1092.07   48.72 1092.16
  49.934 1092.25  50.033 1092.26  51.115 1092.33    52.1  1092.4  52.231 1092.41
  54.003 1092.53  54.134 1092.55  54.265 1092.56  54.429 1092.58   54.56 1092.59
  54.724  1092.6  56.496 1092.75  57.415 1092.82  63.156  1093.4  64.272 1093.46
  65.486 1093.53  65.551 1093.53  65.617 1093.54  66.896  1093.6  66.995 1093.61
   73.95 1093.92  75.853    1094  76.739 1094.04  79.101 1094.14  81.201 1094.21
  81.627 1094.26  83.596 1094.34  85.991 1094.43  86.975 1094.46  87.959 1094.48
  90.584 1094.54 103.543 1094.69 103.871 1094.69 110.564 1094.38  110.63 1094.38
 115.322 1094.35 115.486 1094.36 115.551 1094.36 115.617 1094.35 115.748 1094.36
 115.879 1094.36 119.521 1094.38 124.409 1094.39 124.639 1094.38 125.262 1094.37
 125.886 1094.35 126.115 1094.35 126.673 1094.33 127.067 1094.32 127.428 1094.31
 127.526 1094.31 127.592  1094.3 131.627 1094.24  138.32 1094.66 138.484 1094.67
 139.009  1094.7  140.19 1094.78 140.846 1094.82 140.945 1094.82 141.043 1094.83
  153.97 1095.35 154.035 1095.35 154.396 1095.39 155.052 1095.46 155.184 1095.46
 155.282 1095.47 155.348 1095.48 155.446 1095.48 155.512 1095.49 155.741 1095.49
 156.857  1095.6 156.988  1095.6 157.054 1095.61 157.283 1095.61 157.382 1095.62
 157.579 1095.62 161.516    1096 166.732 1096.61 167.126 1096.66  167.29 1096.69
 167.684 1096.73 168.143 1096.79 168.241  1096.8  168.93 1096.88 169.455 1096.94
 170.112 1097.01 170.833 1097.09 171.686 1097.19 172.736  1097.3 175.951 1097.65
 176.673 1097.73 176.903 1097.75 177.657 1097.83 178.478 1097.91 179.364 1097.99
 179.495    1098 180.249 1098.04  181.07 1098.08  181.89 1098.11 182.152 1098.12
 183.661 1098.24 185.663 1098.39   187.5 1098.54  189.37 1098.68 190.879  1098.8
 192.159 1098.89 193.241 1098.98 194.193 1099.05 202.789 1099.72  203.15 1099.75
 203.478 1099.77 206.496    1100 213.255 1100.21 217.913 1100.34 252.001 1101.37
 257.743 1101.53 261.089 1101.63 263.287 1101.69 264.862 1101.74 271.063    1102
 277.986    1102 279.462 1102.05  280.02 1102.11 281.234 1102.22 292.356 1103.28
BR U #Mann= 3
-119.291     .12   -8.53    .035   7.972     .12
BR D #Sta/Elev= 142
 -78.871 1099.94 -76.214 1099.75 -74.114 1099.56 -72.867 1099.47 -69.324 1099.16
 -58.563    1098 -51.214    1098 -50.951 1097.96 -50.886 1097.96 -50.525 1097.88
 -49.278 1097.66 -48.819 1097.58 -48.491 1097.51 -46.785 1097.22 -39.764 1095.94
 -39.764    1096 -36.975 1095.44   -35.4 1095.13 -34.875 1095.02 -34.186 1094.89
 -33.235  1094.7 -32.448 1094.54  -31.43 1094.34 -30.085 1094.07  -30.02 1094.06
 -28.839 1093.82 -27.854 1093.63 -27.723  1093.6 -27.559 1093.57 -26.673  1093.4
 -26.214 1093.31 -25.951 1093.26 -25.656  1093.2 -24.836 1093.04 -24.311 1092.95
 -23.163 1092.74 -22.703 1092.66 -22.178 1092.56 -21.818  1092.5  -21.26  1092.4
 -21.129 1092.38 -20.866 1092.33 -20.669  1092.3 -20.505 1092.27 -20.374 1092.25
 -20.243 1092.22 -20.112  1092.2  -19.98 1092.18 -19.882 1092.16 -19.816 1092.15
 -18.898    1092  -8.924 1090.47  -8.202 1090.15  -4.921 1087.25    -4.5 1085.76
  -2.526 1085.11    .033 1085.04   1.378 1084.97     4.5 1085.76   4.921 1087.62
   8.366 1090.18   8.957 1091.29  10.105    1092  21.654    1092  23.228  1092.1
  23.327  1092.1  26.345 1092.13  26.476 1092.13  29.429 1092.15  29.626 1092.15
  34.449 1092.18  34.547 1092.18  36.056 1092.19  36.155 1092.19  37.631  1092.2
  39.337  1092.2  40.814 1092.21  44.127 1092.21  45.571 1092.22  47.047 1092.22
  48.852 1092.21   68.11 1092.28  69.619 1092.28  72.933 1092.33  79.495 1092.36
  81.791 1092.39  81.923 1092.39  82.021  1092.4  82.448  1092.4  88.615 1092.51
 104.396 1093.31 112.598 1093.56 112.828 1093.57 115.879 1093.61 136.417 1093.99
 136.483 1093.99 136.909    1094 137.762    1094 138.058 1094.01 141.142 1094.05
 142.651 1094.06 142.782 1094.07 144.291 1094.08 145.801  1094.1 145.997  1094.1
 147.507 1094.12  148.95 1094.15 149.278 1094.15 153.445 1094.21 153.904 1094.22
 154.692 1094.23 156.168 1094.27  156.89 1094.28  167.29 1094.93 168.963 1095.01
 173.392  1095.2 173.622 1095.23 174.573 1095.27 174.869  1095.3 175.689 1095.34
 176.444 1095.37 177.625 1095.47  178.15  1095.5 180.741 1095.77 183.268    1096
 196.096    1096 198.031 1096.11 203.314 1096.47 220.013    1098  223.72 1098.41
  224.77 1098.52 226.608 1098.69 230.282 1099.05 237.762 1099.81  240.19    1100
 247.474 1100.52 262.762    1102 275.197 1103.01 284.449 1103.69  288.78    1104
 294.718 1104.51 300.886  1105.1
BR D #Mann= 3
 -78.871     .12  -4.921    .035   4.921     .12
BC Design=,, 0 ,, 0 ,,,,,,
BC Use User HTab Curves=0
BC User HTab FreeFlow(D)= 0