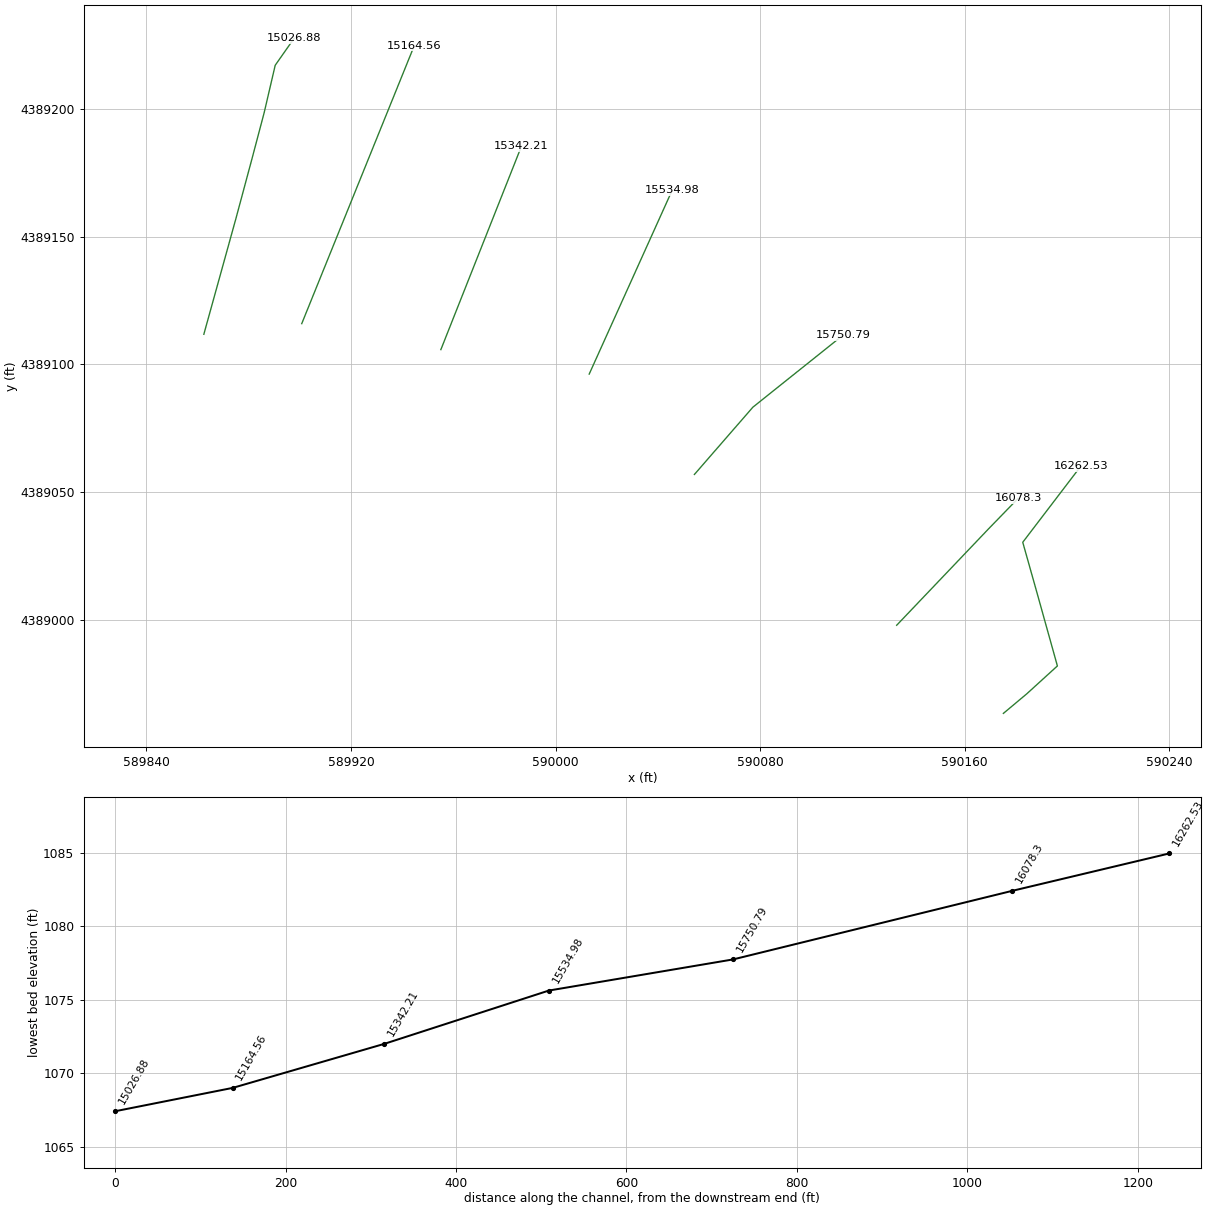
HEC-RAS study Pompono_Run_Detail_Study.prj: Pompono_Run_Detail_Study

--- Pompono_Run_Detail_Study.g01 (geometry) --- (continued)

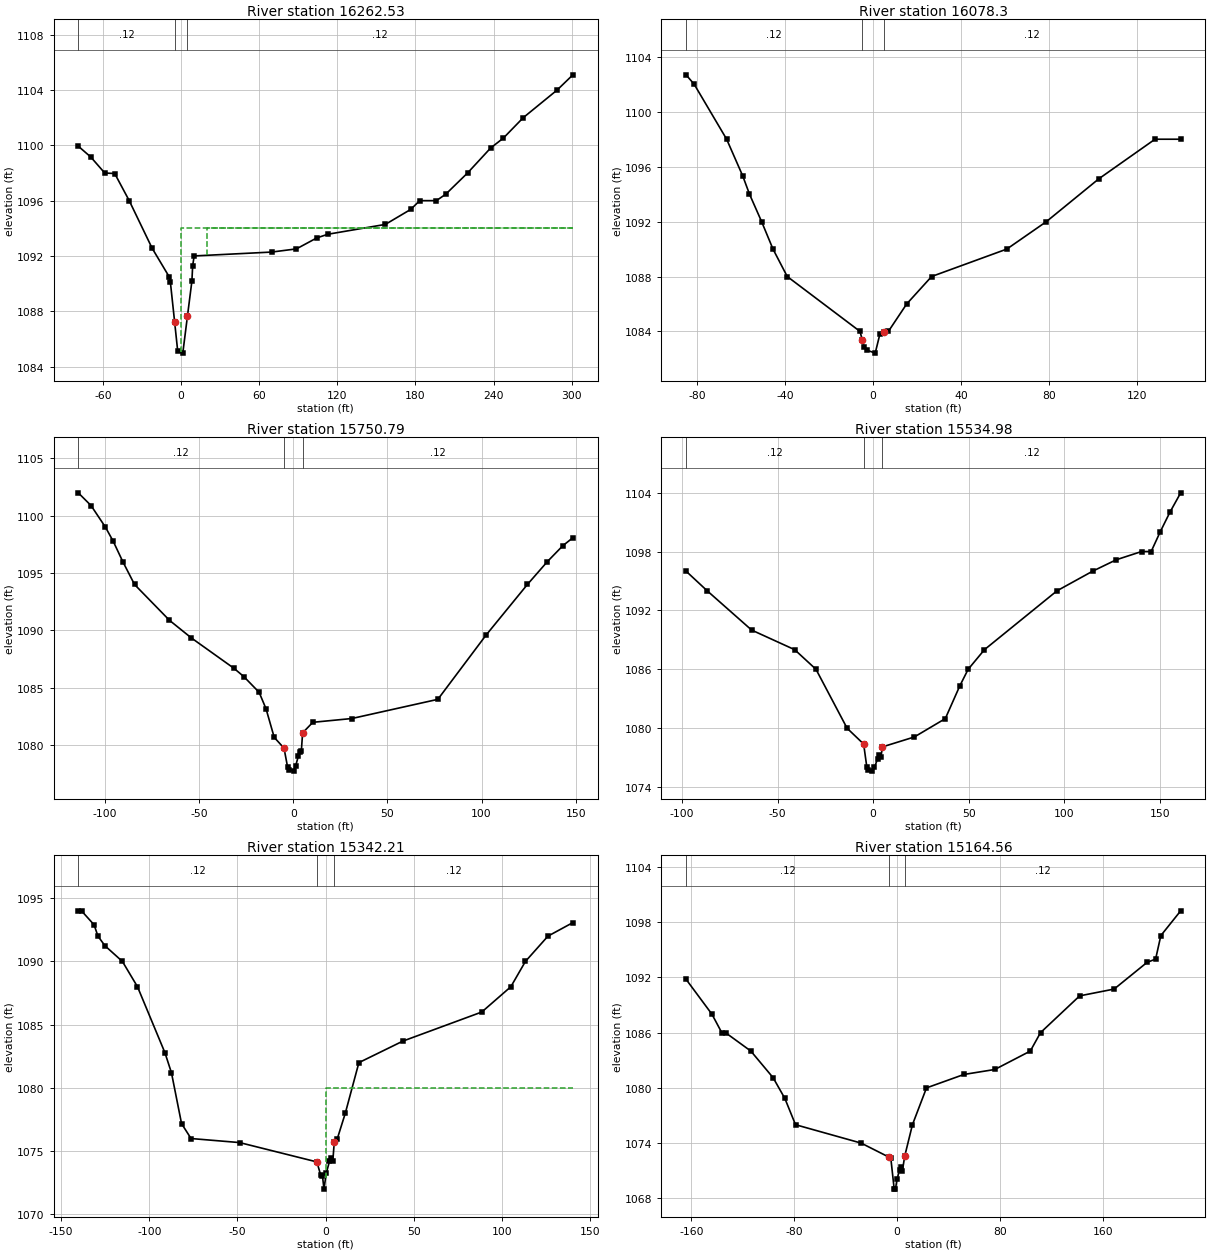
Type RM Length L Ch R = 1 ,16262.53,183.38,184.54,180.259
BEGIN DESCRIPTION:
POP_15 - Hoffman Avenue - DS
END DESCRIPTION:
XS GIS Cut Line= 6
590175.1581579564388963.52725106590184.3052060694388971.17468316
590196.2747022174388982.07737929590188.1243501164389011.28636365
 590182.726342054389030.44304389 590205.421750334389060.18542826
#Sta/Elev= 30
 -78.871 1099.94 -69.324 1099.16 -58.563    1098 -50.886 1097.96 -39.764    1096
 -22.178 1092.56  -8.924 1090.47  -8.202 1090.15  -4.921 1087.25  -2.526 1085.11
   1.378 1084.97   4.921 1087.62   8.366 1090.18   8.957 1091.29  10.105    1092
  69.619 1092.28  88.615 1092.51 104.396 1093.31 112.828 1093.57  156.89 1094.28
 176.444 1095.37 183.268    1096 196.096    1096 203.314 1096.47 220.013    1098
 237.762 1099.81 247.474 1100.52 262.762    1102  288.78    1104 300.886  1105.1
#Mann= 3 ,-1 , 0
 -78.871     .12       0  -4.921    .042       0   4.921     .12       0
#XS Ineff= 2 , 0
       0     -20    1094      20       0    1094
Permanent Ineff=
       F       F
Bank Sta=-4.921,4.921
XS Rating Curve= 0 ,0
Exp/Cntr=0.5,0.3

Type RM Length L Ch R = 1 ,16078.3 ,326.728,327.51,325.305
Node Name=AS
XS GIS Cut Line= 3
 590133.424941444388997.98793949590169.6991898894389036.05136396
590180.882302027 4389047.5606121
#Sta/Elev= 23
 -85.171 1102.69 -81.463    1102 -66.699    1098 -59.383 1095.33 -56.299    1094
 -50.787    1092 -45.604    1090 -39.108    1088  -5.971    1084  -4.921 1083.35
  -4.134 1082.88   -2.71 1082.63     .93 1082.42    3.04 1083.79   4.921 1083.96
   6.923    1084  15.256    1086  26.608    1088   60.86    1090  78.871    1092
 102.756 1095.12 128.314    1098 139.993    1098
#Mann= 3 ,-1 , 0
 -85.171     .12       0  -4.921    .042       0   4.921     .12       0
Bank Sta=-4.921,4.921
XS Rating Curve= 0 ,0
Exp/Cntr=0.3,0.1

Type RM Length L Ch R = 1 ,15750.79,211.407,216.178,223.936
Node Name=AR
XS GIS Cut Line= 3
590054.3171484634389056.96064422590077.1801967454389083.25878854
590112.5248051824389111.51070089
#Sta/Elev= 30
-114.272 1101.98 -107.48 1100.87 -99.836 1098.99 -95.702 1097.76  -90.65    1096
 -84.383    1094 -65.814 1090.88 -54.134 1089.34 -31.463 1086.69 -26.247 1085.97
 -18.176 1084.61 -14.501 1083.17 -10.171 1080.69   -4.96 1079.75   -3.03 1078.08
    -2.2 1077.88     .11 1077.75    1.15 1078.17    2.67 1079.06    3.49 1079.44
    4.23 1079.46   4.921 1081.08  10.335    1082   31.07 1082.33  76.772    1084
 102.329 1089.58 124.344    1094 135.007    1096 143.209 1097.38 148.524 1098.07
#Mann= 3 ,-1 , 0
-114.272     .12       0   -4.96    .042       0   4.921     .12       0
Bank Sta=-4.96,4.921
XS Rating Curve= 0 ,0
Exp/Cntr=0.3,0.1

Type RM Length L Ch R = 1 ,15534.98,192.329,193.094,193.859
Node Name=AQ
XS GIS Cut Line= 2
590013.175243954 4389096.2127887590045.6394923554389168.14558959
#Sta/Elev= 28
 -97.867    1096 -86.811    1094  -63.55    1090  -41.01    1088 -29.856    1086
 -13.583    1080  -4.921 1078.39   -3.25 1076.04   -2.51 1075.78    -.44 1075.63
     .73    1076    2.42 1076.91    3.34 1077.25    4.16 1077.12   4.921  1078.1
  21.621 1079.11  37.828 1080.98  45.374  1084.3   49.77    1086  58.301    1088
  96.293    1094 114.961    1096 127.297 1097.16 140.551    1098 145.571    1098
 150.295    1100 155.381    1102 161.024 1103.98
#Mann= 3 ,-1 , 0
 -97.867     .12       0  -4.921    .038       0   4.921     .12       0
Bank Sta=-4.921,4.921
XS Rating Curve= 0 ,0
Exp/Cntr=0.3,0.1

Type RM Length L Ch R = 1 ,15342.21,178.073,177.956,177.839
Node Name=AP
XS GIS Cut Line= 2
589955.1626592374389105.78046082589986.675931627 4389185.3027818
#Sta/Elev= 30
-140.322    1094-138.484    1094-131.332 1092.89-129.167    1092-125.197 1091.24
-115.289    1090-106.726    1088 -91.142 1082.78 -87.434 1081.19 -81.726 1077.18
 -76.345    1076 -48.786 1075.68  -4.921 1074.15   -2.77  1073.1   -1.78 1073.06
    -.91    1072     .36 1073.25     2.2 1074.19    3.21  1074.5     4.1 1074.23
   4.921  1075.7   6.693    1076  11.188    1078  18.898    1082  43.832  1083.7
  88.615    1086 105.118    1088 113.386    1090 126.181    1092 140.322 1093.07
#Mann= 3 ,-1 , 0
-140.322     .12       0  -4.921     .04       0   4.921     .12       0
#XS Ineff= 2 , 0
       0    -120    1080               0
Permanent Ineff=
       F       F
Bank Sta=-4.921,4.921
XS Rating Curve= 0 ,0
Exp/Cntr=0.3,0.1

Type RM Length L Ch R = 1 ,15164.56,135.865,137.911,140.006
Node Name=AO
XS GIS Cut Line= 2
589900.7589065654389115.94249294589944.7232591084389224.56102229
#Sta/Elev= 30
-164.075  1091.8 -143.93    1088-136.319    1086-133.399    1086-113.714    1084
 -96.424 1081.11  -87.27 1078.85 -79.003    1076 -27.953    1074  -6.299 1072.47
  -4.921 1072.35    -2.3    1069   -1.36    1069     .01 1070.15       2 1071.11
    3.08  1071.4    4.05 1070.99   5.938 1072.62  11.877    1076  22.802    1080
  51.903 1081.46  75.886    1082 103.478    1084 111.417    1086 141.864    1090
 168.668 1090.74  194.16 1093.63 200.886    1094 204.954 1096.55 220.374 1099.24
#Mann= 3 ,-1 , 0
-164.075     .12       0  -6.299     .04       0   5.938     .12       0
Bank Sta=-6.299,5.938
XS Rating Curve= 0 ,0
Exp/Cntr=0.5,0.3

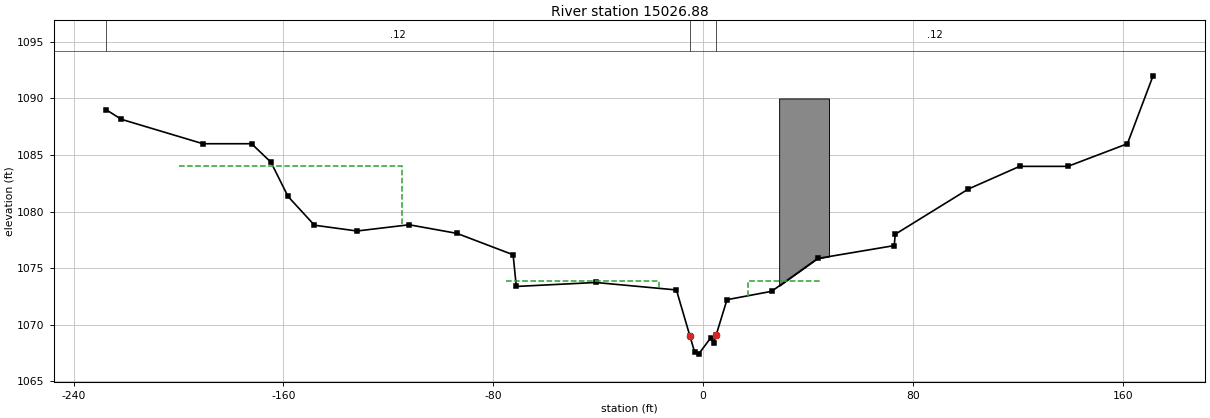
Type RM Length L Ch R = 1 ,15026.88,207.476,187.64,175.338
BEGIN DESCRIPTION:
POP_14 - Willowdale Rd - US
END DESCRIPTION:
XS GIS Cut Line= 6
589862.4729780924389111.79111689589874.9911142464389156.94723745
589881.2578023244389180.26748574589886.0492583834389198.39089396
589890.3835144364389216.99283819589897.7749145284389227.51758232
#Sta/Elev= 30
-227.723 1089.02 -221.85 1088.16-190.715    1086-172.178    1086-164.797 1084.37
-158.268 1081.34-148.196  1078.8-131.955 1078.29-112.073 1078.84 -93.865 1078.08
 -72.441 1076.19 -71.227 1073.39 -40.945 1073.74 -10.171 1073.08   -5.02 1069.01
  -3.215 1067.58  -1.706 1067.41   2.986 1068.87   4.003 1068.36    5.02 1069.13
   9.121 1072.22  26.148 1072.96  43.668 1075.86    72.9    1077  73.261    1078
 101.181    1082 120.702    1084 139.108    1084 161.811    1086 171.588    1092
#Mann= 3 ,-1 , 0
-227.723     .12       0   -5.02    .038       0    5.02     .12       0
#XS Ineff= 3 ,-1
     -75     -17  1073.9    -200    -115    1084      17      45  1073.9
Permanent Ineff=
       F       F       F
#Block Obstruct= 1 ,-1
      29      48    1090
Bank Sta=-5.02,5.02
XS Rating Curve= 0 ,0
Minor Loss Coefficient=0.5
Exp/Cntr=0.5,0.3