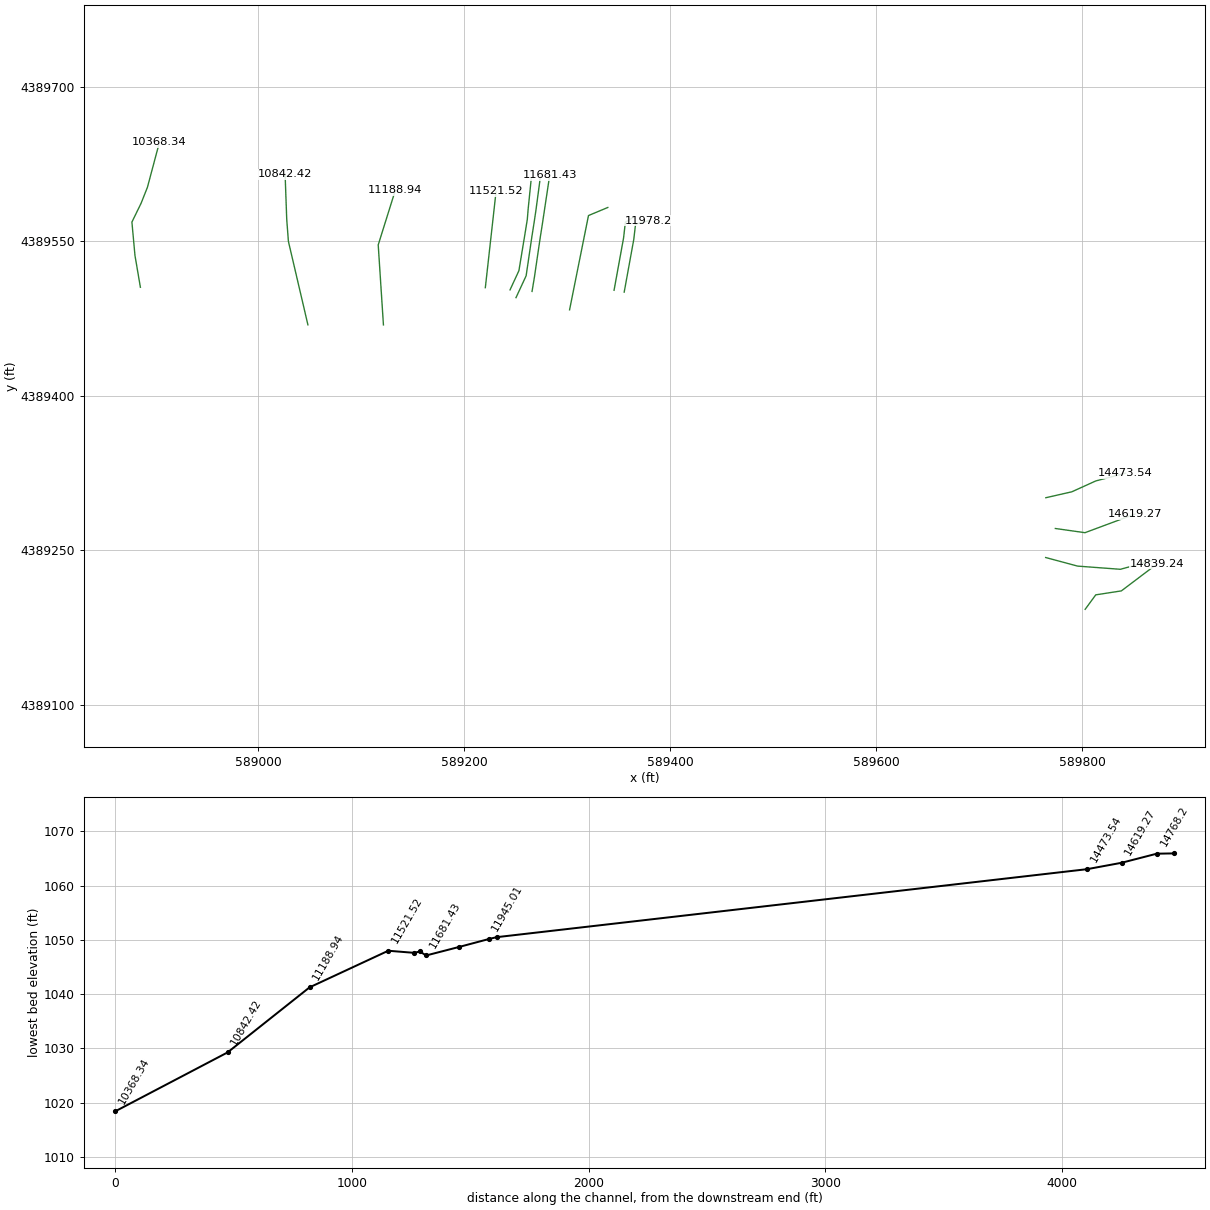
HEC-RAS study Pompono_Run_Detail_Study.prj: Pompono_Run_Detail_Study

--- Pompono_Run_Detail_Study.g01 (geometry) --- (continued)

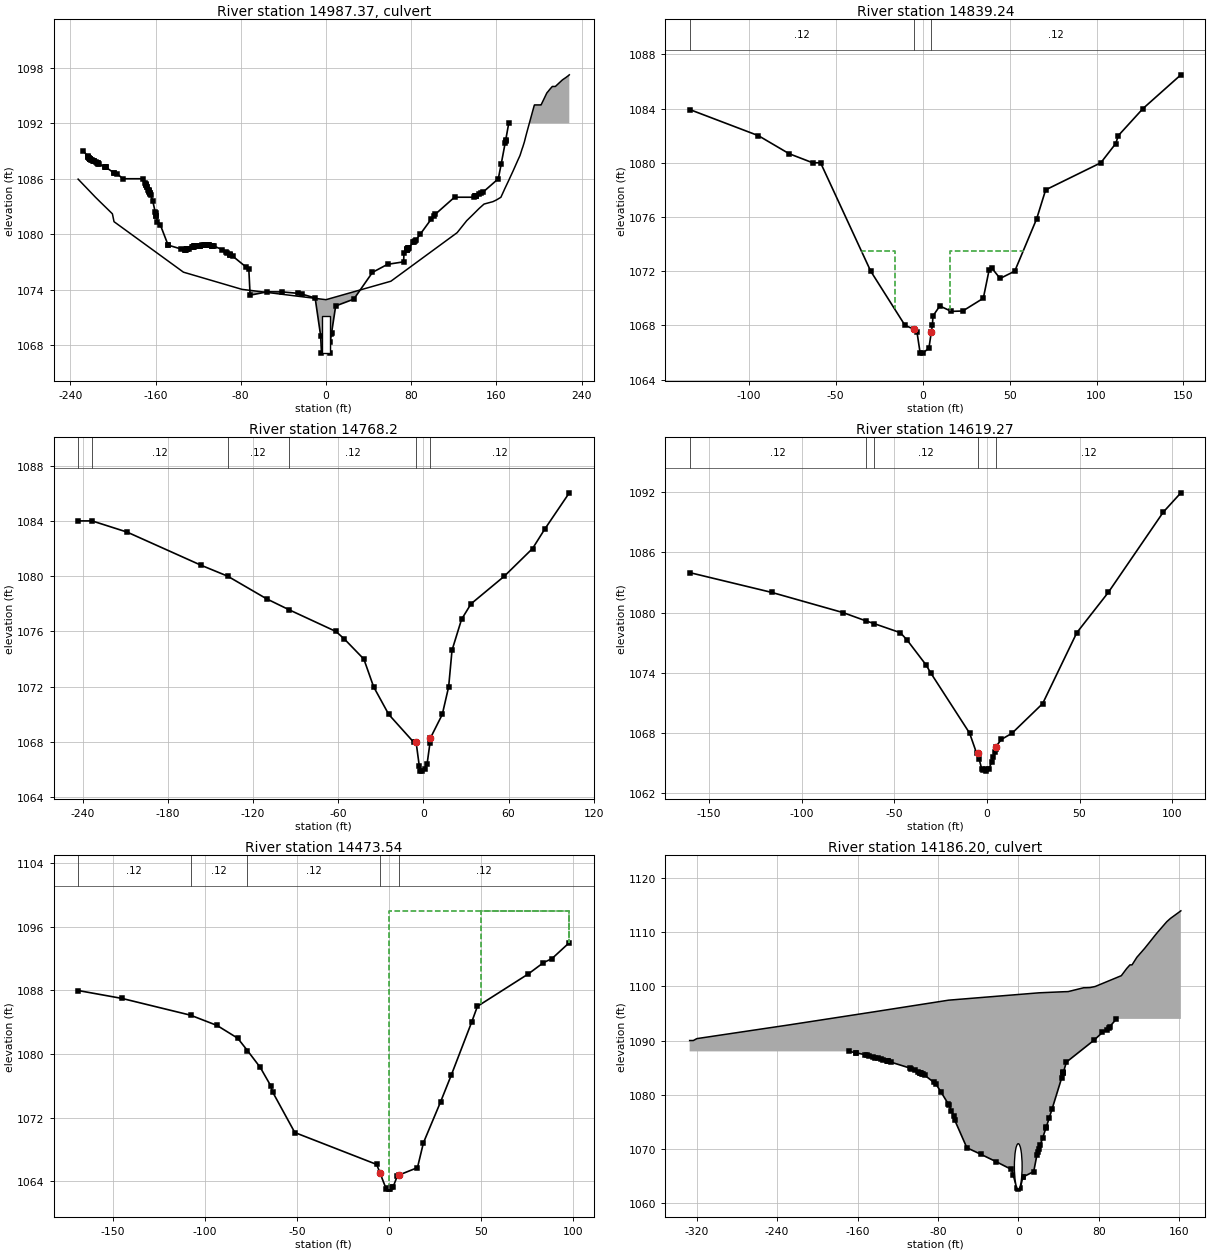
Type RM Length L Ch R = 2 ,14987.37,,,
BEGIN DESCRIPTION:
POP_14 - Willowdale Rd
END DESCRIPTION:
Bridge Culvert--1,0,-1,-1, 0
Deck Dist Width WeirC Skew NumUp NumDn MinLoCord MaxHiCord MaxSubmerge Is_Ogee
19,115,2.6,0, 86, 86, , , , 0, 0,0,,
-232.743-218.865 -216.47-212.959-211.089-204.954-200.525-199.016-133.825 -78.937
       0  60.958 123.163 132.152 136.975 143.865 148.425 156.759 158.169 158.957
 159.219 160.007  160.86 161.745 161.877 164.173 164.272 164.337 164.501 164.829
 164.895 165.059 165.354 165.518 165.617 165.781 165.945 166.207 166.503 166.929
  167.52  171.26 175.787 180.118 182.185  184.35 184.875 186.319 187.303 187.402
   187.5 188.812 195.505 195.669 195.735 195.833 197.408 198.031 198.491 198.885
  199.18 199.442 199.836 200.131 200.394  200.82 201.115 201.509 201.969 207.349
 208.071 208.104 208.596 209.383 209.711 210.531 211.516 211.614 211.713   212.5
 215.387 221.982 225.656  226.28 227.395 228.478
 1085.96 1084.29    1084  1083.6 1083.39  1082.7  1082.2 1081.35 1075.88 1074.02
  1072.9  1074.9 1080.16 1081.46    1082 1082.79 1083.26 1083.52  1083.6 1083.64
 1083.66  1083.7 1083.76 1083.82 1083.83 1083.99    1084 1084.01 1084.06 1084.14
 1084.16  1084.2 1084.28 1084.31 1084.34 1084.38 1084.43 1084.49 1084.57 1084.67
 1084.83 1085.74 1086.87    1088 1088.52  1089.3 1089.46    1090 1090.45 1090.49
 1090.54 1091.11 1093.93 1093.98 1093.98    1094    1094    1094    1094    1094
    1094    1094    1094    1094    1094    1094    1094    1094    1094 1095.29
  1095.4  1095.4 1095.46 1095.58 1095.62 1095.74 1095.87 1095.88 1095.89    1096
    1096 1096.71    1097 1097.06 1097.15 1097.26
                                                                                
                                                                                
                                                                                
                                                                                
                                                                                
                                                                                
                                                                                
                                                                                
                                                
-232.743-218.865 -216.47-212.959-211.089-204.954-200.525-199.016-133.825 -78.937
       0  60.958 123.163 132.152 136.975 143.865 148.425 156.759 158.169 158.957
 159.219 160.007  160.86 161.745 161.877 164.173 164.272 164.337 164.501 164.829
 164.895 165.059 165.354 165.518 165.617 165.781 165.945 166.207 166.503 166.929
  167.52  171.26 175.787 180.118 182.185  184.35 184.875 186.319 187.303 187.402
   187.5 188.812 195.505 195.669 195.735 195.833 197.408 198.031 198.491 198.885
  199.18 199.442 199.836 200.131 200.394  200.82 201.115 201.509 201.969 207.349
 208.071 208.104 208.596 209.383 209.711 210.531 211.516 211.614 211.713   212.5
 215.387 221.982 225.656  226.28 227.395 228.478
 1085.96 1084.29    1084  1083.6 1083.39  1082.7  1082.2 1081.35 1075.88 1074.02
  1072.9  1074.9 1080.16 1081.46    1082 1082.79 1083.26 1083.52  1083.6 1083.64
 1083.66  1083.7 1083.76 1083.82 1083.83 1083.99    1084 1084.01 1084.06 1084.14
 1084.16  1084.2 1084.28 1084.31 1084.34 1084.38 1084.43 1084.49 1084.57 1084.67
 1084.83 1085.74 1086.87    1088 1088.52  1089.3 1089.46    1090 1090.45 1090.49
 1090.54 1091.11 1093.93 1093.98 1093.98    1094    1094    1094    1094    1094
    1094    1094    1094    1094    1094    1094    1094    1094    1094 1095.29
  1095.4  1095.4 1095.46 1095.58 1095.62 1095.74 1095.87 1095.88 1095.89    1096
    1096 1096.71    1097 1097.06 1097.15 1097.26
                                                                                
                                                                                
                                                                                
                                                                                
                                                                                
                                                                                
                                                                                
                                                                                
                                                
Culvert=2,4,8,153,0.013,0.5,1,8,1,1067.11,0,1065.92,0,Culvert #1  , 1 ,18
Culvert Bottom n=0.013
BR U #Sta/Elev= 151
-227.723 1089.02-223.852 1088.43 -223.36 1088.35-223.163 1088.33-222.933 1088.29
-222.736 1088.26 -221.85 1088.16-221.752 1088.16-221.654 1088.15-221.588 1088.15
-220.276 1088.06-219.357    1088-218.832 1087.97-217.881 1087.91-217.421 1087.88
-216.142  1087.8-215.059 1087.73 -214.37 1087.68-214.108 1087.67-213.648 1087.63
-213.451  1087.6-207.546 1087.31-207.087 1087.28-206.923 1087.26-206.759 1087.25
-198.885 1086.62-198.819 1086.62-195.932 1086.53-190.715    1086-172.178    1086
-169.587 1085.52-169.259 1085.44-168.832 1085.34-168.602 1085.29-167.979 1085.13
-167.749 1085.08-166.765 1084.83-166.371 1084.75 -166.24 1084.71-166.076 1084.68
-165.814 1084.62-165.223 1084.48-164.993 1084.41-164.797 1084.37-164.534 1084.29
-162.598 1083.56-160.335  1082.4-160.039 1082.26-159.547    1082-159.416 1081.93
-158.268 1081.34-155.479 1080.99-148.196  1078.8  -147.9  1078.8-135.991 1078.39
-132.087 1078.29-131.955 1078.29-131.857  1078.3 -131.07 1078.34-130.906 1078.35
-130.774 1078.35-130.446 1078.37-130.118 1078.38 -128.97 1078.44-125.984 1078.57
-125.262 1078.61-124.934 1078.62-124.278 1078.66 -123.95 1078.67-123.655 1078.69
-123.327  1078.7-123.261 1078.71-122.933 1078.72-119.062 1078.72-118.635 1078.73
-118.241 1078.74-117.848 1078.76-116.076 1078.81-114.534 1078.84 -113.55 1078.85
-112.566 1078.84-112.073 1078.84-110.991 1078.82-110.827 1078.82-109.744  1078.8
 -109.58  1078.8-107.349 1078.76-107.185 1078.75-107.021 1078.75 -105.84 1078.72
-105.512 1078.72 -97.375 1078.32 -93.865 1078.08 -92.749    1078 -90.354 1077.81
 -89.961 1077.79 -89.731 1077.78 -87.697 1077.63 -75.066 1076.43 -72.441 1076.19
 -71.227 1073.39 -55.184 1073.75 -40.945 1073.74 -26.411 1073.59 -22.113 1073.49
 -10.171 1073.08   -5.02 1069.01  -4.215 1067.11   4.004 1067.11    4.01 1068.36
    5.02 1069.13   5.217 1069.28   9.121 1072.22  26.148 1072.96  43.668 1075.86
  57.808 1076.73    72.9    1077  73.261    1078  75.656 1078.28  75.787  1078.3
  75.984 1078.32  76.214 1078.35  76.476 1078.39  76.804 1078.43  77.198 1078.48
  77.461 1078.52  77.723 1078.55  82.054  1079.1   82.71 1079.18  83.793 1079.29
  84.252 1079.33   88.55    1080   98.72 1081.62 101.181    1082  102.69 1082.16
 120.702    1084 139.108    1084 139.961 1084.09 140.322 1084.11 140.518 1084.11
 140.978 1084.13 141.273 1084.15 143.898 1084.31 145.801 1084.44 147.474 1084.55
 161.811    1086 164.469 1087.56 168.307 1089.89  168.57 1090.08 168.766 1090.19
 171.588    1092
BR U #Mann= 3
-227.723     .12   -5.02    .035    5.02     .12
BR D #Sta/Elev= 96
-134.022 1083.93-131.168 1083.85-130.741 1083.83-130.545 1083.82-130.315 1083.81
 -94.488    1082  -83.53 1081.02 -76.837 1080.67 -63.287    1080 -58.727    1080
 -52.264 1078.22 -51.509    1078 -48.261  1077.1 -40.945 1075.06 -39.534 1074.66
 -37.073    1074 -32.743 1072.77 -32.382 1072.67 -32.119 1072.59  -31.89 1072.53
 -31.693 1072.48 -31.562 1072.44  -31.43  1072.4 -29.888    1072  -28.51 1071.73
 -27.953 1071.61 -26.476  1071.3 -24.606 1070.92 -23.556 1070.71   -22.9 1070.58
 -20.407    1070  -12.73 1068.53 -10.171    1068  -7.283    1068  -4.921 1067.71
  -4.081 1065.92   4.026 1065.92   4.954 1067.49    5.61 1068.03   5.906 1068.69
   6.693 1068.93   6.955    1069   7.119 1069.05   7.448 1069.13   7.612 1069.16
   8.038 1069.25   9.843 1069.43  16.535 1069.03  16.896 1069.05  17.224 1069.06
   17.52 1069.08  17.913  1069.1  18.077  1069.1  23.064 1069.06  34.875    1070
  38.156 1072.05  39.698 1072.24  44.521 1071.46  51.115 1071.88    52.1 1071.91
  52.953    1072  63.451 1075.22  65.551 1075.86  70.735    1078  88.944 1079.27
  89.206 1079.29  90.125 1079.35  90.551 1079.38  90.945  1079.4  91.404 1079.43
  91.896 1079.46  91.962 1079.46  92.454 1079.49  94.029 1079.58  94.587 1079.61
  96.719 1079.72  96.818 1079.72  96.982 1079.74 100.984    1080 102.461    1080
 102.756 1080.04 102.822 1080.05 105.052 1080.36 106.201 1080.61 106.398 1080.66
 111.056 1081.42   112.5    1082 113.025 1082.07 126.706    1084 130.052 1084.41
 131.594 1084.57 132.579 1084.69 136.483 1085.12 139.862  1085.5 144.488    1086
 148.491 1086.49
BR D #Mann= 3
-134.022     .12  -4.921    .035   4.954     .12
BC Design=,, 0 ,, 0 ,,,,,,
BC Use User HTab Curves=0
BC User HTab FreeFlow(D)= 0

Type RM Length L Ch R = 1 ,14839.24,74.789,71.164,65.936
BEGIN DESCRIPTION:
POP_14 - Willowdale Rd - DS
END DESCRIPTION:
XS GIS Cut Line= 4
589802.7718013544389192.65455789589813.0831854814389206.70583807
589837.9152417884389210.54936611589872.6715862184389236.78959844
#Sta/Elev= 30
-134.022 1083.93 -94.488    1082 -76.837 1080.67 -63.287    1080 -58.727    1080
 -29.888    1072 -10.171    1068  -4.921 1067.71  -3.281 1067.51  -1.476 1065.97
       0 1065.95   3.576 1066.31   4.954 1067.49    5.61 1068.03   5.906 1068.69
   9.843 1069.43  16.535 1069.03  23.064 1069.06  34.875    1070  38.156 1072.05
  39.698 1072.24  44.521 1071.46  52.953    1072  65.551 1075.86  70.735    1078
 102.461    1080 111.056 1081.42   112.5    1082 126.706    1084 148.491 1086.49
#Mann= 3 ,-1 , 0
-134.022     .12       0  -4.921    .038       0   4.954     .12       0
#XS Ineff= 2 ,-1
  -34.71     -16  1073.5      16  58.491  1073.5
Permanent Ineff=
       F       F
Bank Sta=-4.921,4.954
XS Rating Curve= 0 ,0
Minor Loss Coefficient=0.5
Exp/Cntr=0.5,0.3

Type RM Length L Ch R = 1 ,14768.2 ,142.382,149.189,150.656
Node Name=AN
XS GIS Cut Line= 4
  589764.4706329 4389242.9343665  589795.4809853 4389234.6011344
  589836.9612178 4389231.5074144  589867.5783782 4389239.8802705
#Sta/Elev= 30
-243.209    1084-233.399    1084-208.694 1083.19-156.562 1080.79-137.828    1080
-110.367 1078.36 -94.783 1077.58 -61.581    1076 -55.709 1075.46 -41.929    1074
 -35.072    1072 -24.409    1070  -6.923    1068  -5.151    1068   -2.91 1066.27
    -2.4 1065.94    -.89  1065.9     .78 1066.09    2.63 1066.44     4.6 1067.92
   4.921 1068.29  13.287    1070  17.782    1072  20.144 1074.64   26.87 1076.88
   33.53    1078  56.988    1080   76.87    1082  85.367 1083.39 102.756 1086.03
#Mann= 6 ,-1 , 0
-243.209     .12       0-233.399     .12       0-137.828     .12       0
 -94.783     .12       0  -5.151    .038       0   4.921     .12       0
Bank Sta=-5.151,4.921
XS Rating Curve= 0 ,0
Exp/Cntr=0.3,0.1

Type RM Length L Ch R = 1 ,14619.27,144.794,145.97,144.116
Node Name=AM
XS GIS Cut Line= 3
   589773.873713 4389271.1070309  589802.5919694 4389267.0227108
    589851.11613  4389285.069919
#Sta/Elev= 30
-160.367 1083.98-115.912    1082 -77.625    1080  -65.19 1079.17 -60.794  1078.9
 -46.719    1078 -43.143 1077.29 -32.776 1074.78 -30.315    1074  -9.318    1068
  -5.545    1066  -4.921 1066.03   -4.17  1065.4   -2.78 1064.44   -2.24 1064.31
    -.67 1064.22     -.3  1064.4     .96 1064.44    2.75 1065.14    3.43 1065.62
    4.59 1066.13    4.82 1066.41   4.921 1066.67   7.776 1067.37   13.55 1067.99
  30.085 1070.94  48.524    1078  65.486    1082  95.177    1090 104.659 1091.92
#Mann= 5 ,-1 , 0
-160.367     .12       0  -65.19     .12       0 -60.794     .12       0
  -4.921    .038       0   4.921     .12       0
Bank Sta=-4.921,4.921
XS Rating Curve= 0 ,0
Exp/Cntr=0.5,0.3

Type RM Length L Ch R = 1 ,14473.54,2483.556,2495.34,2521.91
BEGIN DESCRIPTION:
POP_13 - Football Stadium - US
END DESCRIPTION:
XS GIS Cut Line= 4
  589764.6809449 4389300.9652392  589789.8513292 4389306.7076713
  589813.1807215 4389317.2750874  589841.9965138 4389324.7609755
#Sta/Elev= 30
-168.668 1087.99-144.948    1087-107.677 1084.89 -93.307  1083.6 -82.119    1082
 -76.837 1080.45 -69.849 1078.32  -64.14    1076 -63.189 1075.25 -51.148 1070.15
  -6.726 1066.14  -4.921 1065.06   -1.64  1063.1   -.591 1063.22       0 1063.05
    .558 1063.04    .919 1063.32   2.133 1063.29   4.528 1064.73   5.151 1064.79
  15.387 1065.74  18.635 1068.87   27.92    1074  33.825 1077.42  44.751    1084
    47.9    1086  75.492 1090.07  83.727 1091.49  88.353    1092  97.736    1094
#Mann= 5 ,-1 , 0
-168.668     .12       0-107.677     .12       0 -76.837     .12       0
  -4.921    .038       0   5.151     .12       0
#XS Ineff= 2 , 0
       0     -50    1098      50       0    1098
Permanent Ineff=
       F       F
Bank Sta=-4.921,5.151
XS Rating Curve= 0 ,0
Minor Loss Coefficient=0.5
Exp/Cntr=0.5,0.3

Type RM Length L Ch R = 2 ,14186.20,,,
BEGIN DESCRIPTION:
POP_13 - Football Stadium
END DESCRIPTION:
Bridge Culvert--1,0,-1,-1, 0
Deck Dist Width WeirC Skew NumUp NumDn MinLoCord MaxHiCord MaxSubmerge Is_Ogee
20,1760,2.6,0, 46, 46, , , , 0, 0,0,,
-327.067-326.575-326.115-325.525-325.066-324.541 -324.18-323.786-323.425-319.915
-317.159-260.499-229.626-174.705-143.274 -69.259  20.768  46.654  47.605  48.524
  49.114   49.77   65.19  65.486  65.781  67.126  71.522  76.575 102.592 107.907
 111.155 113.255 118.077 120.079 120.833 122.933 124.639 125.689 129.888 136.319
  138.55 145.997   147.9 149.869 151.575 161.844
    1090    1090    1090    1090    1090    1090    1090    1090    1090 1090.35
 1090.43    1092 1092.85 1094.42 1095.32 1097.47 1098.83 1099.04 1099.04 1099.05
 1099.05 1099.06 1099.77 1099.77 1099.77 1099.77  1099.8    1100    1102 1103.32
    1104    1104 1105.41 1105.83    1106 1106.44 1106.81 1107.03    1108  1109.5
    1110  1111.6    1112 1112.33 1112.61    1114
                                                                                
                                                                                
                                                                                
                                                                                
                                                
-327.067-326.575-326.115-325.525-325.066-324.541 -324.18-323.786-323.425-319.915
-317.159-260.499-229.626-174.705-143.274 -69.259  20.768  46.654  47.605  48.524
  49.114   49.77   65.19  65.486  65.781  67.126  71.522  76.575 102.592 107.907
 111.155 113.255 118.077 120.079 120.833 122.933 124.639 125.689 129.888 136.319
  138.55 145.997   147.9 149.869 151.575 161.844
    1090    1090    1090    1090    1090    1090    1090    1090    1090 1090.35
 1090.43    1092 1092.85 1094.42 1095.32 1097.47 1098.83 1099.04 1099.04 1099.05
 1099.05 1099.06 1099.77 1099.77 1099.77 1099.77  1099.8    1100    1102 1103.32
    1104    1104 1105.41 1105.83    1106 1106.44 1106.81 1107.03    1108  1109.5
    1110  1111.6    1112 1112.33 1112.61    1114
                                                                                
                                                                                
                                                                                
                                                                                
                                                
BR Coef=-1 , 0 , 0 ,, 0 ,,,0.8,-1,,0,
WSPro=,,,, 1 ,,,, 0 ,,,, 0 ,,,,-1 ,-1 ,-1 , 0 , 0 , 0 , 0 , 0
Culvert=4,8.4,7.7,1800,0.024,0.5,1,29,1,1062.51,0,1050.66,1,Culvert #1  , 1 ,57.448
Culvert Bottom n=0.024
BR U #Sta/Elev= 64
-168.668 1087.99-161.975 1087.75 -161.22 1087.71-152.067 1087.36-150.459 1087.26
-148.294 1087.14-144.948    1087-142.093 1086.84-139.698 1086.73-136.155 1086.53
-134.678 1086.46-130.479 1086.22-129.888 1086.19-129.429 1086.17-126.739    1086
-107.677 1084.89-106.266 1084.78-102.559  1084.5 -99.606 1084.23 -97.671 1084.06
 -97.605 1084.05 -97.047    1084 -95.899 1083.87 -94.488 1083.72 -93.307  1083.6
 -83.957 1082.25 -82.119    1082 -76.837 1080.45 -69.849 1078.32 -69.062    1078
 -66.667 1077.02  -64.14    1076 -63.189 1075.25 -51.148 1070.15 -37.467 1068.97
 -22.047 1067.58  -6.726 1066.14  -4.921 1065.06   -1.64 1062.78       0  1062.5
   2.133 1062.78   4.528 1064.73   5.151 1064.79  15.387 1065.74  18.635 1068.87
  19.554 1069.37  20.735    1070  22.047 1070.74  24.344    1072  27.592 1073.82
   27.92    1074  30.741 1075.62  33.825 1077.42  43.209 1083.07  44.685 1083.97
  44.751    1084   44.98 1084.15    47.9    1086  75.492 1090.07  83.727 1091.49
  88.353    1092  89.928 1092.32   91.01 1092.55  97.736    1094
BR U #Mann= 6
-168.668     .12-107.677     .12 -83.957     .12 -76.837     .12  -4.921    .035
   5.151     .12
BR D #Sta/Elev= 139
-169.357    1070-169.259    1070-166.535 1069.63-166.306  1069.6 -166.01 1069.57
-165.322 1069.48-164.436 1069.38-163.747 1069.29-163.156 1069.22-162.598 1069.15
 -152.92 1068.04-152.526    1068-151.673 1067.97-150.755 1067.94-149.902 1067.91
-142.487  1067.7 -142.29  1067.7-142.192 1067.69 -142.06 1067.69-141.109 1067.66
-138.944 1067.61-138.386 1067.59-137.106 1067.56-136.778 1067.55-136.549 1067.55
-107.612 1066.14 -98.753 1066.02 -96.949    1066  -96.26 1065.88 -96.063 1065.85
 -92.913 1065.31 -92.454 1065.23 -91.962 1065.14  -89.37  1064.7 -88.812 1064.61
 -88.189  1064.5 -87.434 1064.37 -86.352 1064.19 -85.958 1064.12 -85.531 1064.06
 -85.203    1064 -85.105 1063.99  -84.81  1063.9 -84.416 1063.81 -84.154 1063.74
 -83.924 1063.67 -83.727 1063.62 -83.465 1063.55 -83.136 1063.47 -82.874 1063.39
 -82.382 1063.26 -82.119 1063.18 -81.266 1062.96  -81.07 1062.89  -79.56 1062.47
 -79.396 1062.42 -77.887    1062 -77.526 1061.89 -76.936 1061.77 -75.328 1061.35
 -74.344 1061.08 -73.524 1060.92 -72.277 1060.68 -71.424 1060.47 -69.849 1060.18
  -68.93    1060 -67.749 1059.91 -61.778 1059.36 -56.824 1058.92 -54.724 1058.73
 -54.134 1058.68 -52.592 1058.53  -51.87 1058.47 -50.131 1058.31 -48.294 1058.13
 -46.883    1058 -39.731    1058 -21.982 1056.03 -21.686    1056 -20.866    1056
  -4.954 1054.42  -3.576 1054.28  -3.215 1054.27  -2.997 1054.11    -1.7 1051.17
       1  1050.6     2.7 1050.98   3.971    1052   4.954 1052.38   5.052 1052.42
   5.676 1052.62  10.039    1054  11.024 1054.63  11.286  1054.8  11.745 1055.11
  12.762 1055.79  12.927 1055.92  13.058    1056  13.189 1056.11  13.681  1056.5
  15.551    1058  15.978 1058.32  17.881 1059.79   18.11 1059.96   19.98 1061.41
  20.735    1062  21.424 1062.51   21.85 1062.84  22.605 1063.42  22.835 1063.61
  23.261 1063.95  28.445 1067.38  29.462    1068  31.004 1068.57  31.529 1068.78
  32.612 1069.21   34.58    1070  35.761 1070.09  37.336 1070.22  37.434 1070.22
  38.845 1070.33  38.976 1070.33  40.256 1070.43   40.42 1070.43  41.437  1070.5
  42.028 1070.55  42.487 1070.55  43.077  1070.6  43.635 1070.64   44.16 1070.68
  44.652 1070.72  49.869 1070.82  64.206 1071.74  64.469 1071.75  64.928 1071.77
  65.125 1071.78   68.11    1072  82.448    1072  92.848 1072.32
BR D #Mann= 5
-169.357     .06  -4.954     .12  -3.576    .035   4.954     .12  38.845     .06
BR D Banks=,5.676
BC Design=,, 0 ,, 0 ,,,,,,
BC Use User HTab Curves=0
BC User HTab FreeFlow(D)= 0

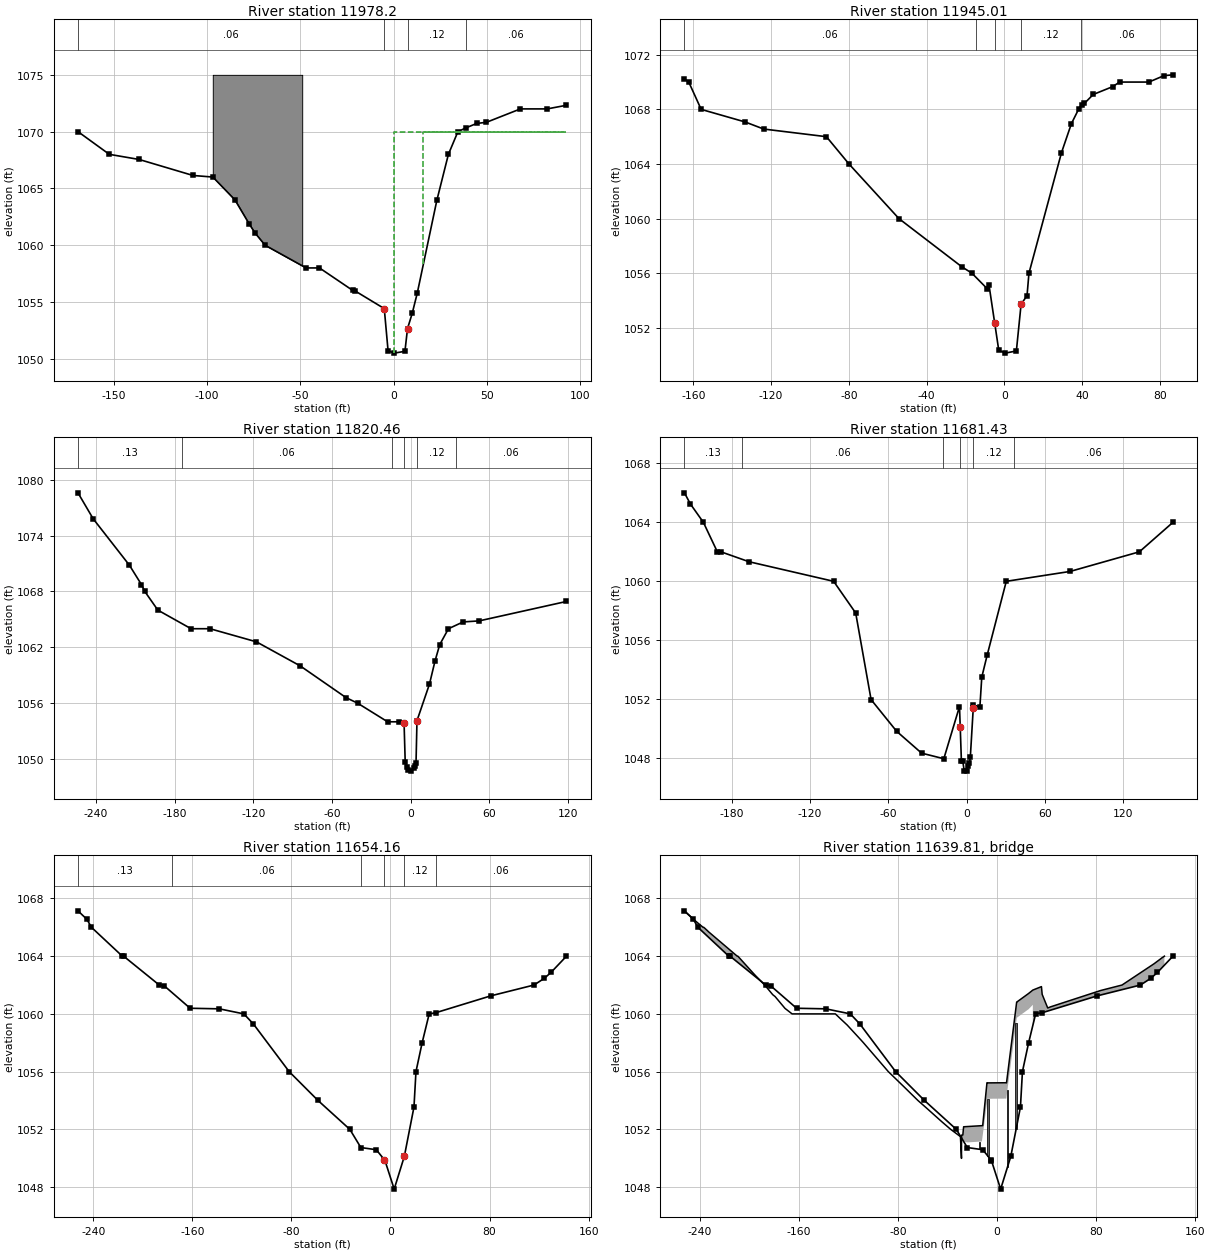
Type RM Length L Ch R = 1 ,11978.2 ,33.222,33.245,33.087
BEGIN DESCRIPTION:
POP_13 - Football Stadium - DS
END DESCRIPTION:
XS GIS Cut Line= 4
589355.468651825 4389500.4690337 589364.762003944389551.59009033
589366.4688839614389566.35155451589379.1394201184389569.71654655
#Sta/Elev= 29
-169.357    1070-152.526    1068-136.549 1067.55-107.612 1066.14 -96.949    1066
 -85.105 1063.99 -77.526 1061.89 -74.344 1061.08  -68.93    1060 -46.883    1058
 -39.731    1058 -21.982 1056.03 -20.866    1056  -4.954 1054.42   -2.92 1050.71
    .394  1050.5   6.135 1050.66    7.52 1052.66  10.039    1054  12.762 1055.79
  23.261 1063.95  29.462    1068   34.58    1070  38.845 1070.33  44.652 1070.72
  49.869 1070.82   68.11    1072  82.448    1072  92.848 1072.32
#Mann= 4 ,-1 , 0
-169.357     .06       0  -4.954    .038       0    7.52     .12       0
  38.845     .06       0
#XS Ineff= 2 , 0
       0     -16    1070      16       0    1070
Permanent Ineff=
       F       F
#Block Obstruct= 1 ,-1
     -97     -49    1075
Bank Sta=-4.954,7.52
XS Rating Curve= 0 ,0
Minor Loss Coefficient=0.5
Exp/Cntr=0.5,0.3

Type RM Length L Ch R = 1 ,11945.01,124.953,124.761,123.752
Node Name=AL
XS GIS Cut Line= 4
589345.6297077044389502.25820972589354.8651478184389553.06227435
 589356.642131844389568.40590654 589364.74676394 4389573.3162346
#Sta/Elev= 30
-164.534 1070.23-162.303    1070-155.938    1068-133.366 1067.08-123.786 1066.56
 -91.535    1066 -79.921    1064 -54.232    1060 -21.982 1056.48 -16.699    1056
  -8.957 1054.88   -7.94 1055.14  -5.052 1052.39   -2.92 1050.36    .394 1050.15
   6.135 1050.31   8.563 1053.73  11.614 1054.36  12.598    1056  29.331 1064.83
  34.416 1066.95  38.091    1068  39.797 1068.35  41.142 1068.44  45.636 1069.09
  55.577 1069.66  59.219    1070  74.278    1070  82.021 1070.47  86.647 1070.53
#Mann= 5 ,-1 , 0
-164.534     .06       0 -14.665     .12       0  -5.052    .038       0
   8.563     .12       0  39.304     .06       0
Bank Sta=-5.052,8.563
XS Rating Curve= 0 ,0
Exp/Cntr=0.3,0.1

Type RM Length L Ch R = 1 ,11820.46,138.556,139.264,140.086
Node Name=AK
XS GIS Cut Line= 4
 589302.460883174389483.28745748589304.1403311914389491.67250559
589320.8067953974389574.77927462589339.5580916294389582.62787471
#Sta/Elev= 30
-253.806  1078.6-242.192 1075.81-214.534 1070.82-205.381 1068.75-202.789    1068
-192.848    1066-167.487    1064-153.051    1064-117.585 1062.59 -84.121    1060
 -49.147 1056.59 -40.354    1056 -17.487    1054  -8.497    1054  -4.921 1053.82
   -4.07 1049.72   -2.97 1049.14   -1.79 1048.77     .19  1048.7    2.74 1049.01
    3.61 1049.22    4.19 1049.57   4.921 1054.12  14.469 1058.06  18.668 1060.52
  22.277 1062.29  28.937    1064  40.157 1064.73  52.329 1064.84 119.029 1066.93
#Mann= 6 ,-1 , 0
-253.806     .13       0-174.672     .06       0 -14.436     .12       0
  -4.921    .038       0   4.921     .12       0  34.613     .06       0
Bank Sta=-4.921,4.921
XS Rating Curve= 0 ,0
Exp/Cntr=0.3,0.1

Type RM Length L Ch R = 1 ,11681.43,27.236,27.313,27.373
Node Name=AJ
XS GIS Cut Line= 6
 589266.055570724389501.16092971589268.3019467484389514.67271387
 589274.111434824389554.20527436589276.2541788464389567.84812253
589278.0037308684389579.53415467589283.182282932 4389613.9003551
#Sta/Elev= 30
-216.175    1066-211.581 1065.24-201.673    1064-190.978    1062-188.189    1062
-166.798 1061.33-101.903    1060 -85.007 1057.85 -73.228 1051.98 -53.642 1049.83
 -34.547 1048.35  -17.52 1047.97  -5.512 1051.51  -4.954 1050.12  -4.068 1047.85
  -3.084 1047.85  -1.903 1047.15   -.033 1047.13    .951 1047.47   2.067 1047.68
   2.789 1048.09    5.02  1051.4   5.151 1051.61  10.105 1051.49  11.549  1053.5
  15.748 1055.02  30.315    1060  79.199 1060.67 132.251    1062 157.972    1064
#Mann= 6 ,-1 , 0
-216.175     .13       0-172.113     .06       0 -17.979     .12       0
  -4.954    .038       0    5.02     .12       0  36.089     .06       0
Bank Sta=-4.954,5.02
XS Rating Curve= 0 ,0
Exp/Cntr=0.3,0.1

Type RM Length L Ch R = 1 ,11654.16,23.492,23.324,24.39
XS GIS Cut Line= 6
589250.4741945284389495.10760163589260.3131386494389516.34301789
589265.9184107194389554.48873836589268.0611547454389568.14682653
589269.7741307664389579.58597067 589274.126674824389612.15994708
#Sta/Elev= 30
-252.264 1067.14-245.046 1066.55-241.404    1066 -216.47    1064 -215.42    1064
-186.647    1062-182.415 1061.93-161.713 1060.39-138.123 1060.35 -118.34    1060
 -110.63  1059.3 -81.759    1056 -58.465    1054 -32.776    1052 -23.885 1050.74
 -11.417 1050.59  -5.052 1049.91  -4.429 1049.84   3.018 1047.86   11.22 1050.13
  18.996 1053.55  20.604    1056  25.591    1058  31.266    1060  36.549 1060.08
  81.037 1061.25 115.912    1062 124.311 1062.47 129.593 1062.87 142.126    1064
#Mann= 6 ,-1 , 0
-252.264     .13       0-176.476     .06       0 -23.556     .12       0
  -5.052    .038       0   11.22     .12       0  36.549     .06       0
Bank Sta=-5.052,11.22
XS Rating Curve= 0 ,0
Exp/Cntr=0.5,0.3

Type RM Length L Ch R = 3 ,11639.81,,,
BEGIN DESCRIPTION:
POP_12 - WVU Foot Bridge
END DESCRIPTION:
Bridge Culvert--1,0,-1,-1, 0
Deck Dist Width WeirC Skew NumUp NumDn MinLoCord MaxHiCord MaxSubmerge Is_Ogee
11.4,6,2.6,0, 155, 155, , , , 0, 0,0,,
 -250.82-249.869-248.524-245.768-245.407-243.504-242.356 -242.06-241.339-237.369
-237.336-237.303 -237.27-237.238-237.205-237.172-237.106-237.041-237.008-236.909
-236.877-236.844-236.713-236.483-236.056 -235.86-235.827 -235.63  -235.4-235.335
-235.171-234.777-234.711-234.154-234.055-233.957-233.629-233.104 -232.94-232.808
 -209.81-209.678-209.514-209.482 -209.35-209.318-209.285-209.186-209.154-205.282
-202.461-200.459-198.885-196.391-195.308-191.699-191.142  -187.5-187.172-185.794
-183.399-183.268-183.104-182.841-182.677-182.513-182.349-182.152-181.988-181.824
-181.759-181.463-180.971-179.068-178.773-171.063-168.668-165.814-165.354-163.386
-161.614-159.186 -148.72-145.833-141.437-133.858-130.413-127.887-127.001-123.917
-123.458-122.867-120.899-117.323-116.634-114.698-110.827-109.416-107.743 -98.031
 -91.765 -90.256 -87.664  -86.22 -85.761 -84.843 -82.054 -75.394 -63.747 -56.857
 -52.231 -46.719 -44.226 -37.303 -32.152  -31.66  -31.07 -30.348 -29.462 -28.609
 -28.543 -27.526 -26.936 -26.903  -26.87 -12.106 -11.975 -11.483  -8.038  -7.579
  -7.513   7.579   7.612   7.743  15.945  16.043  25.656      29  35.958  36.549
   41.01  43.373  83.727  86.942   90.65   94.98 100.098 101.017 126.411 126.608
 126.804 130.151  131.66 133.333 135.236
 1067.01 1066.94 1066.84 1066.63  1066.6 1066.45 1066.37 1066.35 1066.29    1066
    1066    1066    1066    1066    1066    1066    1066    1066    1066    1066
    1066    1066    1066 1065.98 1065.95 1065.94 1065.94 1065.92  1065.9  1065.9
 1065.88 1065.85 1065.85  1065.8 1065.79 1065.79 1065.76 1065.71  1065.7 1065.69
    1064    1064    1064    1064    1064    1064    1064    1064    1064 1063.63
 1063.36 1063.17 1063.02 1062.79 1062.69 1062.37 1062.32    1062 1061.97 1061.83
 1061.59 1061.57 1061.56 1061.53 1061.51  1061.5 1061.48 1061.46 1061.44 1061.42
 1061.41 1061.38 1061.33  1061.2 1061.17 1060.38 1060.22 1060.03    1060    1060
    1060    1060    1060    1060    1060    1060    1060  1059.8 1059.72 1059.47
 1059.44 1059.39 1059.23  1058.9 1058.84 1058.66 1058.29 1058.16    1058 1057.03
  1056.4 1056.25    1056 1055.88 1055.85 1055.77 1055.53 1054.98    1054 1053.48
 1053.12  1052.7 1052.51    1052 1051.67 1051.64  1051.6 1051.56  1051.5 1049.99
  1051.6 1051.61 1052.17 1052.13 1052.18 1052.25 1052.25 1052.26 1055.23 1055.22
 1055.22 1055.23 1055.23 1055.22 1060.82 1060.82 1061.42 1061.65 1061.89 1061.35
 1060.41 1060.49 1061.62 1061.69 1061.77 1061.87 1061.98    1062 1063.45 1063.46
 1063.47 1063.68 1063.78 1063.89    1064
                                                                                
                                                                                
                                                                                
                                                                                
                                                                                
                                                                                
                                                                                
                                                                                
                                                                                
                                                                                
                                                                                
                                                                                
                         1051.08 1051.08 1051.16 1051.25 1051.57 1053.82 1054.12
 1054.12 1054.13 1054.15 1054.24 1059.66 1059.73 1060.33 1060.63
                                                                                
                                        
 -250.82-249.869-248.524-245.768-245.407-243.504-242.356 -242.06-241.339-237.369
-237.336-237.303 -237.27-237.238-237.205-237.172-237.106-237.041-237.008-236.909
-236.877-236.844-236.713-236.483-236.056 -235.86-235.827 -235.63  -235.4-235.335
-235.171-234.777-234.711-234.154-234.055-233.957-233.629-233.104 -232.94-232.808
 -209.81-209.678-209.514-209.482 -209.35-209.318-209.285-209.186-209.154-205.282
-202.461-200.459-198.885-196.391-195.308-191.699-191.142  -187.5-187.172-185.794
-183.399-183.268-183.104-182.841-182.677-182.513-182.349-182.152-181.988-181.824
-181.759-181.463-180.971-179.068-178.773-171.063-168.668-165.814-165.354-163.386
-161.614-159.186 -148.72-145.833-141.437-133.858-130.413-127.887-127.001-123.917
-123.458-122.867-120.899-117.323-116.634-114.698-110.827-109.416-107.743 -98.031
 -91.765 -90.256 -87.664  -86.22 -85.761 -84.843 -82.054 -75.394 -63.747 -56.857
 -52.231 -46.719 -44.226 -37.303 -32.152  -31.66  -31.07 -30.348 -29.462 -28.609
 -28.543 -27.526 -26.936 -26.903  -26.87 -12.106 -11.975 -11.483  -8.038  -7.579
  -7.513   7.579   7.612   7.743  15.945  16.043  25.656      29  35.958  36.549
   41.01  43.373  83.727  86.942   90.65   94.98 100.098 101.017 126.411 126.608
 126.804 130.151  131.66 133.333 135.236
 1067.01 1066.94 1066.84 1066.63  1066.6 1066.45 1066.37 1066.35 1066.29    1066
    1066    1066    1066    1066    1066    1066    1066    1066    1066    1066
    1066    1066    1066 1065.98 1065.95 1065.94 1065.94 1065.92  1065.9  1065.9
 1065.88 1065.85 1065.85  1065.8 1065.79 1065.79 1065.76 1065.71  1065.7 1065.69
    1064    1064    1064    1064    1064    1064    1064    1064    1064 1063.63
 1063.36 1063.17 1063.02 1062.79 1062.69 1062.37 1062.32    1062 1061.97 1061.83
 1061.59 1061.57 1061.56 1061.53 1061.51  1061.5 1061.48 1061.46 1061.44 1061.42
 1061.41 1061.38 1061.33  1061.2 1061.17 1060.38 1060.22 1060.03    1060    1060
    1060    1060    1060    1060    1060    1060    1060  1059.8 1059.72 1059.47
 1059.44 1059.39 1059.23  1058.9 1058.84 1058.66 1058.29 1058.16    1058 1057.03
  1056.4 1056.25    1056 1055.88 1055.85 1055.77 1055.53 1054.98    1054 1053.48
 1053.12  1052.7 1052.51    1052 1051.67 1051.64  1051.6 1051.56  1051.5 1049.99
  1051.6 1051.61 1052.17 1052.13 1052.18 1052.25 1052.25 1052.26 1055.23 1055.22
 1055.22 1055.23 1055.23 1055.22 1060.82 1060.82 1061.42 1061.65 1061.89 1061.35
 1060.41 1060.49 1061.62 1061.69 1061.77 1061.87 1061.98    1062 1063.45 1063.46
 1063.47 1063.68 1063.78 1063.89    1064
                                                                                
                                                                                
                                                                                
                                                                                
                                                                                
                                                                                
                                                                                
                                                                                
                                                                                
                                                                                
                                                                                
                                                                                
                         1051.08 1051.08 1051.16 1051.25 1051.57 1053.82 1054.12
 1054.12 1054.13 1054.15 1054.24 1059.66 1059.73 1060.33 1060.63
                                                                                
                                        
Pier Skew, UpSta & Num, DnSta & Num=  ,-14.1, 2 ,-14.1, 2 , 0 , 0 , 0 ,,
       1       1
    1045    1060
       1       1
    1045    1060
Pier Skew, UpSta & Num, DnSta & Num=  ,-7.1, 2 ,-7.1, 2 , 0 , 0 , 0 ,,
       1       1
    1045    1060
       1       1
    1045    1060
Pier Skew, UpSta & Num, DnSta & Num=  ,8.5, 2 ,8.5, 2 , 0 , 0 , 0 ,,
       1       1
    1045    1060
       1       1
    1045    1060
Pier Skew, UpSta & Num, DnSta & Num=  ,15.5, 2 ,15.5, 2 , 0 , 0 , 0 ,,
       1       1
    1045    1060
       1       1
    1045    1060
BR Coef= 1 , 1 , 0 ,, 0 ,,,0.8,-1,0.3,6,
WSPro=,,,, 1 ,,,, 0 ,,,, 0 ,,,,-1 ,-1 ,-1 , 0 , 0 , 0 , 0 , 0
BC Design=,, 0 ,, 0 ,,,,,,
BC Use User HTab Curves=0
BC User HTab FreeFlow(D)= 0

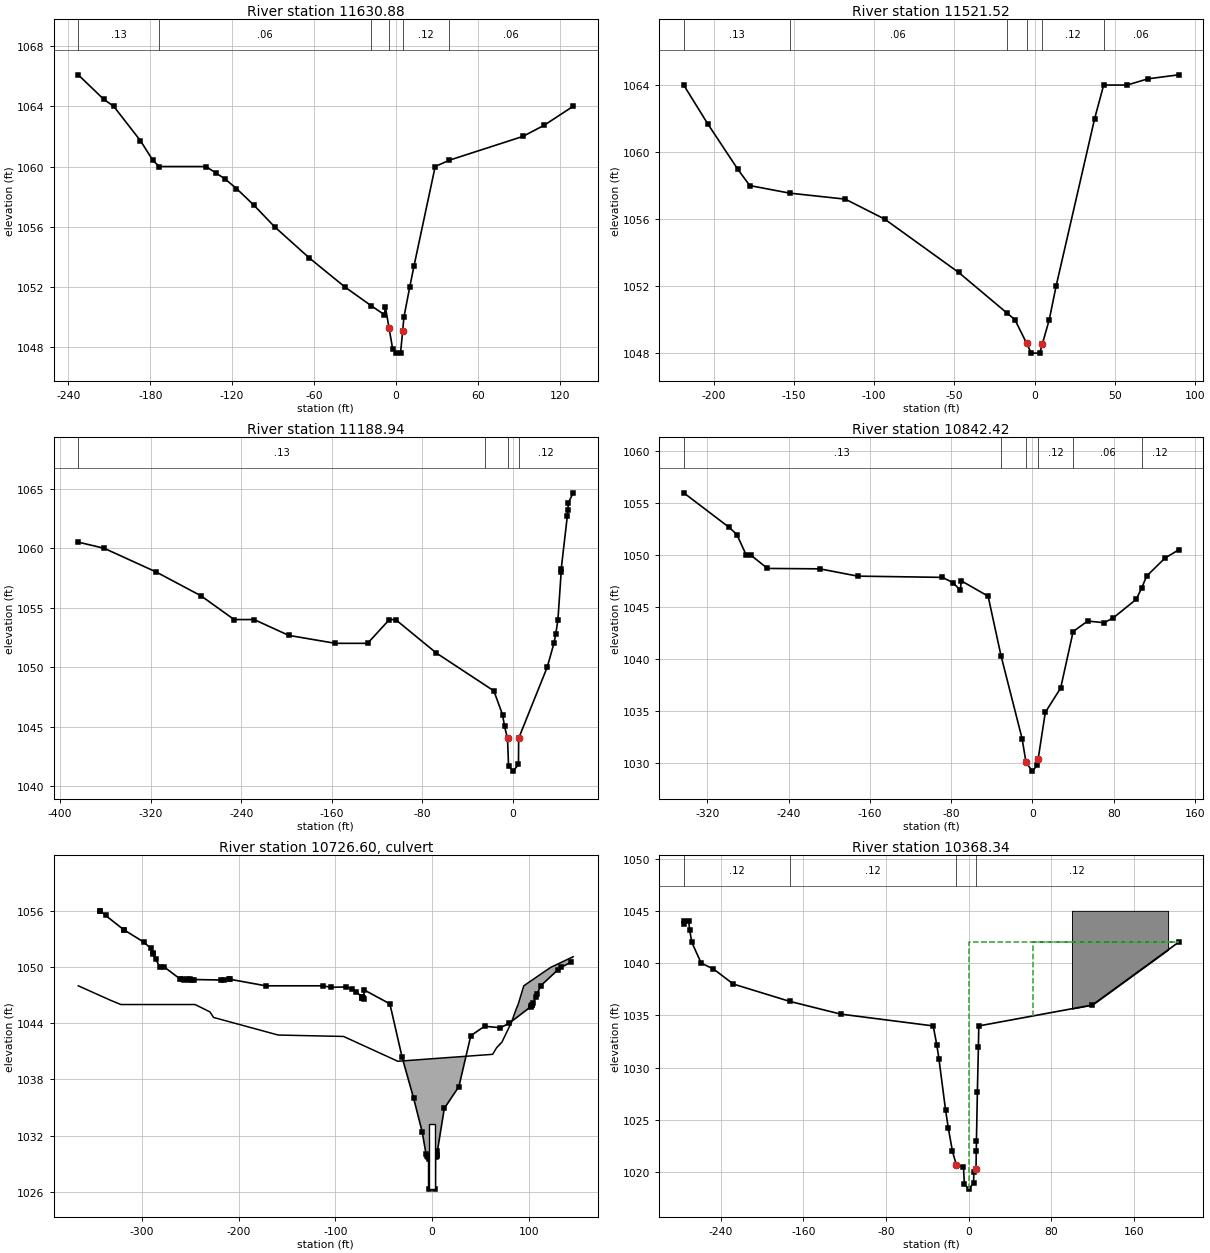
Type RM Length L Ch R = 1 ,11630.88,108.691,109.545,109.069
BEGIN DESCRIPTION:
POP_12 - WVU Foot Bridge  - US
END DESCRIPTION:
XS GIS Cut Line= 6
589244.6860424564389502.67273772589253.3057865634389521.28077795
589259.0146906334389555.94263438589261.4469946634389571.03937857
589262.291290674 4389581.2776107 589265.241754714389610.42868306
#Sta/Elev= 30
 -232.71 1066.09 -214.14 1064.47-206.759    1064-187.139 1061.71-178.182 1060.43
-173.524    1060-139.239    1060-131.463 1059.55-125.427 1059.19-116.831 1058.54
-103.904 1057.42 -88.911    1056 -63.484 1053.93 -37.369    1052  -18.34 1050.77
  -8.432 1050.16  -7.743 1050.69  -5.052 1049.27  -2.428  1047.9       0 1047.61
   3.379 1047.63   4.921 1049.08    5.84    1050  10.105    1052  13.222  1053.4
   28.74    1060  39.075 1060.42  92.979    1062 108.366 1062.73 129.823    1064
#Mann= 6 ,-1 , 0
 -232.71     .13       0-173.524     .06       0  -18.34     .12       0
  -5.052    .038       0   4.921     .12       0  39.075     .06       0
Bank Sta=-5.052,4.921
XS Rating Curve= 0 ,0
Exp/Cntr=0.5,0.3

Type RM Length L Ch R = 1 ,11521.52,335.736,332.58,329.424
BEGIN DESCRIPTION:
POP_12 - WVU Foot Bridge  - DS
END DESCRIPTION:
Node Name=AI
XS GIS Cut Line= 2
 589220.716570164389504.79109775589231.143778289 4389598.1818189
#Sta/Elev= 21
 -218.57    1064-203.576 1061.68-184.777 1058.96-177.428    1058-152.657 1057.55
-117.913 1057.19 -93.406    1056 -47.343 1052.82 -17.159 1050.39  -12.27    1050
  -4.921 1048.58  -2.067    1048   3.248    1048   4.921 1048.57   9.154    1050
  13.419    1052  37.434    1062  43.045    1064  57.644    1064  70.571 1064.37
  89.731 1064.61
#Mann= 6 ,-1 , 0
 -218.57     .13       0-152.657     .06       0 -17.159     .12       0
  -4.921    .038       0   4.921     .12       0  43.045     .06       0
Bank Sta=-4.921,4.921
XS Rating Curve= 0 ,0
Exp/Cntr=0.5,0.3

Type RM Length L Ch R = 1 ,11188.94,347.354,346.52,353.637
Node Name=AH
XS GIS Cut Line= 3
589121.836400938 4389468.6357213589116.7736728754389546.31400226
 589133.312121084389599.10536292
#Sta/Elev= 30
-383.858 1060.51-361.155    1060-315.289 1058.01-275.591    1056 -246.26    1054
-228.642    1054-198.097 1052.67 -156.89    1052-128.445    1052-109.219    1054
-103.773    1054 -67.684 1051.18 -16.962    1048  -9.318    1046  -7.513 1045.01
  -4.921    1044  -4.003  1041.7       0 1041.25   4.757 1041.81   4.921 1044.01
  30.151    1050  36.056    1052  37.664 1052.77    39.6    1054  42.454    1058
  42.487 1058.25  47.867 1062.69  48.458 1063.22   48.72  1063.8  53.051 1064.66
#Mann= 4 ,-1 , 0
-383.858     .13       0 -24.869     .12       0  -4.921    .038       0
   4.921     .12       0
Bank Sta=-4.921,4.921
XS Rating Curve= 0 ,0
Exp/Cntr=0.5,0.3

Type RM Length L Ch R = 1 ,10842.42,483.434,474.086,468.286
BEGIN DESCRIPTION:
POP_11 - WVU Alumni Building Crossing - US
END DESCRIPTION:
XS GIS Cut Line= 4
    589048.54724 4389468.7454493  589029.6100158 4389549.7704343
  589027.9915278 4389571.0820506  589026.4126638 4389614.9397231
#Sta/Elev= 30
-343.176 1056.01 -298.36 1052.68-290.879    1052-281.529    1050-276.903    1050
-260.728 1048.74-209.186  1048.7-171.949    1048 -88.484 1047.88 -78.314 1047.38
 -70.768 1046.63 -70.177 1047.56  -43.57 1046.07 -30.906 1040.36 -10.105 1032.37
  -6.266 1030.08       0 1029.25   4.757 1029.81    5.64 1030.39   12.73  1034.9
  27.822 1037.24  40.125 1042.67  54.364 1043.68  70.702 1043.52  79.823    1044
 102.198 1045.77  107.48 1046.83 112.434    1048 130.577 1049.74  143.93 1050.52
#Mann= 6 ,-1 , 0
-343.176     .13       0 -30.906     .12       0  -6.266     .05       0
    5.64     .12       0  40.125     .06       0  107.48     .12       0
Bank Sta=-6.266,5.64
XS Rating Curve= 0 ,0
Minor Loss Coefficient=0.5
Exp/Cntr=0.5,0.3

Type RM Length L Ch R = 2 ,10726.60,,,
BEGIN DESCRIPTION:
POP_11 - WVU Alumni Building Crossing
Alumni Bldg. Tram underpass
Entrance loss coeff. of 0.7 used as one wall is parallel.
END DESCRIPTION:
Bridge Culvert--1,0,-1,-1, 0
Deck Dist Width WeirC Skew NumUp NumDn MinLoCord MaxHiCord MaxSubmerge Is_Ogee
50,418,2.6,0, 58, 59, , , 0.98, 0, 0,0,,
-365.912-332.448-321.883 -321.03-317.126 -316.47-314.961 -305.84-302.034 -296.03
-292.192-284.547-284.383-283.858-263.451-256.627-253.412-251.444-250.558-249.606
-248.589-247.507-246.325-245.276-245.112-244.849-244.718-238.615-233.202-229.724
-225.984-159.121 -91.503   -35.4       0   62.73  66.831   68.34  68.373  68.438
  70.308  70.341  70.341  70.374  72.474  72.999  74.114  81.791  86.713  87.861
  89.075  92.028  94.915 101.706 111.975 123.163 123.425  146.03
    1048 1046.45    1046    1046    1046    1046    1046    1046    1046    1046
    1046    1046    1046    1046    1046    1046    1046    1046    1046    1046
    1046    1046    1046    1046    1046 1045.99 1045.98 1045.67 1045.39 1045.21
 1044.62 1042.74 1042.59 1039.94 1040.21 1040.68 1041.39 1041.55 1041.56 1041.56
 1041.76 1041.76 1041.77 1041.77    1042 1042.12 1042.37    1044 1045.41 1045.71
    1046 1047.01    1048 1048.48 1049.21    1050    1050 1051.11
                                                                                
                                                                                
                                                                                
                                                                                
                                                                                
                                                                
-365.912-332.448-321.883 -321.03-317.126 -316.47-314.961 -305.84-302.034 -296.03
-292.192-284.547-284.383-283.858-263.451-256.627-253.412-251.444-250.558-249.606
-248.589-247.507-246.325-245.276-245.112-244.849-244.718-238.615-233.202-229.724
-225.984-159.121 -91.503   -35.4       0   62.73  66.831   68.34  68.373  68.438
  70.308  70.341  70.341  70.374  72.474  72.999  74.114  81.791  86.713  87.861
  89.075  92.028  94.915 101.706 111.975 123.163 123.425  146.03     250
    1048 1046.45    1046    1046    1046    1046    1046    1046    1046    1046
    1046    1046    1046    1046    1046    1046    1046    1046    1046    1046
    1046    1046    1046    1046    1046 1045.99 1045.98 1045.67 1045.39 1045.21
 1044.62 1042.74 1042.59 1039.94 1040.21 1040.68 1041.39 1041.55 1041.56 1041.56
 1041.76 1041.76 1041.77 1041.77    1042 1042.12 1042.37    1044 1045.41 1045.71
    1046 1047.01    1048 1048.48 1049.21    1050    1050 1051.11 1051.11
                                                                                
                                                                                
                                                                                
                                                                                
                                                                                
                                                                        
BR Coef=-1 , 0 , 0 ,, 0 ,,,0.8,-1,,0,
WSPro=,,,, 1 ,,,, 0 ,,,, 0 ,,,,-1 ,-1 ,-1 , 0 , 0 , 0 , 0 , 0
Culvert=2,7,7,418,0.013,0.7,1,8,1,1026.28,0,1018.4,0,Culvert #1  , 0 ,50
Culvert Bottom n=0.013
BR U #Sta/Elev= 69
-343.176 1056.01-343.077    1056-337.697 1055.52-318.996    1054 -318.93    1054
 -298.36 1052.68-290.879    1052-288.812 1051.47 -288.55 1051.41 -285.86 1050.85
-281.529    1050-276.903    1050-260.728 1048.74-258.661 1048.69 -256.89 1048.64
-253.379  1048.7-251.608 1048.66-249.836 1048.68-248.163 1048.64-246.391 1048.67
-218.471 1048.62 -215.65 1048.64-209.777  1048.7-209.186  1048.7-171.949    1048
-112.992    1048-104.429 1047.84 -88.484 1047.88 -83.104 1047.65 -78.314 1047.38
 -72.507 1046.79 -72.343 1046.77 -72.146 1046.75 -71.916 1046.73 -71.719 1046.71
  -71.03 1046.65 -70.768 1046.63 -70.177 1047.56  -43.57 1046.07 -30.906 1040.36
 -18.963 1035.97 -10.105 1032.37  -6.266 1030.08  -4.987 1029.86  -4.003  1029.7
   -3.52 1029.48    -3.5 1026.28     3.5 1026.28    3.62 1029.72   4.757 1029.81
   4.921 1029.92    5.64 1030.39   12.73  1034.9  27.822 1037.24  40.125 1042.67
  54.364 1043.68  70.702 1043.52  79.823    1044 102.198 1045.77  102.92 1045.87
 103.773 1045.98 103.937    1046 104.724 1046.19  107.48 1046.83  108.76 1047.13
 112.434    1048 130.577 1049.74 133.858    1050  143.93 1050.52
BR U #Mann= 6
-343.176     .13 -30.906     .12  -4.987     .05    5.64     .12  40.125     .06
  107.48     .12
BR D #Sta/Elev= 160
-275.623 1043.71-275.328    1044-272.736    1044-272.539    1044-272.343    1044
-272.047    1044-271.654    1044-271.391    1044-271.227    1044 -271.03    1044
-270.932    1044-270.801    1044-270.505 1043.71-270.243 1043.45-270.013 1043.33
-269.783 1043.12-269.324 1042.87-268.963  1042.6-268.209  1042.2 -268.11 1042.15
-267.848    1042-267.356 1041.91-267.192 1041.88-267.093 1041.86 -267.06 1041.85
-266.109 1041.67-265.912 1041.63-265.781  1041.6 -265.65 1041.57-264.731 1041.37
-264.501 1041.32-264.272 1041.26-263.517  1041.1-263.058 1040.99-262.697 1040.91
-262.238  1040.8-261.745 1040.69-261.253 1040.57-260.761 1040.46-260.236 1040.34
-259.646 1040.21-258.957 1040.05-258.924 1040.04-258.727    1040-258.169 1039.97
-255.446 1039.82-252.034 1039.65-248.031 1039.49-247.703 1039.48-247.408 1039.46
-247.113 1039.45-246.818 1039.44-227.657    1038-178.215 1036.51-174.114 1036.38
-172.867 1036.34-172.507 1036.33 -161.68    1036-160.564 1035.97-159.843 1035.94
-123.852 1035.13-122.605 1035.13-108.891 1035.09 -94.882  1034.9 -93.766 1034.88
 -92.618 1034.87 -66.175 1034.41 -51.312 1034.24 -49.738 1034.21 -34.285    1034
 -30.741 1032.18 -30.479    1032 -28.707 1030.85 -28.215 1030.47 -26.903 1029.59
 -25.558 1028.58 -24.869    1028 -22.507 1026.14 -22.343    1026 -20.308 1024.69
 -19.619 1024.23 -19.226    1024 -19.062 1023.91 -18.996 1023.88 -18.898 1023.81
 -18.471 1023.58 -17.257 1022.93 -16.306 1022.47 -16.175 1022.42 -16.076 1022.39
 -15.978 1022.36 -15.584    1022 -14.895 1021.69 -12.238 1020.75 -12.008 1020.75
 -11.877 1020.73 -10.827    1020  -9.646 1020.55   -9.35 1021.11  -8.333 1021.81
  -7.874 1022.76  -4.987 1021.11  -4.003 1018.85  -3.506  1018.4   -.066  1018.4
       0  1018.4   1.509  1018.4    3.92  1018.4   4.757 1018.96   5.052 1020.24
   5.151    1020   5.315    1020   7.152 1020.36   7.448    1022   7.579 1022.97
   7.776    1024    7.94 1024.88   8.169    1026   8.301 1026.66   8.497  1027.7
   8.563    1028    8.99 1029.89   9.022    1030   9.416 1031.72   9.482    1032
   9.678 1032.96   9.875    1034  10.925 1034.03  11.581 1034.05  12.172 1034.07
  12.631 1034.09  12.828  1034.1   14.37 1034.16  55.348 1034.87  72.441 1035.21
   95.21 1035.69   96.03  1035.7  96.883 1035.72  97.867 1035.73  99.016 1035.74
 100.295 1035.76 104.921 1035.82 110.335 1035.88 118.077 1035.98 119.718    1036
 120.604 1036.08 121.161 1036.12 127.133 1036.61 132.349 1036.96 136.352 1037.26
 138.878 1037.45 146.949    1038 148.852 1038.13 152.526  1038.4  164.37 1039.28
 167.421 1039.51 168.602  1039.6 173.655    1040 178.576  1040.4 203.182    1042
BR D #Mann= 4
-275.623     .12-172.867     .12  -4.987     .05   5.052     .12
BC Design=,, 0 ,, 0 ,,,,,,
BC Use User HTab Curves=0
BC User HTab FreeFlow(D)= 0

Type RM Length L Ch R = 1 ,10368.34,88.503,85.619,81.891
BEGIN DESCRIPTION:
POP_11 - WVU Alumni Building Crossing - DS
END DESCRIPTION:
XS GIS Cut Line= 6
     588885.9849     4389505.194     588880.7205    4389536.0688
     588877.7572    4389568.4538     588886.6672    4389586.6927
      588892.834    4389602.2544     588904.4467    4389645.7885
#Sta/Elev= 30
-275.623 1043.71-275.328    1044-270.801    1044-269.783 1043.12-267.848    1042
-258.727    1040-246.818 1039.44-227.657    1038-172.867 1036.34-123.852 1035.13
 -34.285    1034 -30.741 1032.18 -28.707 1030.85 -22.343    1026 -19.619 1024.23
 -15.584    1022 -11.877 1020.73  -4.987 1020.51  -4.003 1018.85       0  1018.4
   4.757 1018.96   5.151    1020   7.152 1020.36   7.448    1022   7.579 1022.97
   8.497  1027.7   9.482    1032   9.875    1034 119.718    1036 203.182    1042
#Mann= 4 ,-1 , 0
-275.623     .12       0-172.867     .12       0 -11.877     .05       0
   7.152     .12       0
#XS Ineff= 2 , 0
       0     -50    1042      62       0    1042
Permanent Ineff=
       F       F
#Block Obstruct= 1 ,-1
     100     193    1045
Bank Sta=-11.877,7.152
XS Rating Curve= 0 ,0
Minor Loss Coefficient=0.5
Exp/Cntr=0.5,0.3