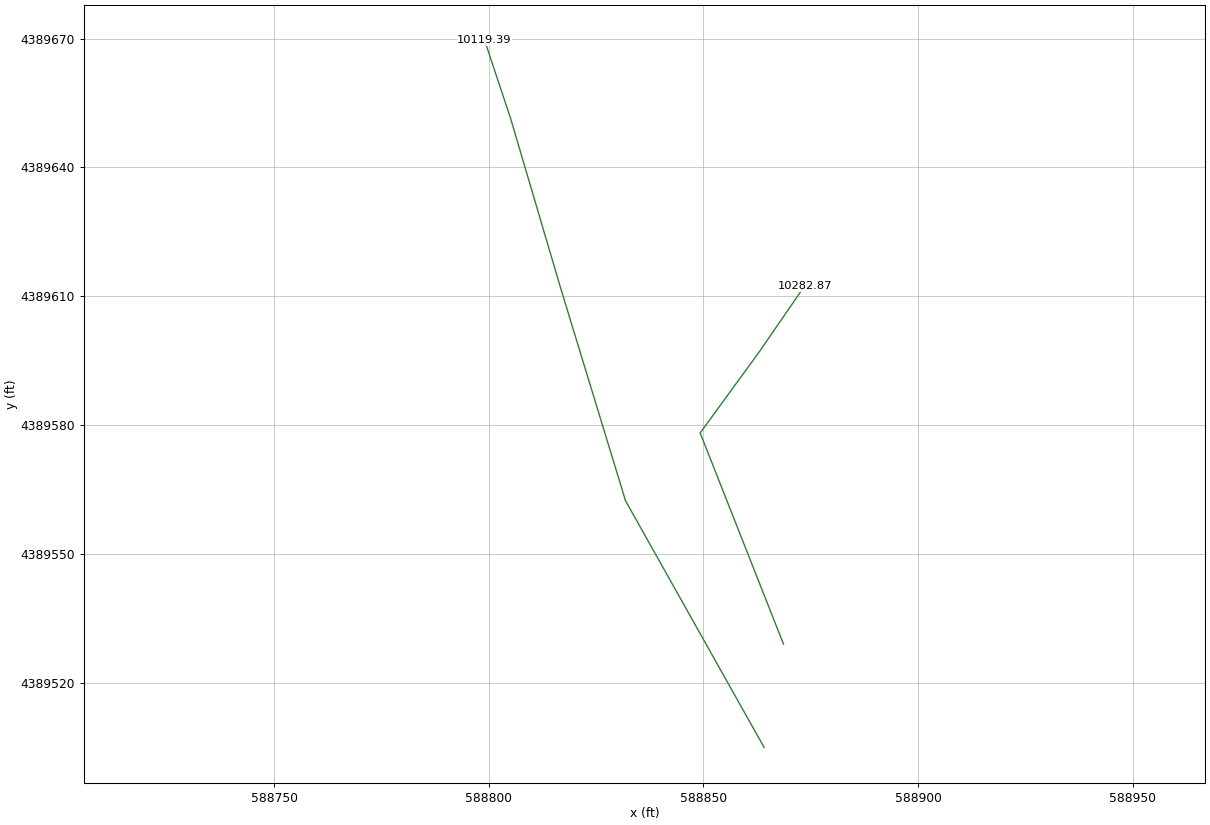
HEC-RAS study Pompono_Run_Detail_Study.prj: Pompono_Run_Detail_Study

--- Pompono_Run_Detail_Study.g01 (geometry) --- (continued)

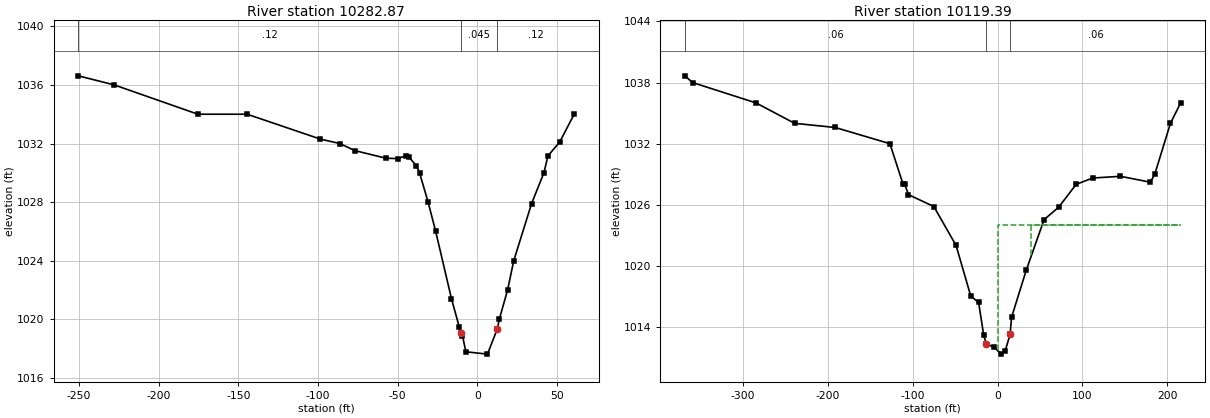
Type RM Length L Ch R = 1 ,10282.87,147.798,163.755,179.731
Node Name=AG
XS GIS Cut Line= 4
588868.6420858094389528.96478605588849.2324215694389578.14731466
 588863.042909744389597.10282689 588873.555461874389612.37025908
#Sta/Elev= 30
-250.427 1036.62-227.887    1036-175.361    1034-144.455    1034 -98.425  1032.3
 -86.286    1032 -76.936 1031.52 -57.415    1031 -49.869 1030.97 -44.554 1031.18
 -42.717 1031.06 -38.222 1030.47 -36.253    1030 -30.873    1028 -26.115    1026
 -16.207 1021.41 -11.319 1019.48 -10.007 1019.08   -9.32  1018.9  -7.185 1017.79
   6.365 1017.63  12.598 1019.36   13.78    1020  18.996    1022  22.867    1024
  34.022 1027.89  41.798    1030  44.357 1031.16   51.64 1032.09  60.794    1034
#Mann= 3 ,-1 , 0
-250.427     .12       0 -10.007    .045       0  12.598     .12       0
Bank Sta=-10.007,12.598
XS Rating Curve= 0 ,0
Exp/Cntr=0.5,0.3

Type RM Length L Ch R = 1 ,10119.39,103.912,103.34,102.651
BEGIN DESCRIPTION:
POP_10  - Raymond Park Foot Bridge - US
END DESCRIPTION:
XS GIS Cut Line= 5
588864.1462857534389504.87948975588831.8649173544389562.33124246
588816.8260851684389611.59606707588805.0577570234389651.49438756
588799.0074769484389669.66351579
#Sta/Elev= 30
 -368.63 1038.66-359.411    1038-284.609    1036-239.203    1034 -191.27 1033.59
-126.802    1032-111.251    1028-109.283    1028-104.952    1027-75.0319 1025.83
-48.8183 1022.01-31.4628 1017.03-22.2766 1016.43-16.2071 1013.18-12.9919 1012.32
-3.60888 1012.024.133808 1011.358.989392 1011.6514.86202 1013.2916.56804 1014.96
33.92347  1019.654.92059 1024.5572.14479 1025.7792.71541 1028.01112.1049 1028.63
144.9785  1028.8180.2143 1028.22185.5292 1029.04203.8689    1034215.8766    1036
#Mann= 3 , 0 , 0
 -368.63     .06       0-12.9919    .038       014.86202     .06       0
#XS Ineff= 2 , 0
       0     -30    1024      40       0    1024
Permanent Ineff=
       F       F
Bank Sta=-12.9919,14.86202
XS Rating Curve= 0 ,0
Exp/Cntr=0.5,0.3