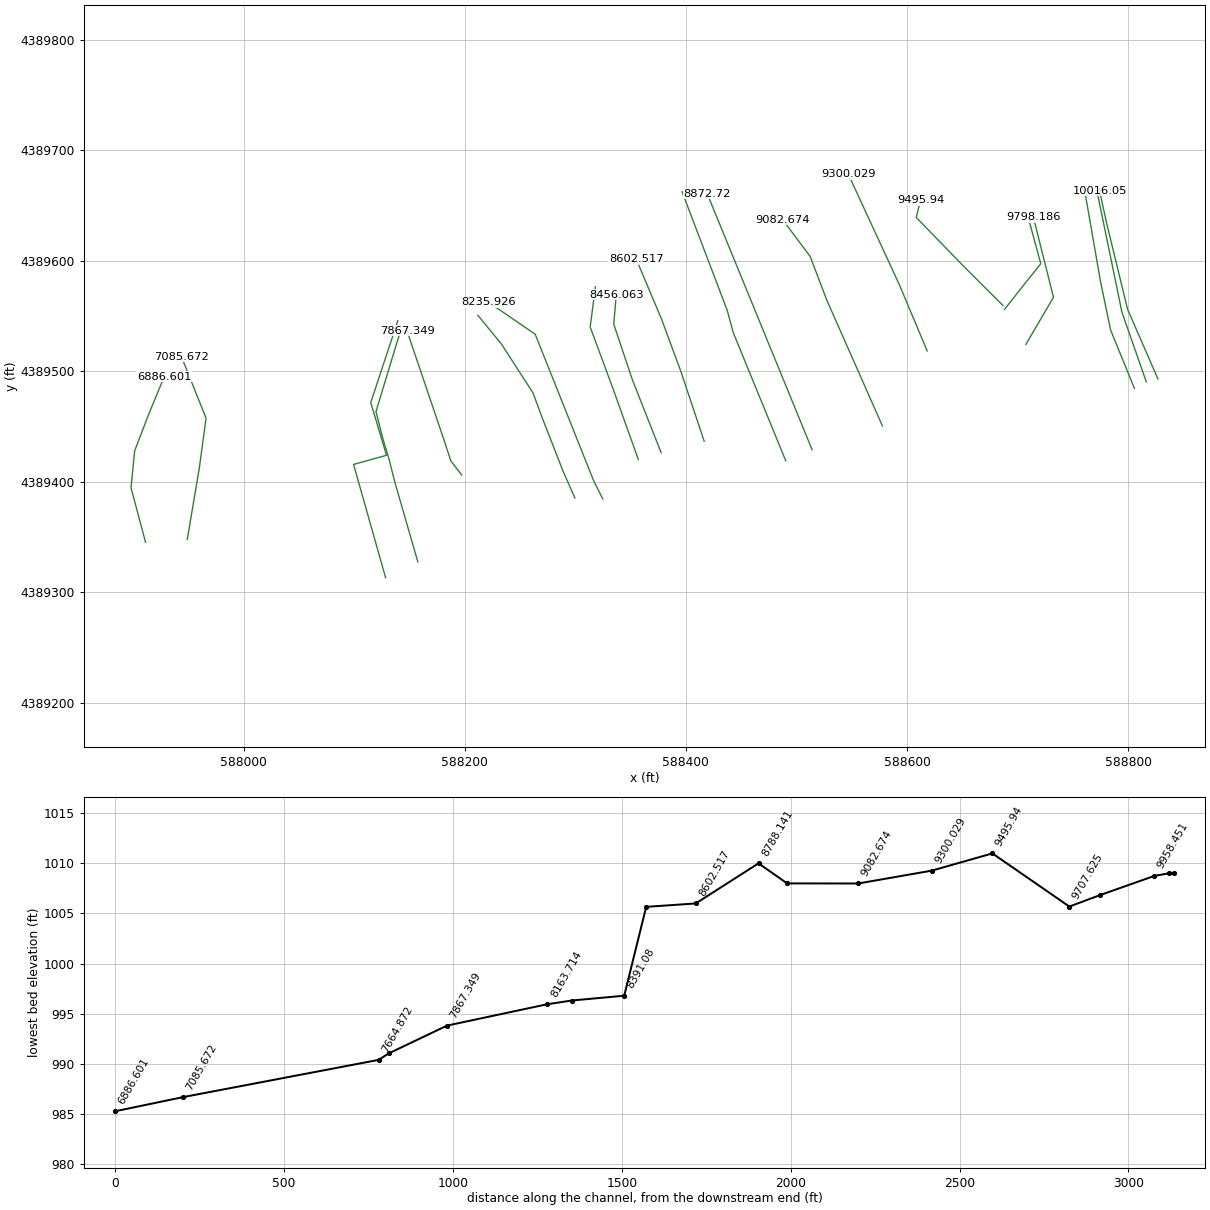
HEC-RAS study Pompono_Run_Detail_Study.prj: Pompono_Run_Detail_Study

--- Pompono_Run_Detail_Study.g01 (geometry) --- (continued)

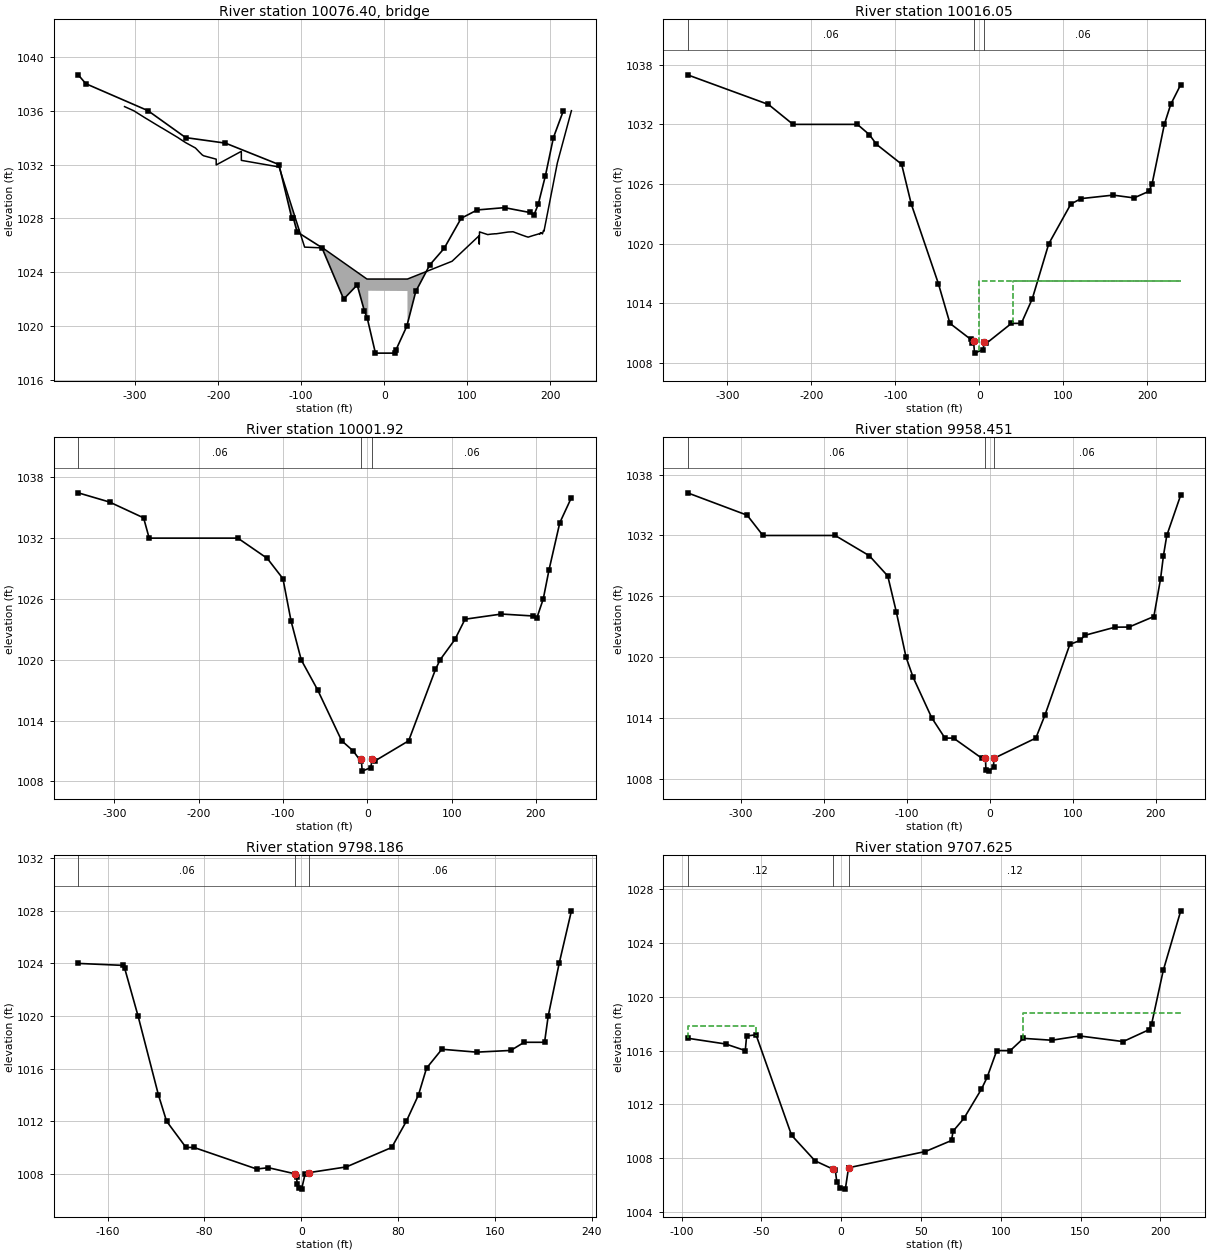
Type RM Length L Ch R = 3 ,10076.40,,,
BEGIN DESCRIPTION:
POP_10  - Raymond Park Foot Bridge
The lower smaller orifices at this structures are assumed to be blocked.
END DESCRIPTION:
Bridge Culvert--1,0,-1,-1, 0
Deck Dist Width WeirC Skew NumUp NumDn MinLoCord MaxHiCord MaxSubmerge Is_Ogee
3,53,2.6,0, 99, 99, , , 0.98, 0, 0,0,,
-312.792-301.932-301.866-301.834-299.307-289.695-288.776-288.087-287.365-286.611
-286.217-285.791 -285.43-275.587-269.091-268.304-267.877-257.608-248.455-246.782
-243.567 -241.04-239.006-227.425-225.982-222.734-221.585-219.125-218.009-217.484
-202.393-202.393-172.111-172.078-154.493-126.606 -95.865  -74.08  -21.03     -20
  -19.16  -19.13    4.34   27.95   28.04   81.76 114.106 114.533 114.828 124.703
 125.852 126.967 128.345  129.46 129.985 131.068 131.626 132.183 132.708 133.266
 133.824 134.382 134.939 149.276 155.215 166.993 167.583 168.174 168.764 169.388
 170.011 170.634 171.291 171.947 172.439  173.39  179.46 186.743 186.842 186.907
 187.367 187.531  187.99 188.088  188.22 188.318 188.482 188.909 189.007 189.138
 190.647 191.894 192.091 192.189 192.288 192.485 206.756 208.593 225.555
  1036.3    1036    1036    1036  1035.9 1035.53 1035.49 1035.47 1035.44 1035.41
  1035.4 1035.38 1035.37    1035 1034.76 1034.73 1034.72 1034.34    1034 1033.93
  1033.8  1033.7 1033.62 1033.23 1033.14 1032.93 1032.86 1032.71 1032.67 1032.65
  1032.4 1031.97 1032.98 1032.31 1032.12 1031.82 1025.87 1025.81 1023.51  1023.5
  1023.5  1023.5  1023.5  1023.5  1023.5 1024.82  1026.7 1026.09    1027  1026.8
 1026.81 1026.82 1026.83 1026.84 1026.84 1026.85 1026.85 1026.85 1026.86 1026.86
 1026.86 1026.86 1026.86 1026.99 1027.01 1026.74 1026.73 1026.72  1026.7 1026.69
 1026.68 1026.66 1026.65 1026.64 1026.63 1026.61 1026.73 1026.86 1026.87 1026.88
 1026.86 1026.88 1026.86 1026.88 1026.89  1026.9 1026.93  1026.9 1026.91 1026.94
 1026.85  1027.1 1027.08 1027.08 1027.07 1027.05 1031.54 1032.12    1036
                                                                                
                                                                                
                                                                                
                                                                                
 1022.63 1022.63 1022.62 1022.61 1022.61
                                                                                
                                                                                
                                                                                
                                                                                
                                                                        
-312.792-301.932-301.866-301.834-299.307-289.695-288.776-288.087-287.365-286.611
-286.217-285.791 -285.43-275.587-269.091-268.304-267.877-257.608-248.455-246.782
-243.567 -241.04-239.006-227.425-225.982-222.734-221.585-219.125-218.009-217.484
-202.393-202.393-172.111-172.078-154.493-126.606 -95.865  -74.08  -21.03     -20
  -19.16  -19.13    4.34   27.95   28.04   81.76 114.106 114.533 114.828 124.703
 125.852 126.967 128.345  129.46 129.985 131.068 131.626 132.183 132.708 133.266
 133.824 134.382 134.939 149.276 155.215 166.993 167.583 168.174 168.764 169.388
 170.011 170.634 171.291 171.947 172.439  173.39  179.46 186.743 186.842 186.907
 187.367 187.531  187.99 188.088  188.22 188.318 188.482 188.909 189.007 189.138
 190.647 191.894 192.091 192.189 192.288 192.485 206.756 208.593 225.555
  1036.3    1036    1036    1036  1035.9 1035.53 1035.49 1035.47 1035.44 1035.41
  1035.4 1035.38 1035.37    1035 1034.76 1034.73 1034.72 1034.34    1034 1033.93
  1033.8  1033.7 1033.62 1033.23 1033.14 1032.93 1032.86 1032.71 1032.67 1032.65
  1032.4 1031.97 1032.98 1032.31 1032.12 1031.82 1025.87 1025.81 1023.51  1023.5
  1023.5  1023.5  1023.5  1023.5  1023.5 1024.82  1026.7 1026.09    1027  1026.8
 1026.81 1026.82 1026.83 1026.84 1026.84 1026.85 1026.85 1026.85 1026.86 1026.86
 1026.86 1026.86 1026.86 1026.99 1027.01 1026.74 1026.73 1026.72  1026.7 1026.69
 1026.68 1026.66 1026.65 1026.64 1026.63 1026.61 1026.73 1026.86 1026.87 1026.88
 1026.86 1026.88 1026.86 1026.88 1026.89  1026.9 1026.93  1026.9 1026.91 1026.94
 1026.85  1027.1 1027.08 1027.08 1027.07 1027.05 1031.54 1032.12    1036
                                                                                
                                                                                
                                                                                
                                                                                
 1022.63 1022.63 1022.62 1022.62 1022.62
                                                                                
                                                                                
                                                                                
                                                                                
                                                                        
BR Coef=-1 , 1 , 0 ,, 0 ,,,0.8,-1,0.3,0,
WSPro=,,,, 1 ,,,, 0 ,,,, 0 ,,,,-1 ,-1 ,-1 , 0 , 0 , 0 , 0 , 0
BR U #Sta/Elev= 30
-368.631 1038.66-359.412    1038-284.609    1036-239.203    1034-191.271 1033.59
-126.803    1032-111.252    1028-109.283    1028-104.953    1027 -75.032 1025.83
 -48.818 1022.01 -32.546 1023.06 -23.851 1021.13 -20.538 1020.63 -10.564    1018
  12.565    1018  13.878  1018.2  27.263    1020  38.057 1022.58  54.921 1024.55
  72.145 1025.77  92.715 1028.01 112.105 1028.63 144.979  1028.8 175.424 1028.44
 180.214 1028.22 185.529 1029.04 194.256 1031.18 203.869    1034 215.877    1036
BR U #Mann= 4
-368.631     .06 -32.546     .06 -10.564    .035  13.878     .06
BR U Banks=-10.564,13.878
BR D #Sta/Elev= 30
-347.535 1036.98-251.178    1034-221.946    1032-145.339    1032-131.002 1030.96
-122.702    1030 -92.715    1028 -87.335    1026 -63.582    1026 -54.527 1025.13
 -37.762    1024  -32.25    1024 -28.609 1023.54 -18.996    1022 -17.191    1022
  -11.22    1020  -5.184 1018.42  -3.609    1018  14.501    1018  20.243 1019.02
  26.542    1020  28.609    1022  38.156    1024  84.021  1024.2  91.961 1024.66
 103.148    1026 206.526 1026.44 220.043    1032 227.589    1034 239.531    1036
BR D #Mann= 4
-347.535     .06 -63.582     .06  -5.184    .035  20.243     .06
BR D Banks=-5.184,20.243
BC Design=,, 0 ,, 0 ,,,,,,
BC Use User HTab Curves=0
BC User HTab FreeFlow(D)= 0

Type RM Length L Ch R = 1 ,10016.05,14.753,14.156,13.558
BEGIN DESCRIPTION:
POP_10  - Raymond Park Foot Bridge - DS
END DESCRIPTION:
XS GIS Cut Line= 4
588826.884485293 4389493.0380096588799.4463889544389556.04321838
588780.3872447184389634.37377135 588774.050452644389663.29624371
#Sta/Elev= 30
 -347.31 1036.98-250.953    1034-221.721    1032-145.114    1032-130.777 1030.96
-122.476    1030-92.4904    1028-81.0076    1024-48.7245    1016-34.9451    1012
-10.4376 1010.41 -8.7972    1010-6.79591 1010.19-5.71324 1009.014.522848 1009.36
6.032016 1010.178.492616    101038.24947    101250.02754    101263.05232 1014.47
 82.6715    1020109.0163    1024121.2209 1024.54159.2454 1024.89184.1466 1024.61
 201.863 1025.27205.6359    1026220.2683    1032227.8141    1034 239.797    1036
#Mann= 3 ,-1 , 0
 -347.31     .06       0-6.79591    .038       06.032016     .06       0
#XS Ineff= 2 , 0
       0     -30  1016.3      40       0  1016.3
Permanent Ineff=
       F       F
Bank Sta=-6.79591,6.032016
XS Rating Curve= 0 ,0
Exp/Cntr=0.5,0.3

Type RM Length L Ch R = 1 ,10001.92,44.055,43.539,43.024
Node Name=AF
XS GIS Cut Line= 3
588816.3445011624389490.53560157 588794.316604894389553.44632235
588771.776644612 4389662.7689397
#Sta/Elev= 30
-342.848 1036.47-305.644 1035.56 -265.29    1034-258.695    1032-153.513    1032
-118.638    1030-100.069    1028-90.4564 1023.83-78.3502 1019.98-58.8951 1017.02
-30.4177 1012.01-16.7368    1011 -7.9114    1010 -7.1241 1010.19-6.10704 1009.01
4.129048 1009.365.638216 1010.17 8.68936    101048.97759    101280.80135 1019.04
86.34589    1020103.8654    1022115.8731    1024159.0484 1024.51196.2199 1024.32
 200.813 1024.07208.6213    1026215.5438  1028.9228.2077 1033.51 242.028    1036
#Mann= 3 ,-1 , 0
-342.848     .06       0 -7.1241    .038       05.638216     .06       0
Bank Sta=-7.1241,5.638216
XS Rating Curve= 0 ,0
Exp/Cntr=0.3,0.1

Type RM Length L Ch R = 1 ,9958.451,159.889,160.54,160.908
Node Name=AE
XS GIS Cut Line= 4
 588805.65211703 4389484.4304575588784.0753247644389537.37421815
588775.0471486524389580.69544269588761.3616284834389659.21192366
#Sta/Elev= 30
-363.972 1036.21-292.122    1034-273.126    1032-186.087    1032-144.945    1030
-122.734    1028-112.531 1024.49-100.753    1020-92.1904    1018-69.7498    1014
-53.8379    1012-43.5034    1012-9.21904    1010-5.01962    1010-4.46188 1008.84
-.524928 1008.744.724352 1009.13 5.08524    101055.64237    101266.53462 1014.25
96.61956 1021.25109.4475 1021.65114.4671 1022.14151.2121 1022.95167.8785 1022.96
197.8322    1024 205.903 1027.71209.3807    1030 213.416    1032230.2466    1036
#Mann= 3 ,-1 , 0
-363.972     .06       0-5.01962    .038       0 5.08524     .06       0
Bank Sta=-5.01962,5.08524
XS Rating Curve= 0 ,0
Exp/Cntr=0.3,0.1

Type RM Length L Ch R = 1 ,9798.186,106.121,90.715,75.492
Node Name=AD
XS GIS Cut Line= 3
588707.4729878174389524.37754599588732.4208681254389566.96725052
  588714.16944394389639.62242742
#Sta/Elev= 30
-184.348    1024-147.373 1023.85-145.995 1023.65-134.873    1020-118.043    1014
-111.317    1012-95.2416    1010-88.6472    1010-36.8105 1008.36-27.1322 1008.46
-5.44612    1008-3.87134 1007.77 -3.2808  1007.2-1.83724 1006.89  .32808 1006.83
3.149568 1007.966.135096 1008.08 37.3027 1008.5274.80224    1010 86.9412    1012
96.94764    1014103.5749 1016.03116.2716 1017.47145.0114 1017.25173.2262 1017.38
184.2825    1018201.1458    1018204.1642    1020213.2192    1024223.3569    1028
#Mann= 3 ,-1 , 0
-184.348     .06       0-5.44612    .038       06.135096     .06       0
Bank Sta=-5.44612,6.135096
XS Rating Curve= 0 ,0
Exp/Cntr=0.3,0.1

Type RM Length L Ch R = 1 ,9707.625,196.543,227.793,250.843
Node Name=AC
XS GIS Cut Line= 4
588688.1059955784389555.96092238588705.9337477984389578.58622666
588720.9085719834389597.30399489588710.0790278494389637.28156339
#Sta/Elev= 30
  -96.26 1016.92 -72.343 1016.49 -60.072    1016 -59.252 1017.08 -53.346 1017.18
  -31.07  1009.7 -16.404  1007.8  -4.987 1007.17  -3.642  1007.1  -2.756 1006.24
   -.591 1005.77   2.625 1005.69   4.626 1007.28    5.02 1007.29  52.822 1008.49
   69.16 1009.31  70.112    1010  76.903 1010.95  87.894 1013.13  91.437    1014
  97.507    1016 105.971    1016 114.173 1016.91 131.923 1016.77 149.377 1017.09
 176.673 1016.67 192.651 1017.54 194.587    1018 201.837 1021.97 212.795  1026.4
#Mann= 3 ,-1 , 0
  -96.26     .12       0  -4.987    .038       0    5.02     .12       0
#XS Ineff= 2 ,-1
  -96.76  -53.14 1017.86  113.75  220.44 1018.77
Permanent Ineff=
       F       F
Bank Sta=-4.987,5.02
XS Rating Curve= 0 ,0
Exp/Cntr=0.3,0.1

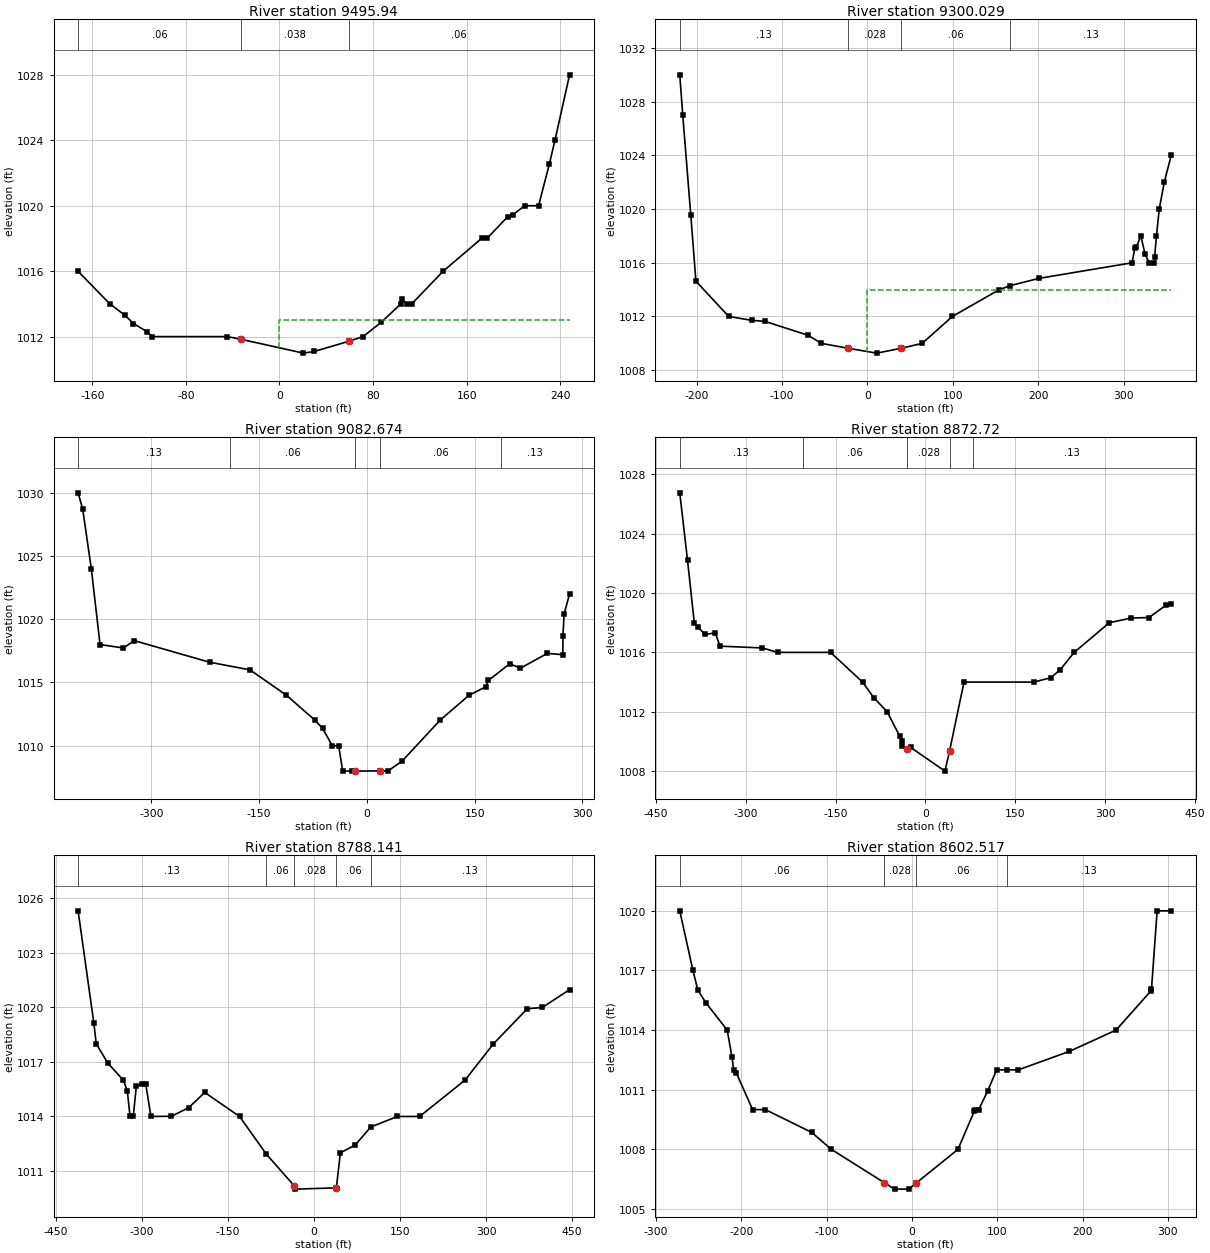
Type RM Length L Ch R = 1 ,9495.94 ,193.407,179.803,174.865
BEGIN DESCRIPTION:
Overland flow modeled here. Total flow was reduced by culvert capacity of 859 cfs
END DESCRIPTION:
Node Name=AB
XS GIS Cut Line= 4
        588686.8     4389559.466      588649.667     4389596.512
      588608.275     4389639.166      588612.207     4389654.798
#Sta/Elev= 27
 -172.08 1015.99 -144.98    1014-132.021  1013.3-124.803  1012.8-113.123  1012.3
-108.825    1012 -44.685    1012   -33.2 1011.84  20.472 1010.99  29.659 1011.09
  59.088 1011.71  71.358    1012  87.008 1012.88  103.74    1014 104.462 1014.28
 108.825    1014 112.992    1014 139.928    1016 172.703    1018 177.329    1018
 195.013 1019.33  199.18 1019.44 209.613    1020 221.391    1020 230.643 1022.56
   235.4    1024 247.867    1028
#Mann= 3 ,-1 , 0
 -172.08     .06       0   -33.2    .038       0  59.088     .06       0
#XS Ineff= 2 , 0
       0     -45    1013               0
Permanent Ineff=
       F       F
Bank Sta=-33.2,59.088
XS Rating Curve= 0 ,0
Exp/Cntr=0.3,0.1

Type RM Length L Ch R = 1 ,9300.029,217.636,217.724,216.928
Node Name=AA
XS GIS Cut Line= 3
588618.1848747134389518.40041792588593.0236344024389578.34238666
588546.764137831 4389678.4448039
#Sta/Elev= 29
-219.685    1030-216.175    1027-206.759 1019.53-200.787 1014.63-162.402    1012
-135.302 1011.71 -120.21 1011.64 -69.521  1010.6 -54.199    1010  -22.59 1009.63
  10.794 1009.27   39.61 1009.63  64.075    1010  99.311    1012 154.298    1014
 167.093  1014.3  200.82 1014.84 309.711    1016 312.894 1017.13 314.633 1017.18
 319.882    1018 324.738 1016.67 329.528    1016 335.597    1016 335.991 1016.43
 338.189    1018 341.404    1020  347.31    1022 355.413    1024
#Mann= 4 ,-1 , 0
-219.685     .13       0  -22.59    .028       0   39.61     .06       0
 167.093     .13       0
#XS Ineff= 2 , 0
       0     -85    1014               0
Permanent Ineff=
       F       F
Bank Sta=-22.59,39.61
XS Rating Curve= 0 ,0
Exp/Cntr=0.3,0.1

Type RM Length L Ch R = 1 ,9082.674,210.78,210.314,210.365
Node Name=Z
XS GIS Cut Line= 4
588577.7470582144389450.50012108588527.3666655914389564.44350649
588512.4009854064389603.81757097588487.3708090974389637.27851539
#Sta/Elev= 30
 -401.87    1030-395.571 1028.73-383.497    1024-371.358    1018-338.747 1017.73
 -323.72 1018.31-218.701  1016.6-162.631    1016-112.073    1014 -71.883    1012
  -61.68 1011.38 -47.999    1010 -39.206    1010 -33.629    1008  -20.75 1007.99
  -16.19 1007.99   18.46 1008.01  29.429    1008  49.278 1008.79  101.64    1012
 142.487    1014 165.584 1014.66  169.16 1015.16 198.885 1016.48 213.878 1016.13
 251.148  1017.3 272.802  1017.2 273.031 1018.69 274.573 1020.41 282.185    1022
#Mann= 5 ,-1 , 0
 -401.87     .13       0-191.142     .06       0  -16.19    .028       0
   18.46     .06       0 186.877     .13       0
Bank Sta=-16.19,18.46
XS Rating Curve= 0 ,0
Exp/Cntr=0.3,0.1

Type RM Length L Ch R = 1 ,8872.72 ,84.731,84.721,82.673
Node Name=Y
XS GIS Cut Line= 2
588514.1170094274389429.09706481588419.3394482564389660.43721967
#Sta/Elev= 30
-410.105 1026.75-397.146  1022.2 -385.86    1018-379.396 1017.69-367.946 1017.21
-350.919 1017.31-342.979 1016.42-272.408  1016.3-246.588    1016-158.497    1016
-104.987    1014 -86.352 1012.95 -63.911    1012 -42.946 1010.35 -39.304    1010
 -38.911 1009.66 -30.282 1009.46 -24.902  1009.6  32.513    1008   40.21 1009.36
  64.304    1014 180.971    1014 208.957 1014.29 224.606 1014.82 248.228    1016
  306.89    1018  343.11 1018.31 373.196 1018.35 400.787 1019.16 410.105 1019.23
#Mann= 5 ,-1 , 0
-410.105     .13       0-204.429     .06       0 -30.282    .028       0
   40.21     .06       0  79.068     .13       0
Bank Sta=-30.282,40.21
XS Rating Curve= 0 ,0
Exp/Cntr=0.3,0.1

Type RM Length L Ch R = 1 ,8788.141,186.498,185.94,187.42
Node Name=X
XS GIS Cut Line= 4
     588490.3182    4389418.9932     588442.8325    4389534.8992
     588437.3421    4389555.1585     588396.4991    4389662.4473
#Sta/Elev= 30
 -411.02 1025.32  -383.6 1019.14 -379.43    1018 -359.15 1016.93 -332.19    1016
 -325.33 1015.42 -320.51    1014  -314.9    1014 -309.58 1015.66 -299.97  1015.8
 -293.27 1015.81 -284.15    1014 -248.36 1014.01  -218.5 1014.48 -190.32 1015.32
 -129.66    1014  -82.87 1011.92  -34.25 1010.18  -32.25    1010   39.04 1010.07
   46.03    1012   71.62 1012.42   98.98 1013.42  145.44    1014  184.22    1014
  263.25    1016  312.86    1018  371.78 1019.93  398.03    1020  445.44 1020.98
#Mann= 5 ,-1 , 0
 -411.02     .13       0  -82.87     .06       0  -34.25    .028       0
   39.04     .06       0   98.98     .13       0
Bank Sta=-34.25,39.04
XS Rating Curve= 0 ,0
Exp/Cntr=0.3,0.1

Type RM Length L Ch R = 1 ,8602.517,146.658,146.703,146.075
Node Name=W
XS GIS Cut Line= 4
588416.5109042214389436.78716891588395.3486399594389500.13680169
588377.9537037444389547.17353827588355.1546634634389601.19324294
#Sta/Elev= 30
 -272.08    1020-256.627    1017 -250.82    1016-241.503 1015.38 -216.47    1014
-210.827 1012.64-208.957    1012-205.807 1011.85-186.713    1010-171.686    1010
 -117.29 1008.85  -94.39    1008  -32.11 1006.32 -20.341    1006  -3.871    1006
   4.921  1006.3   53.97    1008  73.294 1009.93  74.508    1010  78.281    1010
  88.976 1010.95  99.344    1012 111.614    1012  124.77    1012 184.678 1012.93
  239.37    1014 280.348 1015.98 280.873 1016.06 287.467    1020  303.97    1020
#Mann= 4 ,-1 , 0
 -272.08     .06       0  -32.11    .028       0   4.921     .06       0
 111.614     .13       0
Bank Sta=-32.11,4.921
XS Rating Curve= 0 ,0
Exp/Cntr=0.3,0.1

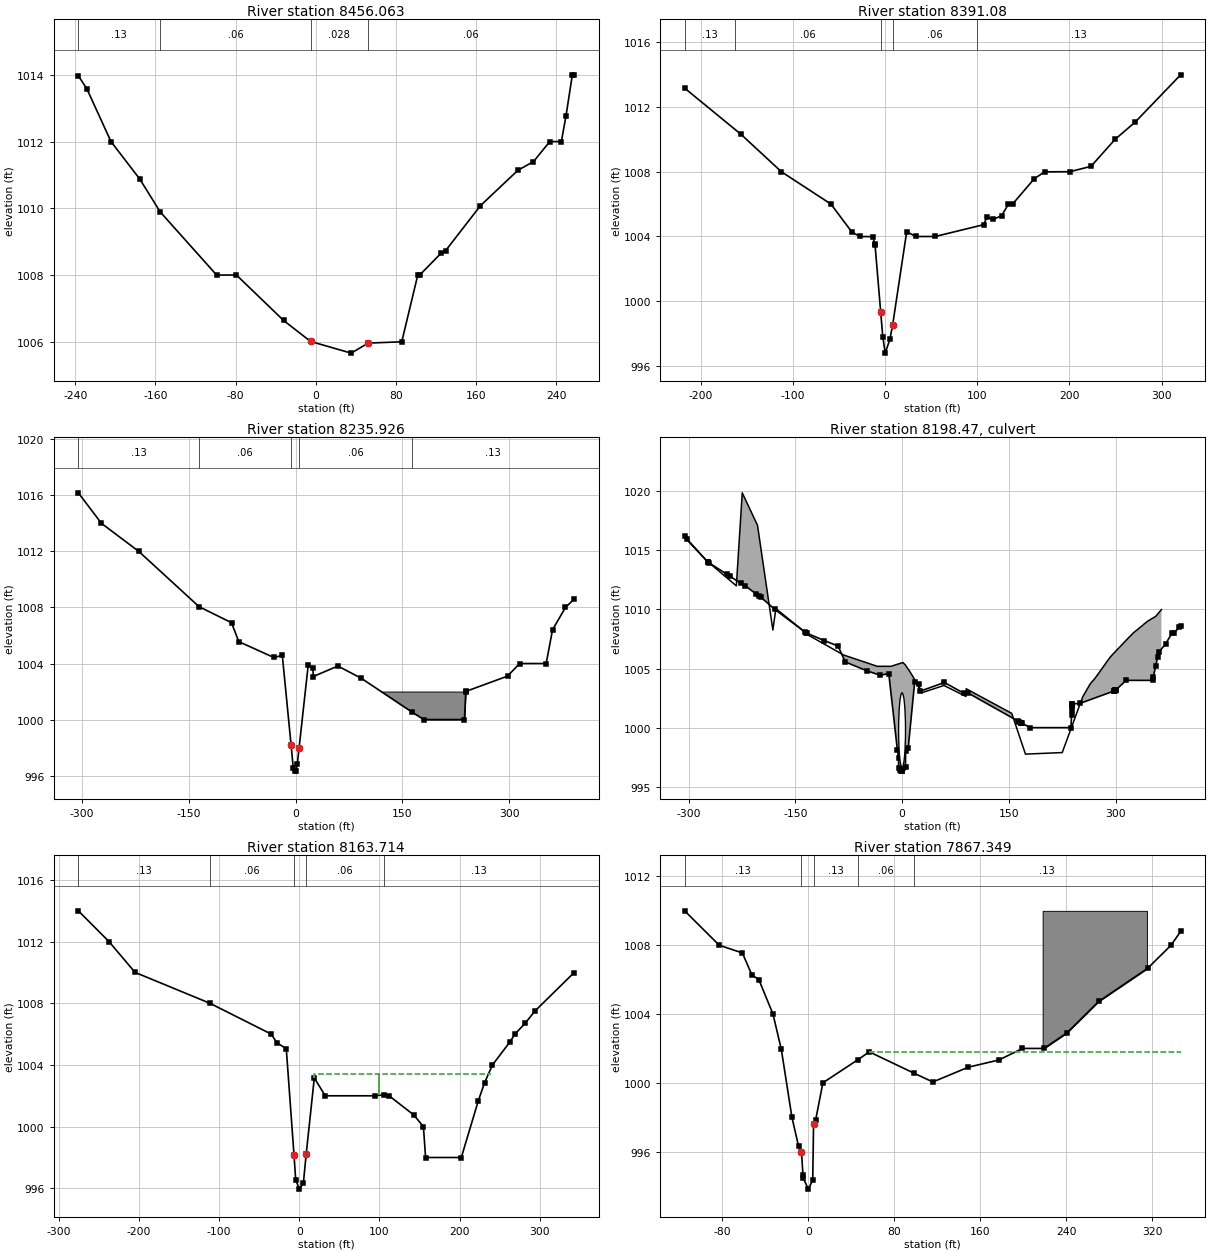
Type RM Length L Ch R = 1 ,8456.063,65.37,65.095,65.628
Node Name=V
XS GIS Cut Line= 4
 588377.594039744389426.41787278588351.618983419 4389492.2363856
 588334.705631214389542.74174622588337.0464952394389569.43613055
#Sta/Elev= 24
-236.942 1013.97-228.412 1013.58-204.364    1012-175.459 1010.87-155.184 1009.89
 -98.917    1008 -79.134    1008 -32.152 1006.64  -5.151 1006.01  35.335 1005.66
   52.25 1005.96  85.827    1006 101.804    1008 103.707    1008 125.262 1008.66
  129.56 1008.73  164.37 1010.08 201.772 1011.14  217.29  1011.4 233.563    1012
 245.112    1012 249.738 1012.77  256.07    1014 257.874    1014
#Mann= 4 ,-1 , 0
-236.942     .13       0-155.184     .06       0  -5.151    .028       0
   52.25     .06       0
Bank Sta=-5.151,52.25
XS Rating Curve= 0 ,0
Exp/Cntr=0.3,0.1

Type RM Length L Ch R = 1 ,8391.08 ,154.822,155.417,155.877
Node Name=U
XS GIS Cut Line= 4
588356.9285994854389420.29748871588334.5227512084389482.99484948
588313.4062069474389540.09608219588318.1732790064389576.44653064
#Sta/Elev= 30
-217.684 1013.15-156.726 1010.31-112.861    1008 -58.989    1006 -36.319 1004.28
  -27.69    1004 -13.156 1003.99 -11.483 1003.49 -11.188 1003.55  -4.954  999.34
   -2.69  997.82   -.033   996.8    5.02  997.65    7.95  998.51  23.294  1004.3
  33.104    1004  54.265    1004 106.923 1004.73 110.302 1005.18 117.323 1005.06
 126.312 1005.28 133.793    1006 138.255    1006 161.877 1007.57 173.163 1007.99
 200.459    1008 223.458 1008.33 249.606    1010 271.391 1011.06 320.768 1013.98
#Mann= 5 ,-1 , 0
-217.684     .13       0-162.927     .06       0  -4.954    .035       0
    7.95     .06       0 100.033     .13       0
Bank Sta=-4.954,7.95
XS Rating Curve= 0 ,0
Exp/Cntr=0.5,0.3

Type RM Length L Ch R = 1 ,8235.926,72.741,72.334,71.924
BEGIN DESCRIPTION:
POP_08 - Chick Fil A Driveway - US
END DESCRIPTION:
XS GIS Cut Line= 5
588324.8483990884389384.51092026588316.6980469874389400.68665646
588269.8624784094389518.02551391588263.6597983324389533.56421811
 588221.475477814389562.45011446
#Sta/Elev= 30
-305.217 1016.18-272.703    1014-220.308    1012-135.761 1008.06 -90.026 1006.91
  -79.79 1005.56 -30.545 1004.43 -18.668 1004.58   -6.28  998.16  -3.314  996.55
   -.623  996.32    .427  996.33   2.428  996.83   4.921  997.99  17.717 1003.88
  24.344 1003.67  24.803 1003.07  59.383 1003.82  92.159 1002.95 163.058 1000.55
 180.249    1000 237.238    1000 239.042    1002 239.272 1002.01 297.736  1003.1
 314.731    1004 352.034    1004 360.991 1006.41 379.167    1008 391.339  1008.6
#Mann= 5 ,-1 , 0
-305.217     .13       0-135.761     .06       0   -6.28     .04       0
   4.921     .06       0 163.058     .13       0
#XS Ineff= 1 ,-1
      70     320  1003.5
Permanent Ineff=
       F
#Block Obstruct= 1 ,-1
     105     255    1002
Bank Sta=-6.28,4.921
XS Rating Curve= 0 ,0
Exp/Cntr=0.5,0.3

Type RM Length L Ch R = 2 ,8198.47 ,,,
BEGIN DESCRIPTION:
POP_08 - Chick Fil A Driveway
END DESCRIPTION:
Bridge Culvert--1,0,-1,-1, 0
Deck Dist Width WeirC Skew NumUp NumDn MinLoCord MaxHiCord MaxSubmerge Is_Ogee
14,34,2.6,0, 51, 51, , , 0.98, 0, 0,0,,
-303.871-289.436-272.474-266.568-232.808-224.508-216.634-203.051-181.496-177.231
-129.987 -82.251 -34.843 -15.486       0   1.083   4.429  10.564  15.748  27.625
  58.858  89.764  90.092 154.068  173.36     225 253.937 264.403 268.602 270.112
 270.702 273.983 274.081 289.108 292.946 296.325 306.398 313.648 316.732  320.21
  321.26 323.819 324.573 328.412 329.134 333.858 337.467 339.665 345.079 356.365
  364.37
    1016 1015.07    1014 1013.72    1012 1019.87 1018.86 1017.12 1008.26 1010.07
 1007.77 1006.15 1005.19 1005.19 1005.49 1005.51 1005.32 1004.78 1004.27 1002.95
 1003.57 1002.64 1003.29 1001.21  997.76  997.89 1002.63 1003.71    1004 1004.11
 1004.15 1004.42 1004.42  1005.7    1006 1006.23 1006.86 1007.32 1007.52 1007.73
 1007.78 1007.95    1008 1008.19 1008.22 1008.46 1008.63 1008.75 1009.01 1009.42
 1009.99
                                                                                
                                                                                
                                                                                
                                                                                
                                                                                
        
-303.871-289.436-272.474-266.568-232.808-224.508-216.634-203.051-181.496-177.231
-129.987 -82.251 -34.843 -15.486       0   1.083   4.429  10.564  15.748  27.625
  58.858  89.764  90.092 154.068  173.36     225 253.937 264.403 268.602 270.112
 270.702 273.983 274.081 289.108 292.946 296.325 306.398 313.648 316.732  320.21
  321.26 323.819 324.573 328.412 329.134 333.858 337.467 339.665 345.079 356.365
  364.37
    1016 1015.07    1014 1013.72    1012 1019.87 1018.86 1017.12 1008.26 1010.07
 1007.77 1006.15 1005.19 1005.19 1005.49 1005.51 1005.32 1004.78 1004.27 1002.95
 1003.57 1002.64 1003.29 1001.21  997.76  997.89 1002.63 1003.71    1004 1004.11
 1004.15 1004.42 1004.42  1005.7    1006 1006.23 1006.86 1007.32 1007.52 1007.73
 1007.78 1007.95    1008 1008.19 1008.22 1008.46 1008.63 1008.75 1009.01 1009.42
 1009.99
                                                                                
                                                                                
                                                                                
                                                                                
                                                                                
        
BR Coef=-1 , 0 , 0 ,, 0 ,,,0.8,0,,0,
WSPro=,,,, 1 ,,,, 0 ,,,, 0 ,,,,-1 ,-1 ,-1 , 0 , 0 , 0 , 0 , 0
Culvert=5,6.3,9.7,40.5,0.024,0.5,1,41,3,996.64,0,996.18,0,Culvert #1  , 0 ,16.5
Culvert Bottom n=0.024
BR U #Sta/Elev= 74
-305.217 1016.18-302.756    1016-272.703    1014-272.638    1014 -271.49 1013.96
-245.801 1012.96-242.028 1012.82-226.542 1012.22-220.308    1012-205.774 1011.35
-200.558 1011.13-198.524 1011.04-178.576    1010-135.761 1008.06-134.318    1008
-134.088    1008-109.416 1007.37 -90.026 1006.91  -79.79 1005.56 -49.114  1004.8
 -30.545 1004.43 -18.668 1004.58   -6.61  998.14  -4.921   997.4  -4.914  996.55
  -2.657   996.4   -1.64  996.33   -.623  996.32    .427  996.33   1.115  996.58
    4.85  996.64   4.921  997.99    8.61  998.24  17.717 1003.88  24.344 1003.67
  24.803 1003.07  59.383 1003.82  86.909 1002.91  92.159 1002.95 163.058 1000.55
 164.862 1000.48 166.864 1000.42 166.995 1000.42 167.651 1000.39 167.782 1000.39
 168.701 1000.36 180.249    1000 237.238    1000 238.222  1001.1 238.583 1001.48
 238.911 1001.84 238.944  1001.9 239.042    1002 239.206 1001.92 239.272 1002.01
 249.869 1002.05 297.736  1003.1  298.13 1003.12 298.556 1003.13 299.016 1003.15
 299.475 1003.16 299.967 1003.18 300.492 1003.19 314.731    1004 352.034    1004
  352.92  1004.3 356.332 1005.21 359.121    1006 360.991 1006.41  370.44  1007.1
 379.167    1008 381.398    1008 389.665 1008.49 391.339  1008.6
BR U #Mann= 5
-305.217     .13-135.761     .06   -6.61    .032    8.61     .06 163.058     .13
BR U Banks=-6.61,8.61
BR D #Sta/Elev= 98
 -275.82 1013.99-238.058    1012-237.631    1012 -229.56 1011.51-228.707 1011.45
 -227.92  1011.4-205.052    1010-198.327 1009.87 -111.68    1008  -85.86 1007.37
 -85.597 1007.36 -85.072 1007.35 -84.514 1007.33 -83.957 1007.32 -83.071  1007.3
 -63.025 1006.69 -52.625 1006.42  -46.03 1006.26 -44.259 1006.21   -37.5 1006.06
 -35.105    1006 -33.169 1005.86 -32.972 1005.84 -28.609  1005.5 -27.986 1005.44
 -16.273 1005.05   -6.28  998.16  -4.921  996.85  -4.895  996.18    .197  995.95
   4.921  996.18   5.052  997.45  18.701 1003.16  32.316    1002  94.357    1002
 105.873 1002.07 106.037 1002.07 106.201 1002.06 106.594 1002.06 106.791 1002.05
 107.021 1002.05 110.696    1002 112.073    1002 129.429 1001.29 133.235  1001.1
 143.012 1000.75  143.57 1000.72 144.127  1000.7 149.049 1000.38 149.344 1000.37
 149.672 1000.36 153.478  1000.1 153.576 1000.09 154.888    1000 155.249  999.71
 155.971  999.15 157.579     998 202.165     998 213.714    1000 217.848 1000.74
 219.554 1001.02 220.866 1001.25 222.277 1001.49 222.671 1001.56 223.261 1001.65
 223.458 1001.69 223.622 1001.71 225.525    1002 231.037 1002.82 231.135 1002.84
 234.022 1003.17 235.072 1003.31 235.958 1003.41 236.188 1003.44 236.352 1003.46
 237.369 1003.57 237.434 1003.58 238.714 1003.73 239.304  1003.8 239.961 1003.87
  240.65 1003.95 241.043    1004  242.52  1004.1 242.881 1004.12 244.259 1004.21
 244.554 1004.24 244.948 1004.26 245.374 1004.29 245.997 1004.34 262.664 1005.48
  269.16    1006 271.949 1006.15 281.594 1006.69 294.554 1007.52 296.161 1007.61
 298.556 1007.74 303.215    1008 343.012 1009.99
BR D #Mann= 5
 -275.82     .13 -111.68     .06   -6.28    .032   5.052     .06 105.873     .13
BR D Banks=-6.28,5.052
BC Design=,, 0 ,, 0 ,,,,,,
BC Use User HTab Curves=0
BC User HTab FreeFlow(D)= 0

Type RM Length L Ch R = 1 ,8163.714,297.5188,296.871,296.3757
BEGIN DESCRIPTION:
POP_08 - Chick Fil A Driveway - DS
END DESCRIPTION:
XS GIS Cut Line= 6
588299.5378067754389385.42532028588288.7174066424389410.10802458
588269.7527504074389458.69619318588261.6907903074389480.47110545
588233.4053499584389524.29524999588211.7980776914389550.71531432
#Sta/Elev= 29
 -275.82 1013.99-237.631    1012-205.052    1010 -111.68    1008 -35.105    1006
 -27.986 1005.44 -16.273 1005.05   -6.61  998.14  -4.495  996.53    .197  995.95
   5.052  996.35    8.61  998.24  18.701 1003.16  32.316    1002  94.357    1002
 105.873 1002.07 112.073    1002 143.012 1000.75 154.888    1000 157.579     998
 202.165     998 223.458 1001.69 231.135 1002.84 241.043    1004 262.664 1005.48
  269.16    1006 281.594 1006.69 294.554 1007.52 343.012 1009.99
#Mann= 5 ,-1 , 0
 -275.82     .13       0 -111.68     .06       0   -6.61     .04       0
    8.61     .06       0 105.873     .13       0
#XS Ineff= 2 ,-1
    18.7     100  1003.4     100     239  1003.4
Permanent Ineff=
       F       T
Bank Sta=-6.61,8.61
XS Rating Curve= 0 ,0
Exp/Cntr=0.5,0.3

Type RM Length L Ch R = 1 ,7867.349,173.6611,172.6007,172.0986
Node Name=T
XS GIS Cut Line= 5
588197.2012055114389406.16696053588187.3775013894389419.00208869
588181.2418773134389437.79910492 588163.155045094389491.19396958
588147.6681568984389536.90787415
#Sta/Elev= 30
-114.862 1009.99 -82.808    1008 -61.286 1007.55 -52.526 1006.28 -45.997    1006
 -32.841    1004 -25.066 1001.94 -15.223     998  -9.055  996.32  -6.365     996
   -4.92  994.63   -4.51  994.44     .07  993.82    4.14  994.35   4.921  997.63
   6.791  997.82  13.583    1000  46.293 1001.35  56.759  1001.8  98.031 1000.57
 115.814 1000.05  148.95 1000.91 177.395 1001.33 199.245    1002 219.324    1002
 240.486  1002.9 270.112 1004.73 315.715 1006.66 337.434    1008 346.358  1008.8
#Mann= 5 ,-1 , 0
-114.862     .13       0  -6.365     .04       0   4.921     .13       0
  46.293     .06       0  98.031     .13       0
#XS Ineff= 2 , 0
       0                   56.76       0  1001.8
Permanent Ineff=
       F       T
#Block Obstruct= 1 ,-1
     218     315    1010
Bank Sta=-6.365,4.921
XS Rating Curve= 0 ,0
Exp/Cntr=0.5,0.3

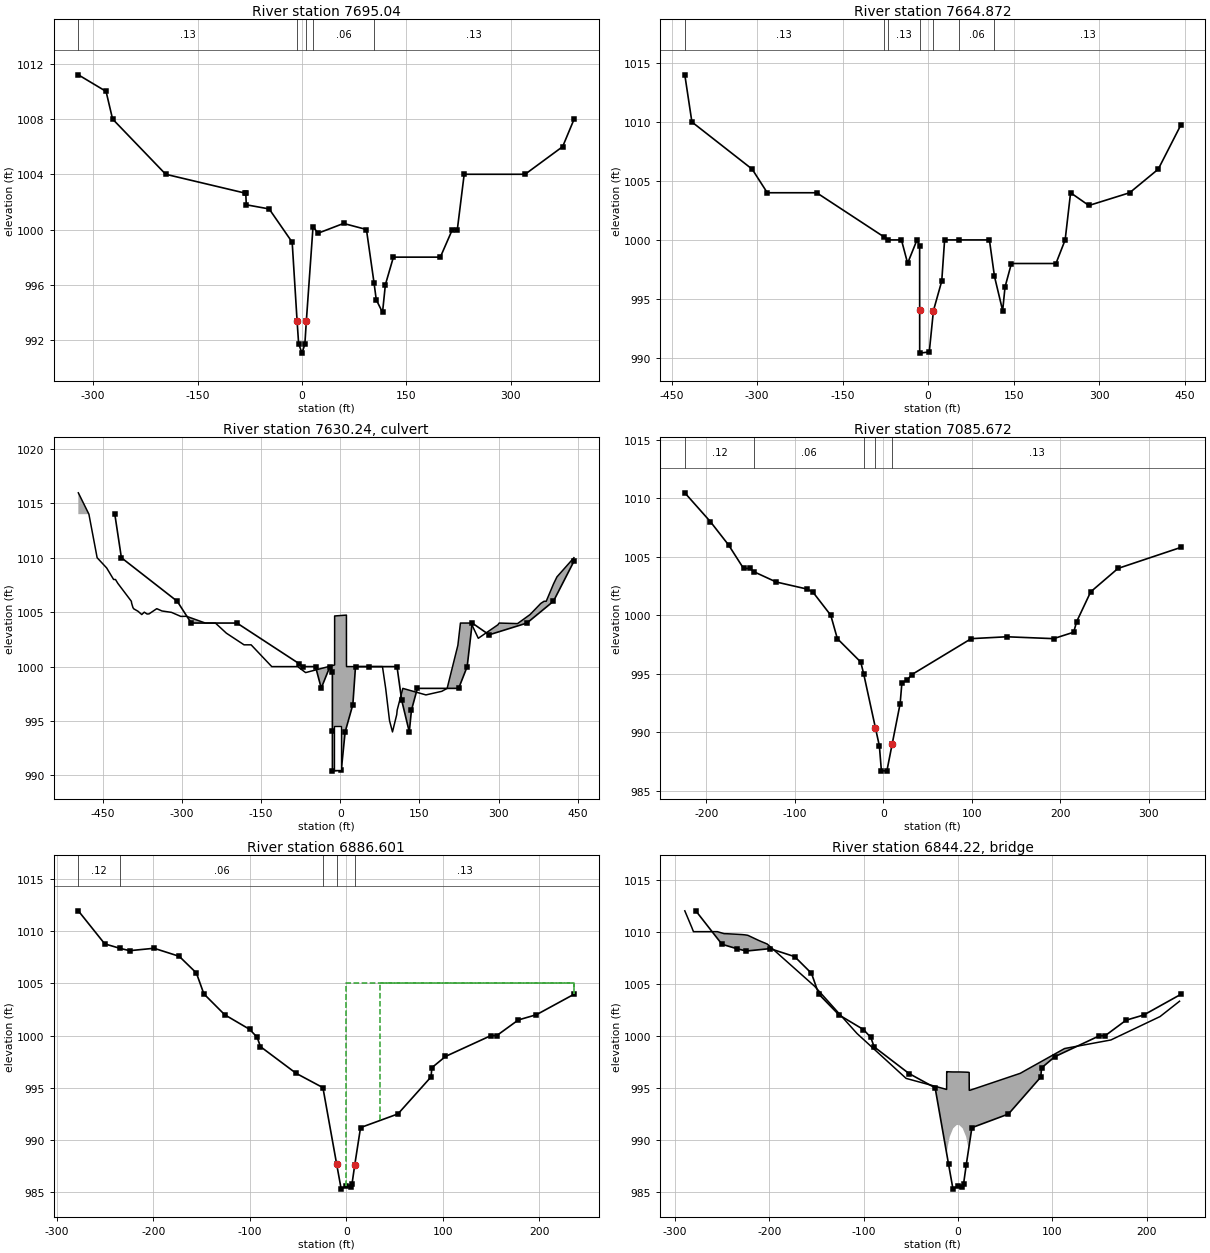
Type RM Length L Ch R = 1 ,7695.04 ,69.35168,30.21774,3.835079
BEGIN DESCRIPTION:
POP_07 - Patteson Drive - US
END DESCRIPTION:
Node Name=S
XS GIS Cut Line= 6
588157.5711090214389327.60780756588137.1708447694389398.26654443
588131.1175166944389421.88549673588125.8475246294389439.31700894
588119.6814205524389463.62785724588141.7550368254389536.22512214
#Sta/Elev= 30
 -321.26  1011.2 -281.43    1010 -272.08    1008-195.768    1004 -82.087 1002.64
 -80.741 1002.61 -79.987 1001.79 -47.146 1001.49 -14.075  999.08   -7.04  993.39
  -4.823  991.74       0  991.05   4.134  991.69     6.3   993.4  15.879 1000.21
  22.999  999.73  59.744 1000.44  92.585    1000 103.478  996.15 106.726  994.91
 115.715     994 119.783     996 131.332     998 198.753     998 216.043    1000
 223.163    1000 233.005    1004 320.505    1004 374.442    1006 390.978    1008
#Mann= 5 ,-1 , 0
 -321.26     .13       0   -7.04     .04       0     6.3     .13       0
  15.879     .06       0 103.478     .13       0
Bank Sta=-7.04,6.3
XS Rating Curve= 0 ,0
Minor Loss Coefficient=0.5
Exp/Cntr=0.5,0.3

Type RM Length L Ch R = 1 ,7664.872,511.9669,580.1851,563.6526
XS GIS Cut Line= 5
     588128.4068    4389313.3391     588099.4189     4389415.775
     588129.2116    4389424.0717     588114.9555    4389471.7378
     588139.4469    4389545.7563
#Sta/Elev= 30
-426.837    1014 -414.37    1010-308.661    1006-282.152    1004-195.505    1004
 -77.559 1000.26  -71.26    1000 -46.818    1000 -35.958  998.02 -19.521    1000
   -14.9  999.51  -14.84 994.044   -14.8   990.4       2   990.5   9.318     994
  23.885  996.51  28.904    1000  54.462    1000  107.48    1000 116.404   996.9
 130.742     994 134.875     996 146.063     998 224.213     998 240.354    1000
 249.902    1004 281.955 1002.92 353.478    1004 403.675    1006 442.913 1009.71
#Mann= 7 ,-1 , 0
-426.837     .13       0 -77.559     .06       0  -71.26     .13       0
  -14.84     .04       0   9.318     .13       0  54.462     .06       0
 116.404     .13       0
#XS Ineff= 1 ,-1
     100     250   998.5
Permanent Ineff=
       T
Bank Sta=-14.84,9.318
XS Rating Curve= 0 ,0
Exp/Cntr=0.5,0.3

Type RM Length L Ch R = 2 ,7630.24 ,,,
BEGIN DESCRIPTION:
POP_07 - Patteson Drive
END DESCRIPTION:
Bridge Culvert--1,0,-1,-1, 0
Deck Dist Width WeirC Skew NumUp NumDn MinLoCord MaxHiCord MaxSubmerge Is_Ogee
7.1,540,2.6,0, 58, 58, , , 0.98, 0, 0,0,,
 -495.89-475.877-460.293-442.248-429.092-425.548-421.021-395.496-395.004-392.478
-391.067-382.832-375.811-371.021-365.772-362.064-347.399-337.556-319.446-301.894
  -291.1-255.404-236.342-215.608-182.143-168.724-129.682 -80.634 -65.509 -10.653
 -10.588  11.722   11.82  11.951  79.963  86.033  93.316  98.927 106.965 107.785
 118.513 162.214 192.266 202.404 222.745 227.568 247.713 261.394   298.5 300.862
 335.672 359.425 379.635 385.902 390.003 403.881 410.311 442.463
 1015.96    1014    1010 1009.06    1008    1008 1007.64    1006 1005.83 1005.42
 1005.31 1005.08 1004.78    1005 1004.83 1004.84 1005.32 1005.11 1004.98 1004.61
 1004.62    1004    1004 1003.07    1002    1002    1000    1000  999.45 1000.15
 1004.65 1004.73 1000.23    1000    1000     998  995.04     994  995.59     996
     998   997.4  997.73     998 1001.96    1004    1004  1002.6 1003.84    1004
 1003.95 1004.78  1005.8    1006    1006  1007.6 1008.24    1010
                                                                                
                                                                                
                                                                                
                                                                                
                                                                                
                                                                
 -495.89-475.877-460.293-442.248-429.092-425.548-421.021-395.496-395.004-392.478
-391.067-382.832-375.811-371.021-365.772-362.064-347.399-337.556-319.446-301.894
  -291.1-255.404-236.342-215.608-182.143-168.724-129.682 -80.634 -65.509 -10.653
 -10.588  11.722   11.82  11.951  79.963  86.033  93.316  98.927 106.965 107.785
 118.513 162.214 192.266 202.404 222.745 227.568 247.713 261.394   298.5 300.862
 335.672 359.425 379.635 385.902 390.003 403.881 410.311 442.463
 1015.96    1014    1010 1009.06    1008    1008 1007.64    1006 1005.83 1005.42
 1005.31 1005.08 1004.78    1005 1004.83 1004.84 1005.32 1005.11 1004.98 1004.61
 1004.62    1004    1004 1003.07    1002    1002    1000    1000  999.45 1000.15
 1004.65 1004.73 1000.23    1000    1000     998  995.04     994  995.59     996
     998   997.4  997.73     998 1001.96    1004    1004  1002.6 1003.84    1004
 1003.95 1004.78  1005.8    1006    1006  1007.6 1008.24    1010
                                                                                
                                                                                
                                                                                
                                                                                
                                                                                
                                                                
BR Coef=-1 , 0 , 0 ,, 0 ,,,0.8,0,0.3,0,
WSPro=,,,, 1 ,,,, 0 ,,,, 0 ,,,,-1 ,-1 ,-1 , 0 , 0 , 0 , 0 , 0
Culvert=2,4,12,544,0.013,0.5,1,8,1,990.5,-5,987.01,2,Culvert #1  , 0 ,7.5
Culvert Bottom n=0.013
BR D #Sta/Elev= 126
-224.344 1010.46-219.423    1010-217.487 1009.84-209.908 1009.23-195.472    1008
-174.836    1006-167.093 1005.06-157.972    1004-150.722    1004-146.063 1003.71
-145.177 1003.71 -121.03 1002.84-119.094 1002.85 -86.352 1002.24 -82.612  1002.1
  -79.79    1002 -64.862  1000.5 -59.383    1000 -56.234   999.2 -52.165  998.06
 -52.034  998.02 -51.936     998 -39.797  997.11 -34.974  996.74 -32.448  996.54
 -29.364  996.31 -27.264  996.14 -25.492     996 -22.146  994.98  -8.858  990.36
  -5.052  989.05  -4.462  988.84      -4  987.01  -2.165  986.73   4.003  986.68
   5.052  986.69       8  987.01      10  988.99  19.029  992.45  20.997  994.21
  21.129  994.21  21.686  994.23  21.752  994.24  21.818  994.24   22.31  994.27
  23.688  994.29  24.311  994.34  24.902  994.39  25.131   994.4  25.689  994.41
  25.984  994.42  27.034  994.47  27.165  994.48  27.953  994.55  28.084  994.55
  28.248  994.56   28.97  994.62  29.626  994.68  30.217  994.74  32.054  994.92
  47.999  995.58  48.589  995.61  48.753  995.63  49.081  995.65  55.906     996
  57.448     996  61.417  996.19  63.189  996.28  63.484   996.3  66.765  996.47
  66.995  996.48  68.406  996.56  68.668  996.57   69.98  996.64  70.308  996.66
  78.248  997.09  78.609  997.11  78.871  997.12  79.134  997.14  81.463  997.24
  81.693  997.26   81.89  997.27  83.366  997.33   83.76  997.35  85.302  997.42
  85.531  997.43  85.827  997.45  87.697  997.52  87.927  997.54  88.123  997.55
  95.407   997.8  99.377     998 108.136     998 113.156  998.05 120.112  998.09
 139.567  998.16  161.45  998.09 169.882     998 192.421     998 215.157  998.55
 215.223  998.58 215.322   998.6 215.518  998.66 215.781  998.72 216.043   998.8
 216.371  998.88 216.568  998.94 216.798  998.99 217.815  999.28 217.913   999.3
 217.979  999.32 218.438  999.44 232.218 1001.61 233.727 1001.92 234.383    1002
 235.827  1002.1 236.352 1002.13 236.417 1002.14 236.483 1002.14 236.549 1002.15
 236.614 1002.15 238.255 1002.25 265.223    1004  290.42  1004.7 292.224 1004.73
 336.024 1005.79
BR D #Mann= 5
-224.344     .12-146.063     .06 -22.146     .13  -4.462    .035      10     .13
BC Design=,, 0 ,, 0 ,,,,,,
BC Use User HTab Curves=0
BC User HTab FreeFlow(D)= 0

Type RM Length L Ch R = 1 ,7085.672,198.5,199.412,195.539
BEGIN DESCRIPTION:
POP_07 - Patteson Drive - DS
END DESCRIPTION:
XS GIS Cut Line= 4
587949.0360904434389347.99892781587959.9540265784389412.76588061
587966.0134506534389457.60196117587943.7721943784389513.19748185
#Sta/Elev= 30
-224.344 1010.46-195.472    1008-174.836    1006-157.972    1004-150.722    1004
-146.063 1003.71 -121.03 1002.84 -86.352 1002.24  -79.79    1002 -59.383    1000
 -51.936     998 -25.492     996 -22.146  994.98  -8.858  990.36  -4.462  988.84
  -2.165  986.73   4.003  986.68      10  988.99  19.029  992.45  20.997  994.21
  27.034  994.47  32.054  994.92  99.377     998 139.567  998.16 192.421     998
 215.157  998.55 218.438  999.44 234.383    1002 265.223    1004 336.024 1005.79
#Mann= 5 ,-1 , 0
-224.344     .12       0-146.063     .06       0 -22.146     .13       0
  -8.858     .04       0      10     .13       0
Bank Sta=-8.858,10
XS Rating Curve= 0 ,0
Minor Loss Coefficient=0.5
Exp/Cntr=0.5,0.3

Type RM Length L Ch R = 1 ,6886.601,105.746,98.231,95.657
BEGIN DESCRIPTION:
POP_06 - Laurel Street - US
END DESCRIPTION:
XS GIS Cut Line= 5
587911.2805139774389345.42031978587898.1466818144389394.68514439
587901.447665855 4389428.1247528587914.4443380164389461.91488122
587928.1115701854389494.94605763
#Sta/Elev= 30
-277.526 1011.96-250.164 1008.79-234.219 1008.36-224.377 1008.14-199.081 1008.37
-173.031  1007.6-155.249    1006-147.507    1004-125.951    1002-100.131  1000.6
 -92.323  999.84 -88.878  998.94 -51.903  996.38  -24.18  995.01    -9.9  987.65
  -5.249  985.28       0  985.61    4.56  985.47   5.938  985.76    8.83  987.63
  14.797  991.18  53.543  992.49  87.828  996.04  88.648  996.92 102.789     998
 149.902    1000 155.906    1000 178.248  1001.5 196.982    1002 236.056 1003.97
#Mann= 5 ,-1 , 0
-277.526     .12       0-234.219     .06       0  -24.18     .13       0
    -9.9     .04       0    8.83     .13       0
#XS Ineff= 2 , 0
       0     -35    1005      35       0    1005
Permanent Ineff=
       F       F
Bank Sta=-9.9,8.83
XS Rating Curve= 0 ,0
Exp/Cntr=0.5,0.3

Type RM Length L Ch R = 3 ,6844.22 ,,,
BEGIN DESCRIPTION:
POP_06 - Laurel Street
END DESCRIPTION:
Bridge Culvert--1,0,-1,-1, 0
Deck Dist Width WeirC Skew NumUp NumDn MinLoCord MaxHiCord MaxSubmerge Is_Ogee
27,28,2.6,0, 64, 64, , , 0.98, 0, 0,0,,
-289.534-284.416 -282.94-282.218-280.381-279.823-279.692-279.528-276.903-276.083
-271.194-268.635 -267.06 -266.01-262.828-257.054-255.052-247.933-247.802-244.751
-244.587-244.423-228.904-227.657-226.542-225.558-224.803-224.213-223.786-222.474
-211.253-210.203-208.694-206.824-206.594-205.184-204.134 -202.92-202.297-197.343
-151.936-107.087 -54.921 -16.306     -12   -11.9  -10.77   -8.67   -5.07   -1.49
       0    1.49    5.07    8.67   10.77    11.9      12    12.7  66.076  72.703
 113.058 162.106 214.272 234.908
    1012  1010.9 1010.58 1010.43    1010    1010    1010    1010    1010    1010
    1010    1010    1010    1010    1010    1010    1010 1009.81 1009.81  1009.8
  1009.8  1009.8 1009.72 1009.71  1009.7 1009.69 1009.68 1009.67 1009.67 1009.64
 1009.16 1009.12 1009.06 1008.99 1008.98 1008.93 1008.89 1008.84 1008.82 1008.42
 1004.76 1000.23  995.91  994.96  994.85  996.56  996.55  996.54  996.53  996.53
  996.53  996.53  996.52  996.51   996.5  996.48 994.772  994.77   996.4  996.74
  998.78   999.6 1001.85 1003.32
                                                                                
                                                                                
                                                                                
                                                                                
                                           987.5  989.38  990.31  991.11  991.42
  991.45  991.42  991.11  990.31  989.38   987.5
                                
-289.534-284.416 -282.94-282.218-280.381-279.823-279.692-279.528-276.903-276.083
-271.194-268.635 -267.06 -266.01-262.828-257.054-255.052-247.933-247.802-244.751
-244.587-244.423-228.904-227.657-226.542-225.558-224.803-224.213-223.786-222.474
-211.253-210.203-208.694-206.824-206.594-205.184-204.134 -202.92-202.297-197.343
-151.936-107.087 -54.921 -16.306     -12   -11.9  -10.77   -8.67   -5.07   -1.49
       0    1.49    5.07    8.67   10.77    11.9      12    12.7  66.076  72.703
 113.058 162.106 214.272 234.908
    1012  1010.9 1010.58 1010.43    1010    1010    1010    1010    1010    1010
    1010    1010    1010    1010    1010    1010    1010 1009.81 1009.81  1009.8
  1009.8  1009.8 1009.72 1009.71  1009.7 1009.69 1009.68 1009.67 1009.67 1009.64
 1009.16 1009.12 1009.06 1008.99 1008.98 1008.93 1008.89 1008.84 1008.82 1008.42
 1004.76 1000.23  995.91  994.96  994.85  996.56  996.55  996.54  996.53  996.53
  996.53  996.53  996.52  996.51   996.5  996.48 994.772  994.77   996.4  996.74
  998.78   999.6 1001.85 1003.32
                                                                                
                                                                                
                                                                                
                                                                                
                                           987.5  989.38  990.31  991.11  991.42
  991.45  991.42  991.11  990.31  989.38   987.5
                                
BR Coef=-1 , 1 , 0 ,, 0 ,,,0.8,-1,0.3,0,
WSPro=,,,, 1 ,,,, 0 ,,,, 0 ,,,,-1 ,-1 ,-1 , 0 , 0 , 0 , 0 , 0
BC Design=,, 0 ,, 0 ,,,,,,
BC Use User HTab Curves=0
BC User HTab FreeFlow(D)= 0