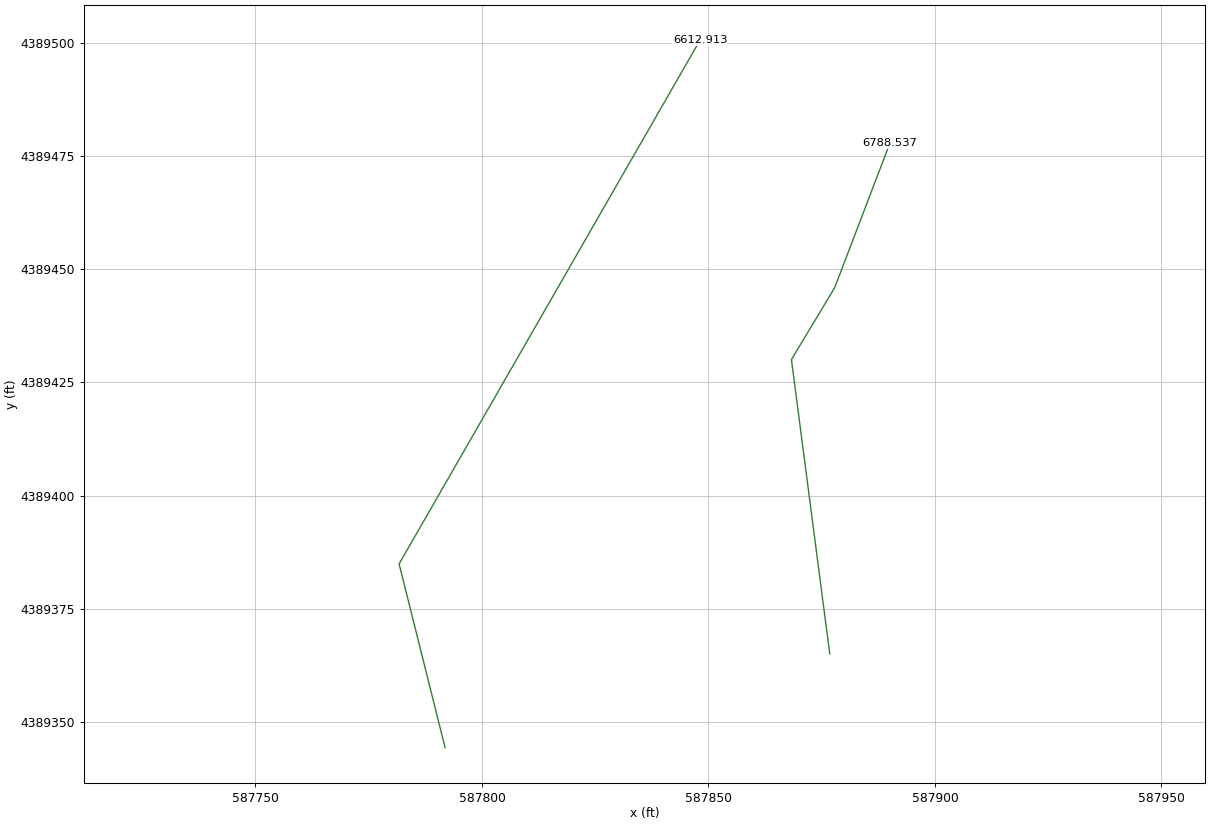
HEC-RAS study Pompono_Run_Detail_Study.prj: Pompono_Run_Detail_Study

--- Pompono_Run_Detail_Study.g01 (geometry) --- (continued)

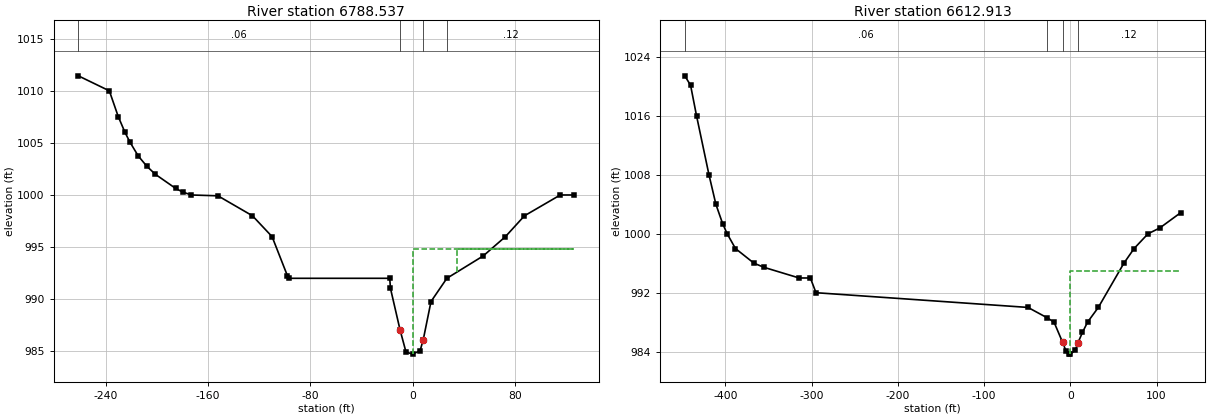
Type RM Length L Ch R = 1 ,6788.537,175.838,175.922,175.677
BEGIN DESCRIPTION:
POP_06 - Laurel Street - DS
END DESCRIPTION:
XS GIS Cut Line= 4
587876.7923935514389365.06163202587868.3280974464389430.04194483
587877.8805295644389445.91897702587890.0572897144389477.78886542
#Sta/Elev= 30
-261.483 1011.44-237.238    1010-230.282 1007.53-224.967    1006-221.096 1005.07
-214.665 1003.75-208.071 1002.78-201.411    1002-185.499 1000.64-179.823 1000.28
-173.097    1000-152.297  999.92-125.295     998-109.974     996 -98.031  992.26
 -96.555     992 -17.979     992 -17.388  991.03   -9.91  987.05  -5.282  984.93
   -.033  984.72   5.807  985.06    8.26  986.12  14.304  989.77  26.706     992
  55.151  994.15  72.507     996  87.369     998 115.387    1000 126.247    1000
#Mann= 4 ,-1 , 0
-261.483     .06       0   -9.91     .04       0    8.26     .12       0
  26.706     .12       0
#XS Ineff= 2 , 0
       0     -35  994.77      35       0  994.77
Permanent Ineff=
       F       F
Bank Sta=-9.91,8.26
XS Rating Curve= 0 ,0
Exp/Cntr=0.5,0.3

Type RM Length L Ch R = 1 ,6612.913,296.865,313.69,329.934
Node Name=R
XS GIS Cut Line= 3
587791.8598725014389344.37485577587781.7100323754389384.91630427
587848.168625197 4389500.6031457
#Sta/Elev= 30
-446.949 1021.45-440.256 1020.17-433.301    1016-418.898    1008-410.892    1004
-403.084 1001.38-397.802    1000-388.222     998-366.699     996-354.692  995.43
-314.403     994-301.378     994-294.849     992 -49.049     990 -26.936   988.6
 -18.865     988   -8.86  985.24   -5.06   984.1   -1.79  983.66    -.02  983.66
    5.68  984.17    8.91  985.21  14.075  986.61   19.98     988  32.448     990
  62.073     996   73.95     998  90.059    1000 103.707 1000.79 127.887 1002.86
#Mann= 4 ,-1 , 0
-446.949     .06       0 -26.936     .12       0   -8.86     .04       0
    8.91     .12       0
#XS Ineff= 2 , 0
       0     -80     995               0
Permanent Ineff=
       F       F
Bank Sta=-8.86,8.91
XS Rating Curve= 0 ,0
Exp/Cntr=0.3,0.1