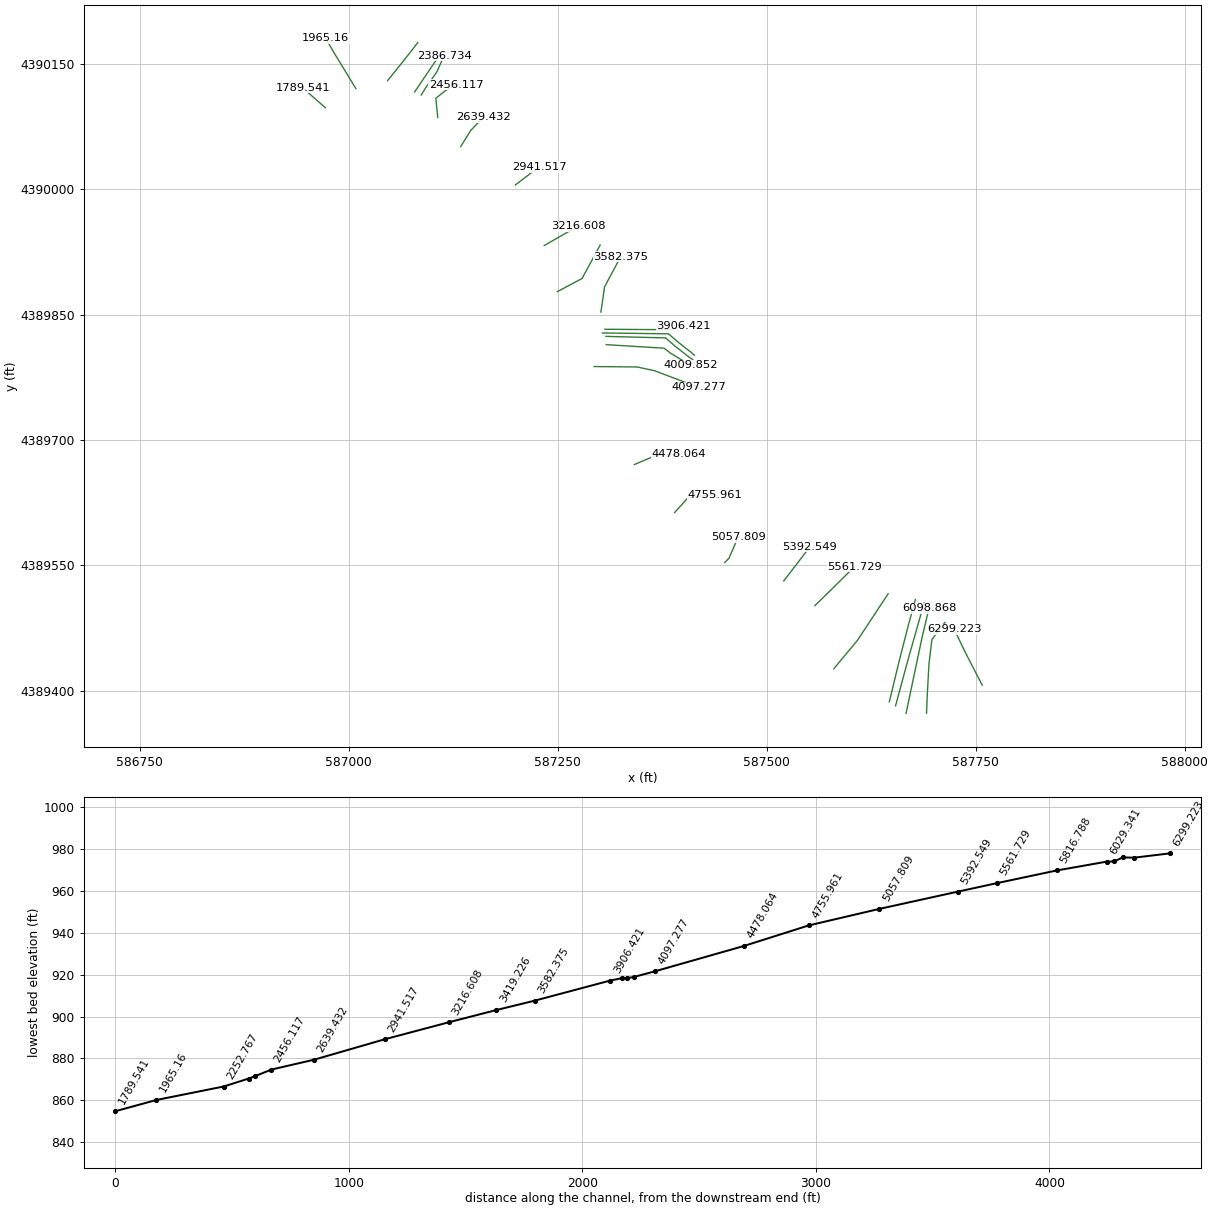
HEC-RAS study Pompono_Run_Detail_Study.prj: Pompono_Run_Detail_Study

--- Pompono_Run_Detail_Study.g01 (geometry) --- (continued)

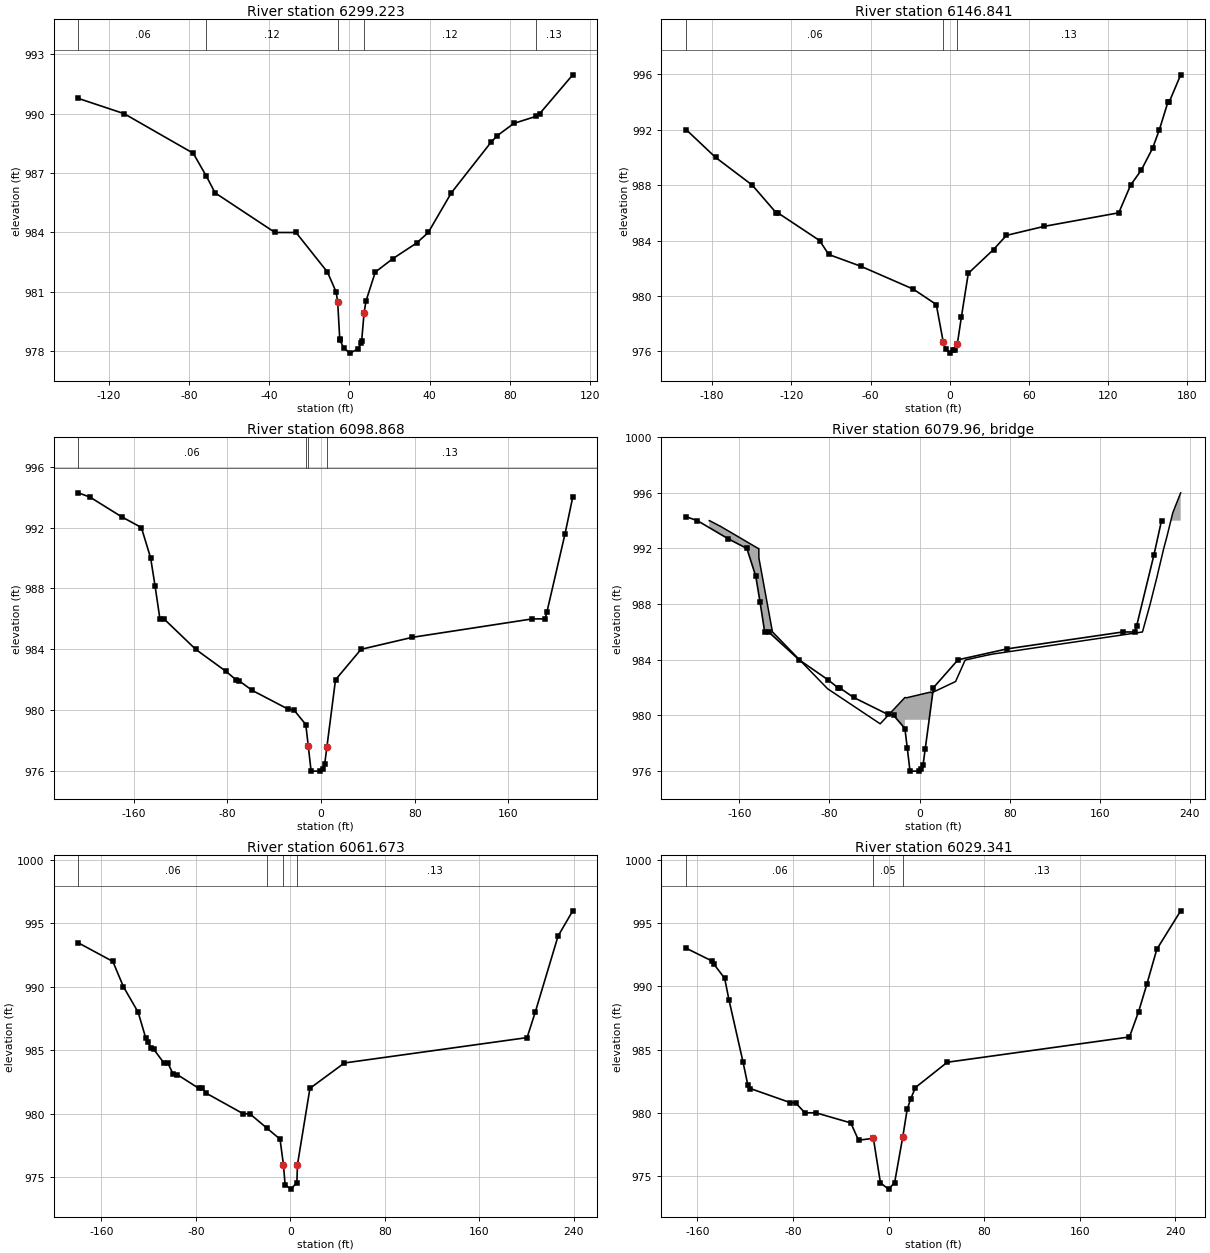
Type RM Length L Ch R = 1 ,6299.223,161.757,152.641,143.124
Node Name=Q
XS GIS Cut Line= 3
587757.9173440814389406.59368054587739.0045038484389443.18187299
587724.1607436644389473.68930537
#Sta/Elev= 30
-135.138  990.77-112.303     990 -77.822     988 -71.227  986.83 -66.929     986
 -37.073     984 -26.608     984 -10.925     982  -6.627     981   -5.84   980.5
   -4.82  978.63   -4.69  978.56   -2.81  978.17     .29  977.91    4.41  978.13
    5.75  978.41    6.12  978.54    7.31  979.93   8.268  980.54  12.894     982
  21.654  982.68   33.53  983.47  39.304     984  50.787     986  70.538  988.55
   73.72  988.89  81.988  989.51  92.946  989.86  94.849     990 111.319  991.96
#Mann= 5 ,-1 , 0
-135.138     .06       0 -71.227     .12       0   -5.84     .04       0
    7.31     .12       0  92.946     .13       0
Bank Sta=-5.84,7.31
XS Rating Curve= 0 ,0
Exp/Cntr=0.3,0.1

Type RM Length L Ch R = 1 ,6146.841,50.314,48.056,46.68
Node Name=P
XS GIS Cut Line= 5
587691.2880632584389373.03215212587692.0317752674389392.36561636
587694.2110952944389432.33708886587697.7498233384389461.25651321
 587713.303767534389481.63239346
#Sta/Elev= 29
-199.606     992-177.395     990-149.606     988-131.463     986-130.249     986
 -98.622     984 -91.667  982.99 -67.323  982.14 -27.657  980.49 -10.203  979.38
  -4.921  976.66  -2.986  976.16       0  975.87   2.723  976.07   4.035  976.08
   5.709  976.51    8.77  978.46  14.042  981.63  33.169  983.35  42.913  984.37
  71.457  985.02 128.018     986 136.975     988 145.046  989.08 153.576  990.65
  158.76     992 165.256     994 166.207     994 174.902  995.96
#Mann= 3 , 0 , 0
-199.606     .06       0  -4.921     .04       0   5.709     .13       0
Bank Sta=-4.921,5.709
XS Rating Curve= 0 ,0
Exp/Cntr=0.5,0.3

Type RM Length L Ch R = 1 ,6098.868,38.132,37.258,36.305
BEGIN DESCRIPTION:
POP_05 - Foot Bridge at Krepps Park - US
END DESCRIPTION:
XS GIS Cut Line= 4
587666.7516629554389372.86451212587670.1257989964389388.74154432
587686.0028311934389464.11248925587694.2202392944389498.53050567
#Sta/Elev= 30
-207.185  994.28-197.211     994-170.243  992.71-153.314     992-145.407     990
-141.601  988.14  -137.5     986-134.022     986-106.955     984 -81.398  982.57
 -72.539     982 -70.276  981.95 -58.629   981.3 -28.018  980.07 -22.933     980
 -12.992  979.06  -10.86  977.64  -8.465     976   -.755     976    1.28  976.17
   3.117  976.45   5.052   977.6  12.369     982  34.154     984  78.051  984.79
 180.446     986  191.24     986 192.717  986.42 208.169  991.55 214.862     994
#Mann= 4 ,-1 , 0
-207.185     .06       0 -12.992     .12       0  -10.86     .04       0
   5.052     .13       0
Bank Sta=-10.86,5.052
XS Rating Curve= 0 ,0
Exp/Cntr=0.5,0.3

Type RM Length L Ch R = 3 ,6079.96 ,,,
BEGIN DESCRIPTION:
POP_05 - Foot Bridge at Krepps Park
END DESCRIPTION:
Bridge Culvert--1,0,-1,-1, 0
Deck Dist Width WeirC Skew NumUp NumDn MinLoCord MaxHiCord MaxSubmerge Is_Ogee
18,8,2.6,0, 58, 58, , , 0.98, 0, 0,0,,
 -186.68 -186.45-179.593-177.559-177.329-143.241-143.209-143.176-143.143 -143.11
-143.077-143.045-143.012-142.913-142.881-142.717-142.618 -130.61  -81.66 -34.941
     -13 -11.122   -10.6     8.2  10.171    10.6  32.021  40.223  41.207   41.24
  41.273  46.982   49.77      50  52.657  52.822  55.381  55.577  58.038  60.696
  60.958  61.253  64.731 194.619 197.933 198.294 198.392 198.655 199.541 204.757
 208.924 210.991 211.778 216.831 219.587  224.77 227.264  231.89
     994     994  993.71  993.62  993.62     992     992     992     992     992
     992     992     992     992     992     992  991.31  986.01  981.92   979.4
  981.29  981.27  981.29  981.65  981.68  981.62  982.44  983.93     984     984
     984   984.1  984.15  984.16   984.2  984.21  984.25  984.25   984.3  984.34
  984.35  984.35  984.41  985.96     986   986.1  986.13  986.21  986.47     988
  989.34     990  990.28     992  992.83  994.54  995.06     996
                                                                                
                                                                                
  979.69  979.69  979.69  979.69
                                                                                
                                                                                
                                                                
 -186.68 -186.45-179.593-177.559-177.329-143.241-143.209-143.176-143.143 -143.11
-143.077-143.045-143.012-142.913-142.881-142.717-142.618 -130.61  -81.66 -34.941
 -11.352 -11.122   -10.6  10.105  10.171    10.6  32.021  40.223  41.207   41.24
  41.273  46.982   49.77      50  52.657  52.822  55.381  55.577  58.038  60.696
  60.958  61.253  64.731 194.619 197.933 198.294 198.392 198.655 199.541 204.757
 208.924 210.991 211.778 216.831 219.587  224.77 227.264  231.89
     994     994  993.71  993.62  993.62     992     992     992     992     992
     992     992     992     992     992     992  991.31  986.01  981.92   979.4
  981.29  981.27  981.29  981.65  981.68  981.62  982.44  983.93     984     984
     984   984.1  984.15  984.16   984.2  984.21  984.25  984.25   984.3  984.34
  984.35  984.35  984.41  985.96     986   986.1  986.13  986.21  986.47     988
  989.34     990  990.28     992  992.83  994.54  995.06     996
                                                                                
                                                                                
                  980.05  980.02  980.02  980.02
                                                                                
                                                                                
                                                                
BR Coef=-1 , 0 , 0 ,, 0 ,,,0.8,0,1.2,0,
WSPro=,,,, 1 ,,,, 0 ,,,, 0 ,,,,-1 ,-1 ,-1 , 0 , 0 , 0 , 0 , 0
BC Design=,, 0 ,, 0 ,,,,,,
BC Use User HTab Curves=0
BC User HTab FreeFlow(D)= 0

Type RM Length L Ch R = 1 ,6061.673,31.936,32.386,32.668
BEGIN DESCRIPTION:
POP_05 - Foot Bridge at Krepps Park - DS
END DESCRIPTION:
XS GIS Cut Line= 3
  587654.25181484389382.03899223587669.3089349864389437.67718492
587688.3619832224389504.99226575
#Sta/Elev= 30
-179.528  993.47-150.262     992 -141.24     990-128.839     988-122.507     986
-120.801  985.66-117.684  985.17-115.551  985.07-107.021     984 -103.74     984
 -99.049   983.1 -95.604  983.08 -77.493     982 -74.442     982 -71.227  981.62
 -39.862     980 -34.318     980 -20.144  978.89  -8.727     978   -5.84     976
  -4.421  974.41      .5  974.06   5.552  974.58    6.07     976  16.601     982
  45.768     984 200.459     986 207.349     988 226.673     994 239.108  995.99
#Mann= 4 ,-1 , 0
-179.528     .06       0 -20.144     .12       0   -5.84     .05       0
    6.07     .13       0
Bank Sta=-5.84,6.07
XS Rating Curve= 0 ,0
Exp/Cntr=0.5,0.3

Type RM Length L Ch R = 1 ,6029.341,220.967,212.914,205.108
Node Name=O
XS GIS Cut Line= 4
587646.7903107084389386.80301629587658.9091588584389436.99748091
587669.8088069924389479.35248944587677.904295093 4389509.0643938
#Sta/Elev= 28
-169.423  993.02-147.638     992-146.227  991.76-137.238  990.64-133.563  988.91
-121.818     984-117.815  982.18-115.781  981.92 -82.448  980.81 -77.822  980.79
 -70.112     980 -60.892     980  -31.66   979.2 -25.164  977.83  -12.73  977.98
  -6.824  974.45       0  973.96   5.052  974.48   11.85  978.09  15.551  980.27
  18.373  981.07  22.474     982  49.147     984  201.64     986 209.285     988
 216.207  990.18 224.541  992.94 244.521  995.98
#Mann= 3 ,-1 , 0
-169.423     .06       0  -12.73     .05       0   11.85     .13       0
Bank Sta=-12.73,11.85
XS Rating Curve= 0 ,0
Exp/Cntr=0.3,0.1

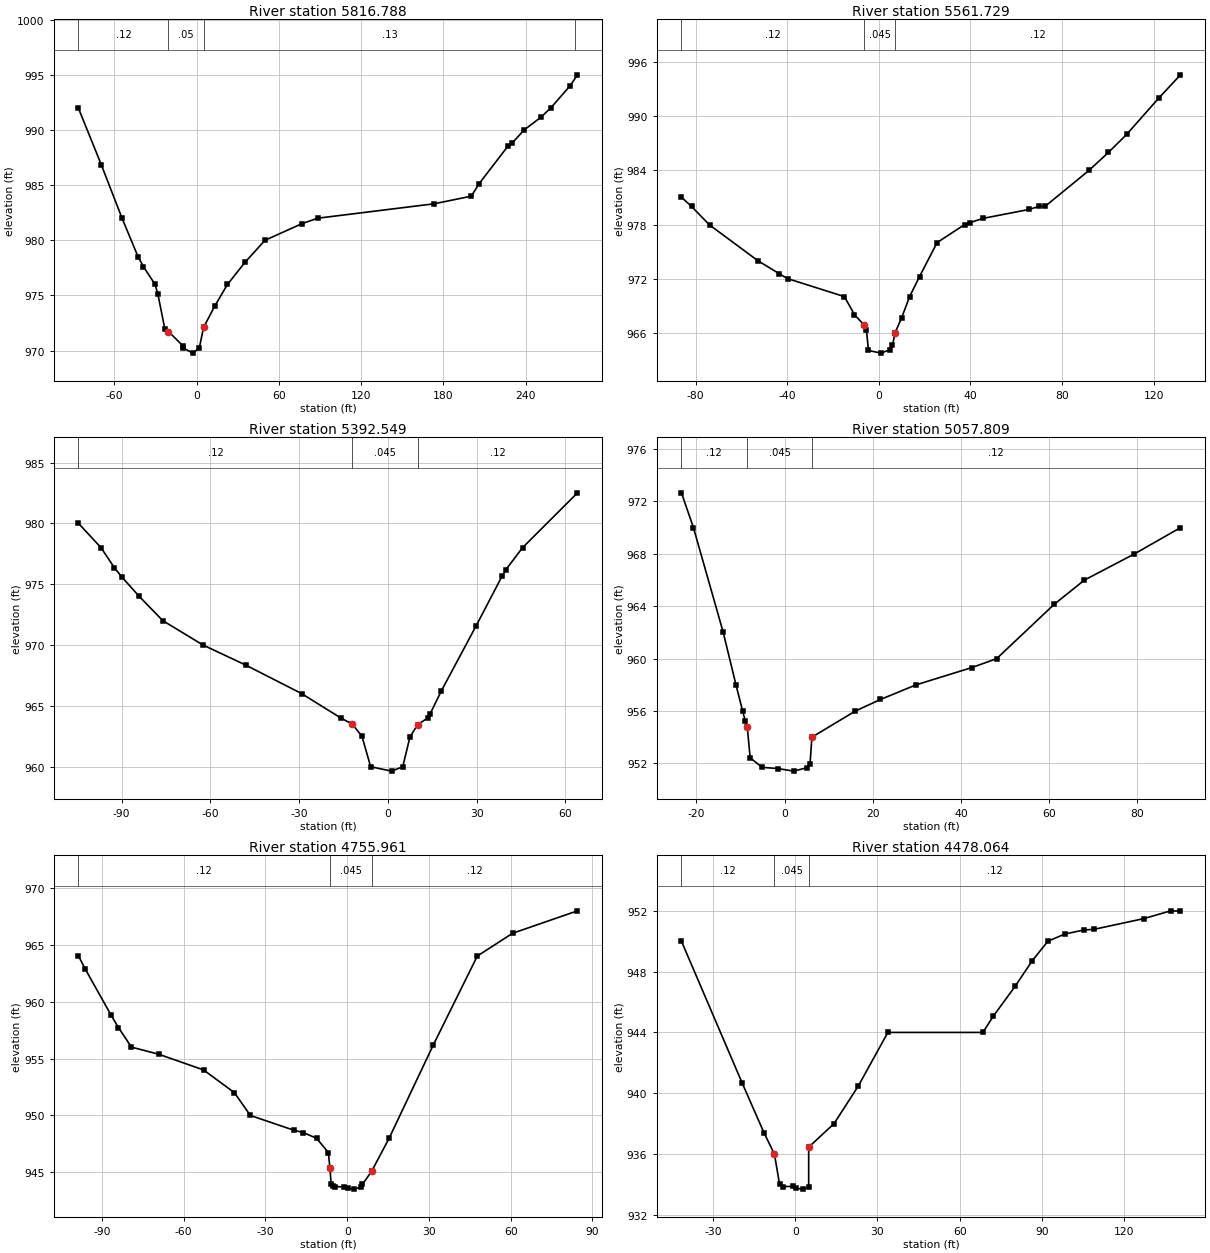
Type RM Length L Ch R = 1 ,5816.788,257.351,255.493,253.635
Node Name=N
XS GIS Cut Line= 3
587580.4018218874389426.31119278587608.614110236 4389460.2293372
587645.3943266914389515.96811389
#Sta/Elev= 30
 -86.056  991.96 -69.488  986.87 -54.298     982 -42.552  978.49 -38.747  977.62
 -30.217     976  -28.15  975.11 -23.163     972  -20.45  971.73   -9.92  970.43
    -9.5  970.22    -2.6  969.77    2.04  970.24   5.151   972.1  13.222  974.02
  22.572     976  35.335     978  49.934     980  76.739   981.5  88.287     982
  173.36  983.31 200.361     984 206.037  985.13 227.165  988.55 230.348  988.84
 238.878     990  251.05  991.15 258.301     992 272.343     994 277.789     995
#Mann= 4 ,-1 , 0
 -86.056     .12       0  -20.45     .05       0   5.151     .13       0
 276.247     .12       0
Bank Sta=-20.45,5.151
XS Rating Curve= 0 ,0
Exp/Cntr=0.3,0.1

Type RM Length L Ch R = 1 ,5561.729,167.168,169.468,171.786
Node Name=M
XS GIS Cut Line= 2
587557.7612776084389501.75833771587605.1271981934389548.31958629
#Sta/Elev= 30
  -86.22  981.03 -81.791     980  -73.95  977.95  -52.92     974  -43.57  972.55
 -39.895     972 -15.059     970 -10.663     968   -6.45  966.84   -5.44  966.31
   -4.56  964.03      .9  963.73    5.02  964.13    5.92  964.59   7.087     966
   9.941  967.67  13.419     970  17.749  972.23  25.427     976  37.467     978
  39.862  978.22  45.472  978.68  65.518  979.67  69.783     980  72.507     980
  91.732     984  100.23     986 108.202     988 122.113     992 131.693  994.61
#Mann= 3 , 0 , 0
  -86.22     .12       0   -6.45    .045       0   7.087     .12       0
Bank Sta=-6.45,7.087
XS Rating Curve= 0 ,0
Exp/Cntr=0.3,0.1

Type RM Length L Ch R = 1 ,5392.549,336.54,334.74,338.785
Node Name=L
XS GIS Cut Line= 2
587520.4720451474389531.32393808587551.7871975344389572.09093858
#Sta/Elev= 25
-104.593     980 -96.982     978 -92.487  976.36 -89.993   975.6 -84.088     974
 -76.115     972 -62.566     970  -48.13  968.35 -29.199     966 -15.978     964
  -12.05  963.48    -8.8   962.5   -5.84  959.98    1.22  959.62    5.01  959.98
    7.44  962.43   10.03  963.44  13.484     964  14.239  964.32  18.012   966.2
  29.856  971.59  38.583  975.66  39.895   976.2  45.505     978  64.075  982.51
#Mann= 3 , 0 , 0
-104.593     .12       0  -12.05    .045       0   10.03     .12       0
Bank Sta=-12.05,10.03
XS Rating Curve= 0 ,0
Exp/Cntr=0.3,0.1

Type RM Length L Ch R = 1 ,5057.809,313.601,301.848,284.23
Node Name=K
XS GIS Cut Line= 3
587449.8864602744389553.27868235587454.9430923374389558.59744241
587465.8457884724389583.48436272
#Sta/Elev= 23
 -23.392  972.66 -20.669     970 -13.911     962 -11.024     958  -9.514     956
  -8.924  955.26  -8.465  954.78    -7.8  952.43   -5.12   951.7    -1.6  951.61
    2.07  951.41    5.19  951.68    5.79  951.99   6.201     954  16.076     956
  21.752  956.88  29.856     958   42.52  959.32   48.13     960  61.188  964.15
  68.045     966  79.298  967.98  89.829     970
#Mann= 3 , 0 , 0
 -23.392     .12       0  -8.465    .045       0   6.201     .12       0
Bank Sta=-8.465,6.201
XS Rating Curve= 0 ,0
Exp/Cntr=0.3,0.1

Type RM Length L Ch R = 1 ,4755.961,272.31,278.368,284.427
Node Name=J
XS GIS Cut Line= 3
587389.8682915334389613.08958709587406.0501237334389630.97220331
587437.5573001224389634.68466736
#Sta/Elev= 28
 -98.655     964 -96.096  962.82 -86.647  958.79  -83.99  957.72 -79.199     956
 -69.259  955.38 -52.756     954 -41.404     952 -35.564     950 -19.554   948.7
 -16.175   948.5 -11.253     948  -6.923  946.74   -6.34  945.37   -5.92  944.02
    -5.1  943.84   -4.66  943.76   -1.09  943.72     .11   943.6    2.64  943.53
    5.17  943.72     5.6  943.95    9.02  945.12  15.387     948  31.529  956.15
  47.769     964  60.728     966  84.547  967.97
#Mann= 3 ,-1 , 0
 -98.655     .12       0   -6.34    .045       0    9.02     .12       0
Bank Sta=-6.34,9.02
XS Rating Curve= 0 ,0
Exp/Cntr=0.3,0.1

Type RM Length L Ch R = 1 ,4478.064,393.507,380.787,368.068
Node Name=I
XS GIS Cut Line= 3
587341.807426939 4389670.5779158587368.3158832664389681.81284394
587394.9645475964389682.74857995
#Sta/Elev= 25
  -41.47     950 -19.259  940.64 -11.352  937.39  -7.579     936   -5.71  934.03
   -4.43  933.86    -.81  933.87     .41  933.74    2.97  933.69    4.92  933.81
   4.921  936.45  14.173     938  22.999  940.47  33.793     944  68.438     944
  72.178  945.05  80.217  947.04   86.45  948.72  92.159     950  98.261  950.47
 105.249  950.74 108.924  950.78 127.165  951.49 136.942     952 140.486  951.98
#Mann= 3 ,-1 , 0
  -41.47     .12       0  -7.579    .045       0   4.921     .12       0
Bank Sta=-7.579,4.921
XS Rating Curve= 0 ,0
Exp/Cntr=0.3,0.1

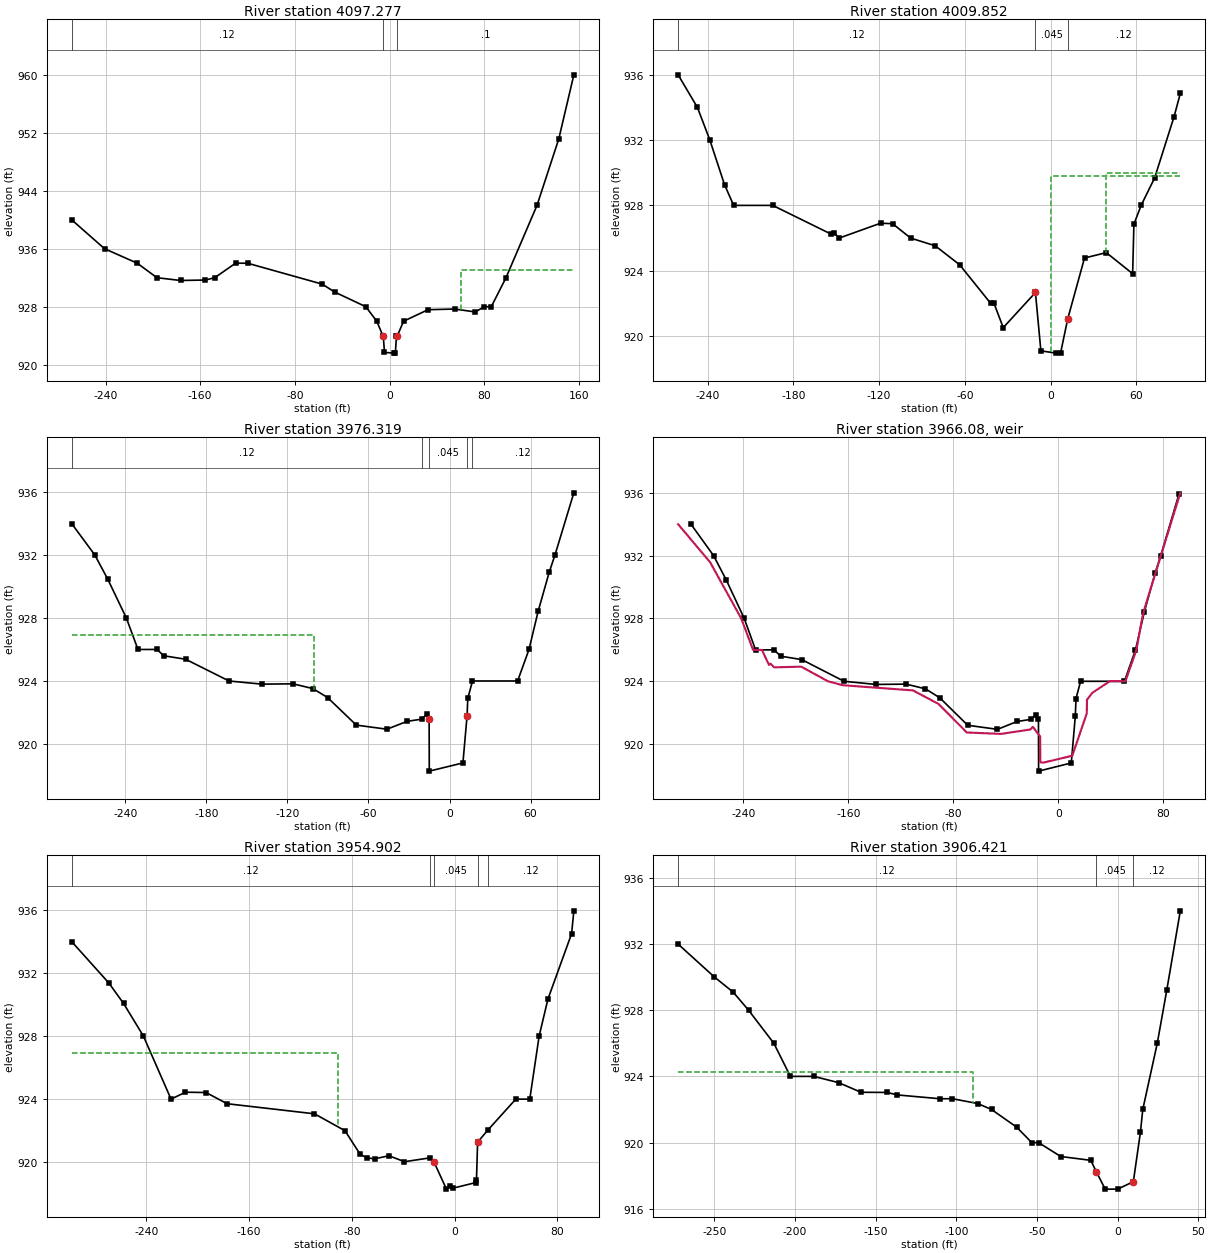
Type RM Length L Ch R = 1 ,4097.277,92.374,87.574,84.471
Node Name=H
XS GIS Cut Line= 4
587293.6795063444389787.81009325587345.3248189824389787.27059724
587365.9292992374389782.79308519587418.8608678914389762.76467694
#Sta/Elev= 30
-268.602  939.99-240.814     936-213.189     934-196.522     932 -176.64  931.62
-155.643  931.68-147.736     932-130.151     934 -119.98     934 -56.988  931.12
 -46.063     930 -20.079     928 -10.827     926  -5.643     924   -5.31  923.91
    -4.3   921.7     3.7   921.6    4.92  921.62    5.79  923.92   6.594     924
  11.811     926  32.513  927.59   55.02  927.68  72.408  927.28   80.02     928
  85.925     928   98.36     932 124.606     942 142.979  951.16 155.676  959.98
#Mann= 3 ,-1 , 0
-268.602     .12       0  -5.643    .045       0   6.594      .1       0
#XS Ineff= 2 , 0
       0                      60       0     933
Permanent Ineff=
       F       F
Bank Sta=-5.643,6.594
XS Rating Curve= 0 ,0
Exp/Cntr=0.3,0.1

Type RM Length L Ch R = 1 ,4009.852,34.772,33.589,31.469
Node Name=G
XS GIS Cut Line= 4
 587307.965482524389814.00460557587377.2038513764389809.77702952
587385.5553714794389803.43718944587408.9579157694389789.39200527
#Sta/Elev= 30
-260.728  935.99-247.244     934-238.517     932-228.248  929.27 -221.85     928
-194.488     928-153.806  926.25-151.772  926.34-147.999     926-119.029  926.91
-110.564  926.88 -97.966     926 -80.807  925.53 -63.681  924.37 -41.864     922
 -39.567     922 -33.136  920.52 -10.597  922.67  -6.791   919.1   3.871  918.96
   6.988  918.96   12.01  921.06  23.753  924.78  39.009  925.11  57.448  923.82
  58.333  926.85  63.386     928  72.835  929.68   86.45  933.43  90.814  934.85
#Mann= 3 , 0 , 0
-260.728     .12       0 -10.597    .045       0   12.01     .12       0
#XS Ineff= 2 , 0
       0 -112.56  929.77   39.01       0     930
Permanent Ineff=
       F       F
Bank Sta=-10.597,12.01
XS Rating Curve= 0 ,0
Exp/Cntr=0.5,0.3

Type RM Length L Ch R = 1 ,3976.319,22.115,21.454,20.515
XS GIS Cut Line= 5
587307.7155465174389823.89231769  587379.13323544389822.06046967
587390.2188115374389812.37697355587406.8517477434389799.32238939
587411.7956038044389795.86900535
#Sta/Elev= 30
-279.757  933.99-262.631     932-253.084  930.47-239.272     928-230.643     926
-216.503     926-211.549   925.6-195.407  925.38-163.222     924-138.911   923.8
-115.912  923.82-101.181  923.52 -90.289  922.95 -68.996   921.2 -46.325  920.94
 -31.398  921.44 -20.407  921.58 -17.028  921.88 -15.092  921.61 -14.961  918.28
   9.941   918.8   12.99  921.77   13.55   922.9  17.028     924  50.427     924
  58.858     926  65.682  928.44  73.852  930.91  78.117     932   92.06  935.94
#Mann= 5 ,-1 , 0
-279.757     .12       0 -20.407     .06       0 -15.092    .045       0
   12.99     .06       0  17.028     .12       0
#XS Ineff= 2 , 0
            -100  926.89
Permanent Ineff=
       F       F
Bank Sta=-15.092,12.99
XS Rating Curve= 0 ,0
Exp/Cntr=0.5,0.3

Type RM Length L Ch R = 5 ,3966.08 ,,,
BEGIN DESCRIPTION:
POP_04
END DESCRIPTION:
IW Pilot Flow=0
#Inline Weir SE= 30
-289.665     934-265.289  931.58-241.568     928-232.546     926-225.787     926
-220.407  925.04-219.455  925.13 -216.47  924.89-195.833  924.93-175.427     924
-164.206  923.75-110.728  923.42 -91.306  922.56 -69.685  920.74 -43.602  920.65
 -21.325  920.93 -19.357   921.1  -13.78  920.48 -13.648  918.84 -10.794  918.83
  10.696  919.26  21.752  921.96  21.916  922.83  26.017  923.27  39.173     924
  51.148     924   59.58     926  63.911     928  66.043  928.71  93.012     936
IW Dist,WD,Coef,Skew,MaxSub,Min_El,Is_Ogee,SpillHt,DesHd
8,3.5,2.6,0,0.98,, 0 ,,,0,0,

Type RM Length L Ch R = 1 ,3954.902,31.251,48.563,65.414
XS GIS Cut Line= 5
587303.6647544674389827.98882974587382.6628194444389826.94336573
587394.0470995844389817.00078961 587409.850979784389804.59542945
587413.6396438274389801.35845342
#Sta/Elev= 30
-298.261     934-269.291  931.37-257.808  930.07-242.356     928-220.866     924
-209.678  924.44 -193.57  924.42-177.231  923.71-109.186  923.07 -85.433     922
 -73.589   920.5 -68.471  920.28 -62.369  920.21 -51.181  920.41 -39.075  920.03
 -19.521  920.27  -16.01     920  -6.398  918.29   -3.74  918.46  -1.345  918.35
  16.699  918.71  16.995  918.87  17.881  921.27  25.984  922.05  47.605     924
  58.497     924  65.781     928  72.638  930.35  91.076   934.5  92.815  935.95
#Mann= 5 ,-1 , 0
-298.261     .12       0 -19.521     .06       0  -16.01    .045       0
  17.881     .06       0  25.984     .12       0
#XS Ineff= 2 , 0
          -90.74  926.95
Permanent Ineff=
       F       F
Bank Sta=-16.01,17.881
XS Rating Curve= 0 ,0
Exp/Cntr=0.5,0.3

Type RM Length L Ch R = 1 ,3906.421,305.043,324.046,343.03
Node Name=F
XS GIS Cut Line= 3
587306.420146501 4389832.4114778587384.3605554654389831.89636579
587400.6277316664389836.53542185
#Sta/Elev= 29
-272.441  931.99-249.934     930-238.222  929.08-228.806     928-213.123     926
-202.854     924 -188.32     924  -172.9  923.62-159.121  923.04-142.913  923.03
-136.614  922.88-110.236  922.65-102.428  922.65 -86.778  922.36 -78.215     922
  -62.73  920.94 -53.248     920 -49.049     920 -35.302  919.16 -16.732  918.93
   -13.2  918.23  -7.776  917.19   -.033  917.19   9.678  917.64  14.108  920.66
  15.518     922  24.508     926  30.446  929.24   38.78     934
#Mann= 3 , 0 , 0
-272.441     .12       0   -13.2    .045       0   9.678     .12       0
#XS Ineff= 2 , 0
          -89.71  924.29
Permanent Ineff=
       F       F
Bank Sta=-13.2,9.678
XS Rating Curve= 0 ,0
Exp/Cntr=0.3,0.1

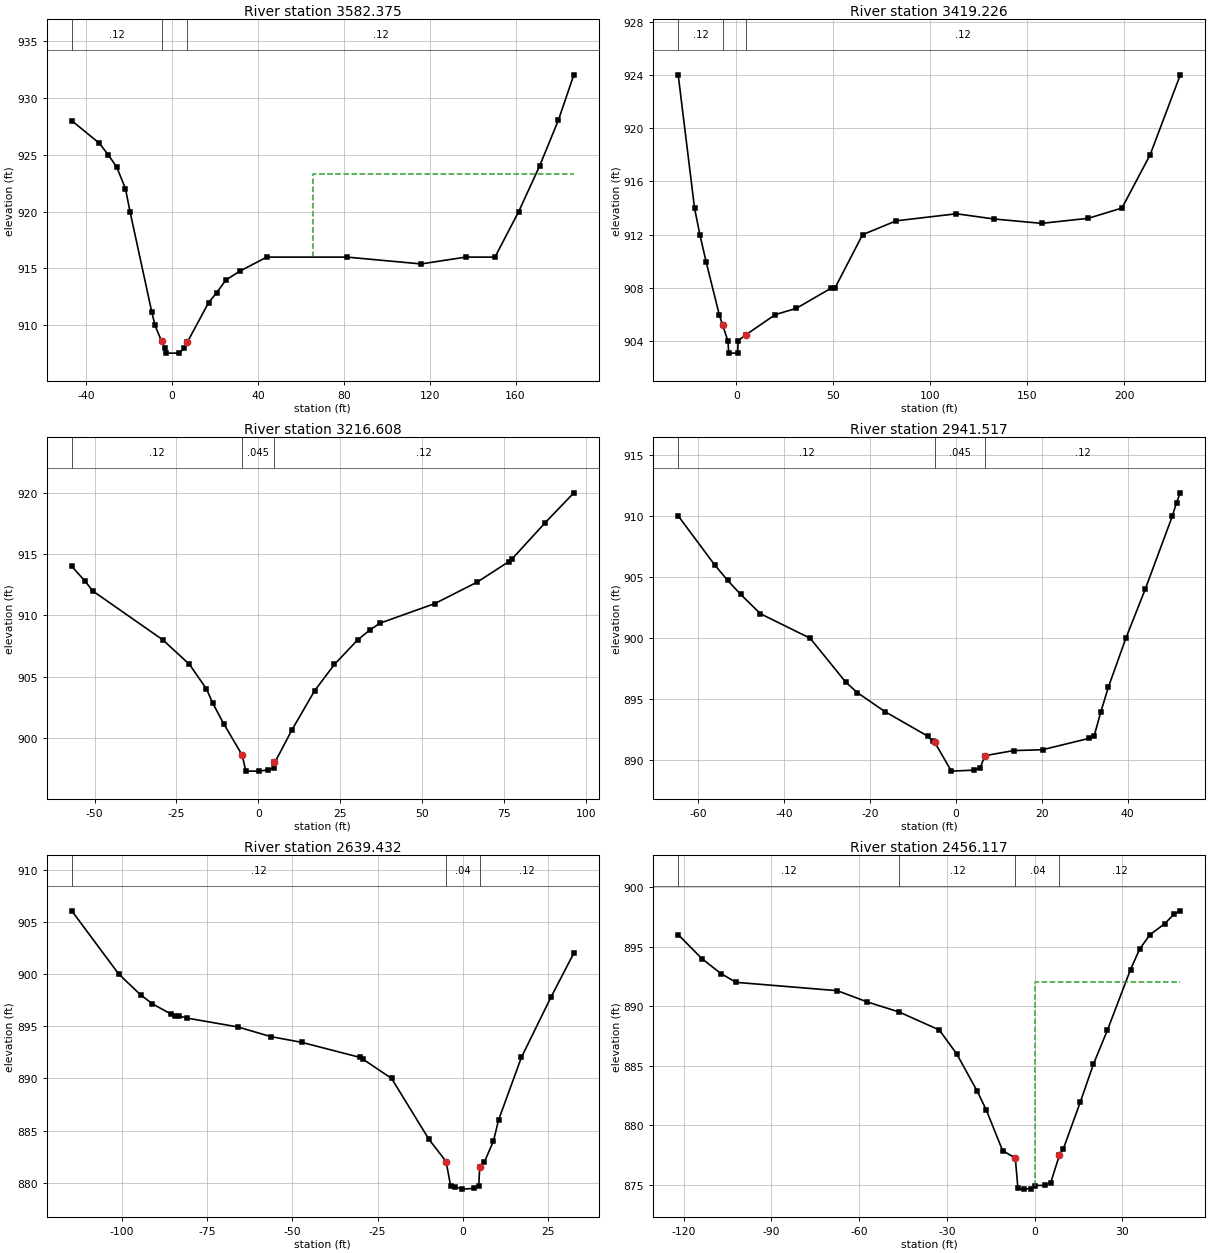
Type RM Length L Ch R = 1 ,3582.375,179.112,163.428,147.745
Node Name=J
XS GIS Cut Line= 3
587301.7262264434389853.00681405587306.0726744974389883.13324643
587325.3360347354389919.18499087
#Sta/Elev= 27
 -46.785  927.97 -33.957     926 -29.757  924.97 -25.853  923.91 -21.752     922
 -19.652     920  -9.547  911.22  -8.005     910  -4.954  908.63  -3.445     908
   -2.84  907.57    3.15  907.57   5.741     908       7  908.51  16.962     912
  20.702  912.87  25.066     914  31.791  914.79  44.062     916  81.398     916
  116.01   915.4 136.778     916 150.426     916 161.483     920 171.227     924
 179.921     928 187.172     932
#Mann= 3 ,-1 , 0
 -46.785     .12       0  -4.954    .045       0       7     .12       0
#XS Ineff= 2 , 0
                            65.6          923.26
Permanent Ineff=
       F       F
Bank Sta=-4.954,7
XS Rating Curve= 0 ,0
Exp/Cntr=0.3,0.1

Type RM Length L Ch R = 1 ,3419.226,202.438,202.961,203.485
Node Name=I
XS GIS Cut Line= 3
587249.6176177994389877.43348636587279.1374981644389893.13068655
587300.7752504324389933.09606304
#Sta/Elev= 24
 -29.888  923.97  -21.49     914 -18.734     912 -15.453  909.93   -8.76     906
  -6.955  905.19  -4.232     904   -3.89  903.11      .7  903.11    1.05  904.05
   4.921  904.48  20.112     906  30.938  906.47  49.081     908  50.919     908
  65.125     912  82.448  913.04 113.517  913.57 132.841  913.18 157.415  912.85
  181.43  913.23 198.819     914 213.353     918 228.904     924
#Mann= 3 , 0 , 0
 -29.888     .12       0  -6.955    .045       0   4.921     .12       0
Bank Sta=-6.955,4.921
XS Rating Curve= 0 ,0
Exp/Cntr=0.3,0.1

Type RM Length L Ch R = 1 ,3216.608,273.454,275.559,277.664
Node Name=H
XS GIS Cut Line= 2
587233.9356576064389932.57180704587274.4832021074389955.85243132
#Sta/Elev= 27
 -56.988     914 -52.854  912.77 -50.623     912 -29.167     908  -21.03     906
 -15.846     904 -13.911  902.83 -10.597  901.17  -4.921  898.59   -3.82  897.29
     .26  897.29    3.06  897.39     4.7  897.55   4.921     898   5.052     898
  10.302  900.67  17.224  903.86  23.261     906  30.348     908   33.99  908.79
  37.139  909.36  53.904  910.96  66.765   912.7  76.509  914.38  77.559  914.62
  87.631  917.56  96.391     920
#Mann= 3 ,-1 , 0
 -56.988     .12       0  -4.921    .045       0   4.921     .12       0
Bank Sta=-4.921,4.921
XS Rating Curve= 0 ,0
Exp/Cntr=0.3,0.1

Type RM Length L Ch R = 1 ,2941.517,299.283,302.085,304.887
Node Name=G
XS GIS Cut Line= 2
587199.3469531784390005.05934393587227.681161528 4390026.6178482
#Sta/Elev= 27
 -64.567     910 -56.102     906 -53.051  904.72 -50.033  903.58  -45.44     902
 -33.891     900 -25.656  896.43 -22.933  895.56 -16.503     894  -6.562     892
  -5.381  891.57  -4.921   891.5   -1.03  889.13    4.18  889.21    5.72  889.41
   6.726  890.39  13.451  890.81  20.177  890.88  31.004  891.81  32.185     892
   33.76     894  35.499     896  39.567     900  44.062     904  50.394     910
  51.345  911.09  52.231  911.89
#Mann= 3 , 0 , 0
 -64.567     .12       0  -4.921    .045       0   6.726     .12       0
Bank Sta=-4.921,6.726
XS Rating Curve= 0 ,0
Exp/Cntr=0.3,0.1

Type RM Length L Ch R = 1 ,2639.432,185.835,183.627,179.515
Node Name=F
XS GIS Cut Line= 3
587133.894200369 4390050.8890725587146.0374325194390070.35055274
587161.1280807064390086.25806494
#Sta/Elev= 28
-114.665  906.05-100.919     900 -94.488     898  -91.01  897.14  -85.63  896.17
 -84.514     896 -83.366     896 -80.971  895.78 -66.043  894.93 -56.299     894
 -47.113  893.44 -30.085     892 -29.331  891.84 -20.932     890  -9.941  884.15
  -4.921  882.03    -3.6  879.67   -2.46  879.64    -.15  879.39    3.22  879.46
    4.63  879.69   4.921  881.48   6.299     882   8.957     884  10.433     886
  17.126     892  25.853  897.81  32.513     902
#Mann= 3 ,-1 , 0
-114.665     .12       0  -4.921     .04       0   4.921     .12       0
Bank Sta=-4.921,4.921
XS Rating Curve= 0 ,0
Exp/Cntr=0.5,0.3

Type RM Length L Ch R = 1 ,2456.117,64.894,69.502,76.013
BEGIN DESCRIPTION:
POP_03 - Chipps Hollow Rd - US
END DESCRIPTION:
XS GIS Cut Line= 5
   587106.529256 4390085.8130569   587104.197536 4390108.7401132
  587115.1764321 4390117.5549293  587121.5406562 4390121.5691454
  587128.3742723 4390125.0133854
#Sta/Elev= 30
-121.818     896 -113.78     894-107.251  892.74-102.067     892 -67.454   891.3
 -57.251  890.36 -46.194   889.5 -32.579     888  -26.64     886 -19.619  882.87
  -16.47  881.26 -10.958  877.89  -6.594  877.25  -5.709  874.71  -3.642  874.65
  -1.345   874.7       0  874.95   3.543  874.97   5.512   875.2   8.497  877.51
   9.777     878  15.682     882  20.112  885.14  24.902     888  32.776  893.07
  35.925   894.8  39.436     896  44.488  896.92  47.802  897.76  49.803     898
#Mann= 4 ,-1 , 0
-121.818     .12       0 -46.194     .12       0  -6.594     .04       0
   8.497     .12       0
#XS Ineff= 2 , 0
       0     -28     892               0
Permanent Ineff=
       F       F
Bank Sta=-6.594,8.497
XS Rating Curve= 0 ,0
Exp/Cntr=0.5,0.3

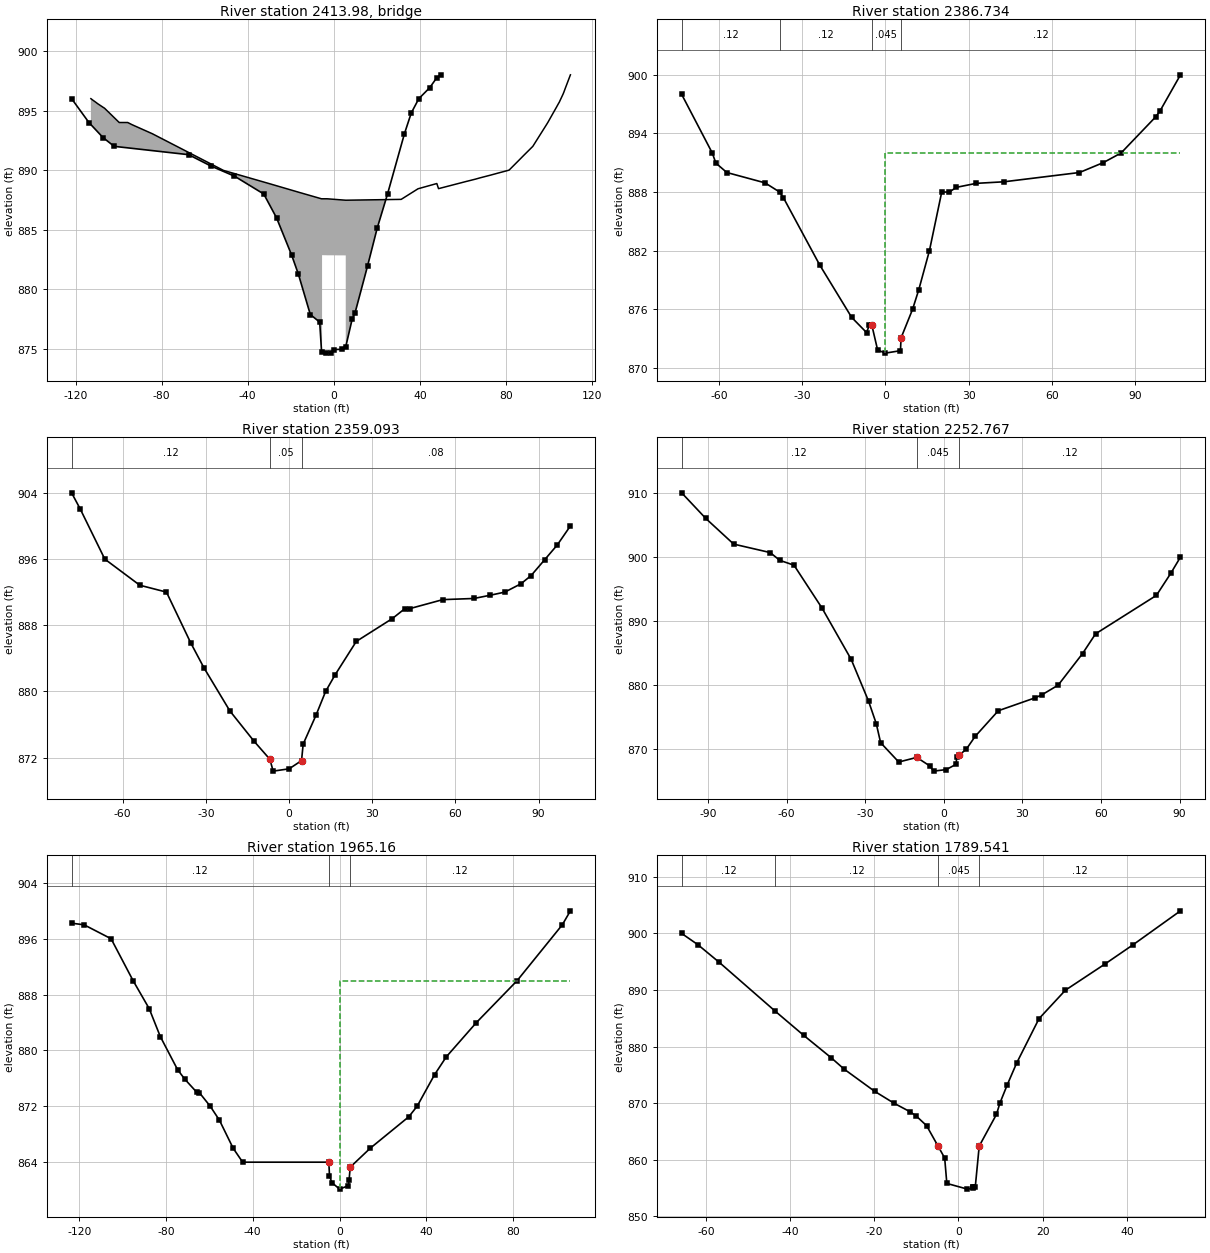
Type RM Length L Ch R = 3 ,2413.98 ,,,
BEGIN DESCRIPTION:
POP_03 - Chipps Hollow Rd
END DESCRIPTION:
Bridge Culvert--1,0,-1,-1, 0
Deck Dist Width WeirC Skew NumUp NumDn MinLoCord MaxHiCord MaxSubmerge Is_Ogee
31,19.4,2.6,0, 61, 61, , , 0.98, 0, 0,0,,
 -112.86-112.073-111.909-111.056-110.302-109.646-109.219-107.972-107.316-106.529
 -99.705 -99.442 -98.983  -98.72 -98.458  -98.36 -97.999 -97.802 -97.408 -97.244
 -96.785 -96.654 -96.161 -96.096 -95.768 -93.668  -84.35  -51.28 -29.593 -15.781
  -5.774    -5.5    -3.2     5.5   5.512  31.234  39.075  47.802  48.589  61.811
  61.844  65.781  67.749  70.079  72.867  76.115  81.299  81.332   85.86  88.156
  92.388   94.16  98.556  99.344 103.379 104.265 104.659 106.496 106.824  107.48
 109.843
     896  895.89  895.87  895.76  895.66  895.57  895.52  895.37  895.29   895.2
     894     894     894     894     894     894     894     894     894     894
     894     894     894     894     894  893.81  893.06  889.98  888.85  888.12
   887.6   887.6   887.6  887.48  887.48  887.55  888.44  888.88  888.45  889.07
  889.07  889.25  889.35  889.46  889.59  889.75     890     890  890.82  891.24
     892  892.51  893.77     894  895.29  895.58   895.7  896.41  896.56  896.88
     898
                                                                                
                                                                                
                                                                                
          882.87  882.86  882.85
                                                                                
                                                                                
        
 -112.86-112.073-111.909-111.056-110.302-109.646-109.219-107.972-107.316-106.529
 -99.705 -99.442 -98.983  -98.72 -98.458  -98.36 -97.999 -97.802 -97.408 -97.244
 -96.785 -96.654 -96.161 -96.096 -95.768 -93.668  -84.35  -51.28 -29.593 -15.781
  -5.774    -5.5    -3.2     5.5   5.512  31.234  39.075  47.802  48.589  61.811
  61.844  65.781  67.749  70.079  72.867  76.115  81.299  81.332   85.86  88.156
  92.388   94.16  98.556  99.344 103.379 104.265 104.659 106.496 106.824  107.48
 109.843
     896  895.89  895.87  895.76  895.66  895.57  895.52  895.37  895.29   895.2
     894     894     894     894     894     894     894     894     894     894
     894     894     894     894     894  893.81  893.06  889.98  888.85  888.12
   887.6   887.6   887.6  887.48  887.48  887.55  888.44  888.88  888.45  889.07
  889.07  889.25  889.35  889.46  889.59  889.75     890     890  890.82  891.24
     892  892.51  893.77     894  895.29  895.58   895.7  896.41  896.56  896.88
     898
                                                                                
                                                                                
                                                                                
          882.88  882.88  882.84
                                                                                
                                                                                
        
Abutment Skew #Up #Dn= , 2 , 2
    -5.5    -3.2
  875.23  875.23
    -5.5    -3.2
  874.42  874.42
BR Coef=-1 , 1 , 0 ,, 0 ,,,0.8,0,0.3,0,
WSPro=,,,, 1 ,,,, 0 ,,,, 0 ,,,,-1 ,-1 ,-1 , 0 , 0 , 0 , 0 , 0
BC Design=,, 0 ,, 0 ,,,,,,
BC Use User HTab Curves=0
BC User HTab FreeFlow(D)= 0

Type RM Length L Ch R = 1 ,2386.734,27.408,27.687,28.028
BEGIN DESCRIPTION:
POP_03 - Chipps Hollow Rd - DS
END DESCRIPTION:
XS GIS Cut Line= 4
  587086.7324958 4390112.7177533  587092.0299199 4390121.2948254
    587105.38016 4390140.1954736  587114.1462081 4390159.8855539
#Sta/Elev= 30
 -73.425     898 -62.402     892 -61.089  890.96 -57.152     890 -43.373  888.94
 -38.123     888 -36.745  887.41  -23.72  880.55 -12.172  875.17  -6.824  873.62
  -5.774  874.38  -4.921  874.39  -2.822  871.83   -.066  871.51   5.413  871.76
    5.61  873.06   9.777     876  12.008     878  15.846     882  20.276     888
  23.031     888  25.525  888.48   32.71  888.89  42.717  889.05  69.915     890
  78.543  891.02  84.908     892   97.31  895.68  98.885  896.28 106.299     900
#Mann= 4 ,-1 , 0
 -73.425     .12       0 -38.123     .12       0  -4.921    .045       0
    5.61     .12       0
#XS Ineff= 2 , 0
       0     -30     892               0
Permanent Ineff=
       F       F
Bank Sta=-4.921,5.61
XS Rating Curve= 0 ,0
Exp/Cntr=0.5,0.3

Type RM Length L Ch R = 1 ,2359.093,107.825,106.507,105.318
Node Name=E
XS GIS Cut Line= 4
     587078.8752    4390116.3513     587081.4099    4390120.1478
     587099.6469    4390147.1348     587109.7591    4390161.6681
#Sta/Elev= 30
  -78.44     904  -75.26     902  -66.47  895.99  -53.84  892.83 -44.226     892
 -35.531   885.9 -30.741  882.87 -21.358  877.64 -12.697     874  -6.923  871.79
  -5.741  870.36    .033  870.64   4.495  871.63   5.085  873.63   9.678  877.09
  13.189     880  16.601     882  24.245  886.04   37.24   888.8   41.77     890
    43.5     890   55.45  891.09   66.67  891.23   72.54  891.62   77.82     892
   83.66  893.01    87.3     894   92.26  895.94   96.72  897.69  101.48     900
#Mann= 3 ,-1 , 0
  -78.44     .12       0  -6.923     .05       0   4.495     .08       0
Bank Sta=-6.923,4.495
XS Rating Curve= 0 ,0
Exp/Cntr=0.3,0.1

Type RM Length L Ch R = 1 ,2252.767,273.206,288.096,315.263
Node Name=D
XS GIS Cut Line= 4
  587046.5568073 4390129.9298095  587065.6951995 4390153.6828738
  587075.7749357 4390166.4997139  587082.6176957  4390175.412066
#Sta/Elev= 30
-100.066     910 -90.846     906 -80.217     902 -66.273  900.68 -62.631  899.47
 -57.185  898.71 -46.457     892 -35.335     884  -28.74  877.52 -25.787     874
 -24.114  871.02 -17.192     868  -10.33  868.72    -5.3  867.38   -3.87  866.58
     .94  866.82    4.66  867.64   4.954  868.76   5.971  869.11   8.596     870
  11.975     872  20.801     876  34.744     878  37.434  878.48  43.668     880
  52.986  884.93   57.94     888  81.168     894   86.68  897.46  90.354  899.98
#Mann= 3 ,-1 , 0
-100.066     .12       0  -10.33    .045       0   5.971     .12       0
Bank Sta=-10.33,5.971
XS Rating Curve= 0 ,0
Exp/Cntr=0.3,0.1

Type RM Length L Ch R = 1 ,1965.16 ,170.75,175.918,181.086
Node Name=C
XS GIS Cut Line= 4
  587008.5269108 4390120.4170014  586988.8368306 4390152.7044658
  586981.9239665 4390164.0460739  586972.3837264 4390180.4717461
#Sta/Elev= 30
-123.524  898.23-117.782     898-105.315     896 -95.177     890 -87.762     886
 -82.644     882 -74.639  877.24  -71.26  875.86 -65.781     874   -64.6  873.95
  -59.58     872 -55.348     870 -49.049     866 -44.652     864  -4.921     864
   -4.62  862.05   -3.51  861.07   .0599  860.14    4.09  860.64    4.41  861.41
   4.921  863.28  14.173     866  31.923   870.5  35.761     872  43.799  876.52
  49.213  879.08  63.123     884   81.89     890 102.723     898 106.463     900
#Mann= 3 ,-1 , 0
-123.524     .12       0  -4.921     .04       0   4.921     .12       0
#XS Ineff= 2 , 0
       0     -57     890               0
Permanent Ineff=
       F       F
Bank Sta=-4.921,4.921
XS Rating Curve= 0 ,0
Exp/Cntr=0.3,0.1

Type RM Length L Ch R = 1 ,1789.541,83.263,84.092,82.463
Node Name=B
XS GIS Cut Line= 4
  586972.0728304 4390097.4594651  586967.3484303 4390101.5468331
  586949.6029741 4390117.1312573   586944.957822 4390121.3131134
#Sta/Elev= 30
 -65.748     900 -61.877     898 -56.824  894.89 -43.504  886.23 -36.811     882
 -30.217     878 -27.165     876 -19.948  872.09 -15.387     870 -11.417  868.42
  -9.974  867.66  -7.579     866  -4.921  862.46  -3.281  860.28   -2.77  855.78
    2.12  854.77    3.36  854.93    3.41  855.11    3.55  855.14    3.98  855.12
   4.921  862.38   9.022     868   9.843     870  11.581  873.22  13.812  877.07
  19.127  884.93  25.394  889.96  34.711  894.55   41.47     898  52.723     904
#Mann= 4 ,-1 , 0
 -65.748     .12       0 -43.504     .12       0  -4.921    .045       0
   4.921     .12       0
Bank Sta=-4.921,4.921
XS Rating Curve= 0 ,0
Exp/Cntr=0.3,0.1