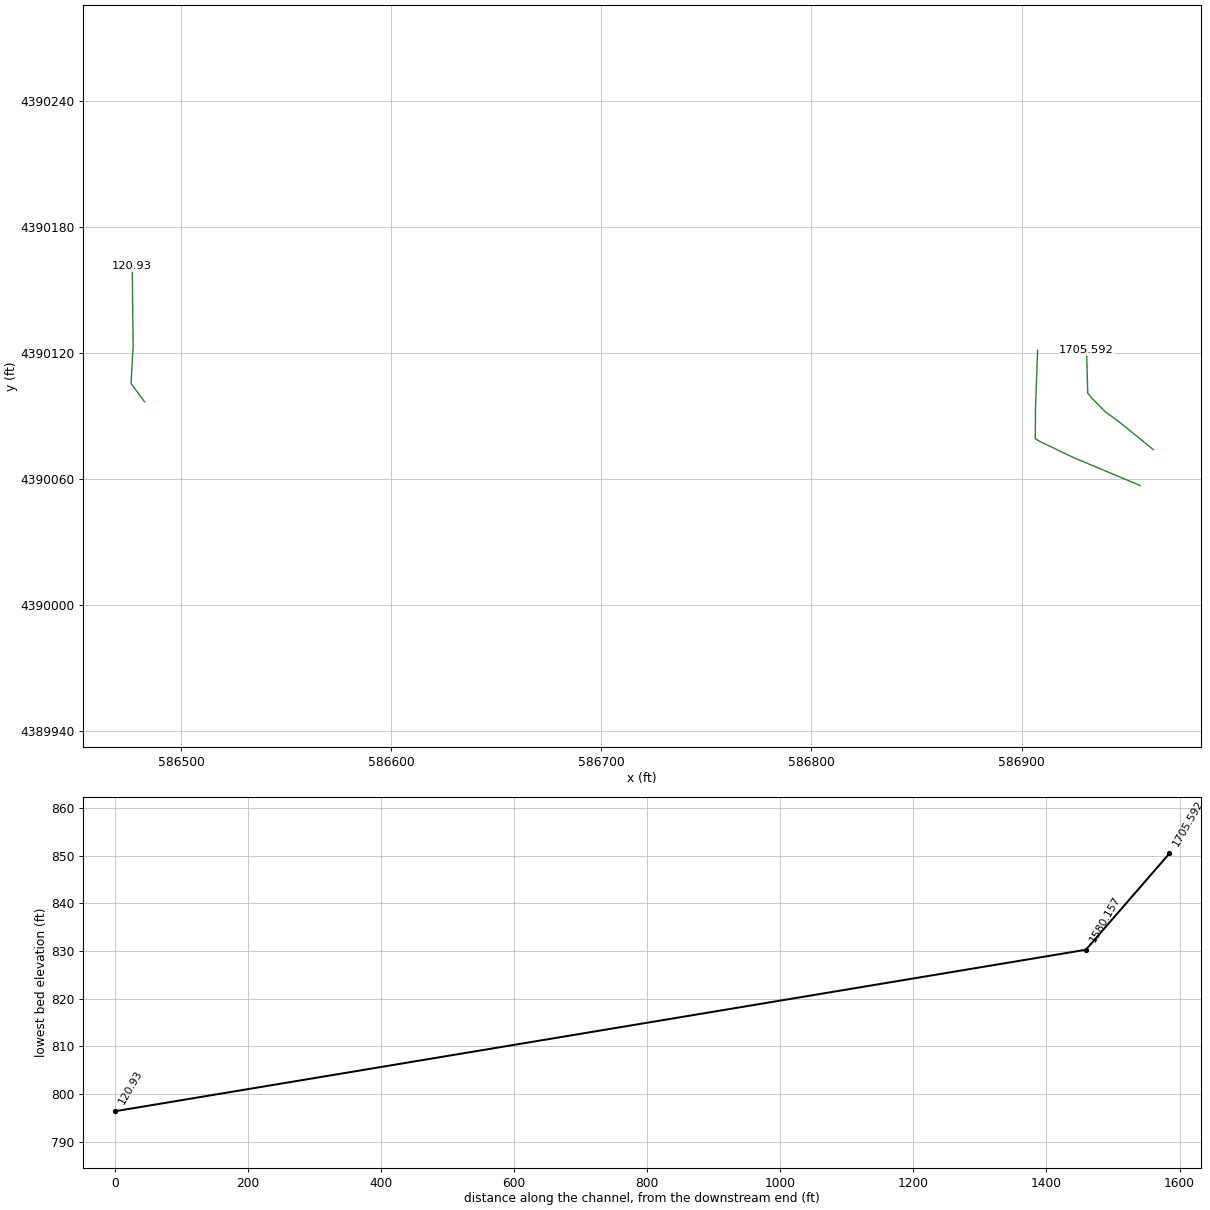
HEC-RAS study Pompono_Run_Detail_Study.prj: Pompono_Run_Detail_Study

--- Pompono_Run_Detail_Study.g01 (geometry) --- (continued)

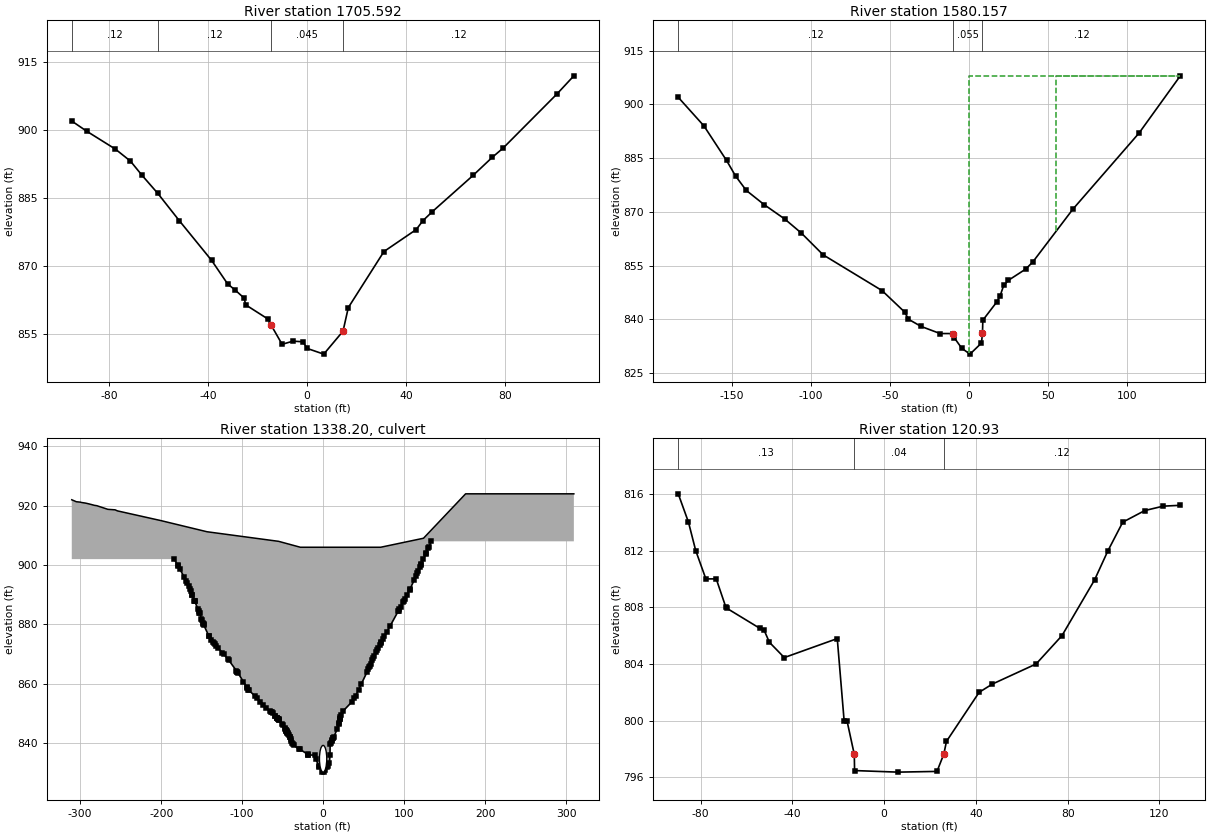
Type RM Length L Ch R = 1 ,1705.592,114.874,125.648,112.031
Node Name=A
XS GIS Cut Line= 6
  586962.7489983 4390074.1056888   586946.137398  4390087.568705
   586940.004822  4390091.988305  586933.3662779 4390098.7000011
  586931.4826139 4390101.0195291  586930.9339739 4390121.3771214
#Sta/Elev= 30
 -94.948     902 -88.878  899.74 -77.362   895.8 -71.293  893.15 -66.601     890
 -60.236     886 -51.608     880 -38.517  871.18 -32.087     866 -29.035  864.63
 -25.394  862.85 -24.803  861.37 -15.814  858.23  -14.57  856.92 -10.105  852.64
  -5.709  853.34  -1.706   853.2       0  851.73   6.693  850.47  14.469  855.54
  16.601  860.76  30.971  873.15  43.963     878  46.752     880  50.558     882
  66.962     890  74.705     894  79.003     896 100.787     908 107.579     912
#Mann= 4 ,-1 , 0
 -94.948     .12       0 -60.236     .12       0  -14.57    .045       0
  14.469     .12       0
Bank Sta=-14.57,14.469
XS Rating Curve= 0 ,0
Exp/Cntr=0.5,0.3

Type RM Length L Ch R = 1 ,1580.157,1489.396,1459.22,1461.791
BEGIN DESCRIPTION:
POP-02 - Monongahela Blvd - US
END DESCRIPTION:
XS GIS Cut Line= 6
  586956.4365902 4390057.0460326  586924.6611898 4390070.3810327
  586908.7414856 4390077.9949368  586906.5316856 4390079.3177689
  586906.6170296  4390094.076185  586907.6350616 4390121.4289374
#Sta/Elev= 30
-183.957     902-167.684     894-153.412  884.37-147.671     880-140.945     876
 -129.56     872-116.601     868 -106.07  864.07 -92.323     858  -55.02     848
 -40.715     842  -38.32     840 -30.381     838 -18.307     836 -10.203     836
  -9.252  834.77   -4.56  831.87    .623  830.25   7.874  833.35    8.52  836.16
   8.727  839.72  17.487  844.78  19.587  846.42  21.916  849.44  24.967  850.89
  35.827     854  40.354     856   65.65  870.72 107.546     892 133.661     908
#Mann= 3 , 0 , 0
-183.957     .12       0 -10.203    .055       0    8.52     .12       0
#XS Ineff= 2 , 0
       0     -55     908      55       0     908
Permanent Ineff=
       F       F
Bank Sta=-10.203,8.52
XS Rating Curve= 0 ,0
Minor Loss Coefficient=0.5
Exp/Cntr=0.5,0.3

Type RM Length L Ch R = 2 ,1338.20 ,,,
BEGIN DESCRIPTION:
POP-02 - Monongahela Blvd
TOR elevations on right side were raised to refleft the higher embankment.
END DESCRIPTION:
Bridge Culvert--1,0,-1,-1, 0
Deck Dist Width WeirC Skew NumUp NumDn MinLoCord MaxHiCord MaxSubmerge Is_Ogee
8,1390,3,0, 26, 26, , , 0.98, 0, 0,0,,
  -310.4-304.823 -303.74-299.934-298.327-297.999-293.307-291.831 -290.65-289.665
-288.156-282.349-279.429-265.879-263.845 -261.68 -256.89-254.035-200.262-143.438
     -55     -28      71     124     176 309.678
     922  921.34  921.31   921.2  921.08  921.07  920.87  920.78   920.7  920.64
  920.54  920.12     920  918.78  918.74   918.7  918.61  918.26  914.98  911.23
     908     906     906  909.04     924     924
                                                                                
                                                                                
                                                
  -310.4-304.823 -303.74-299.934-298.327-297.999-293.307-291.831 -290.65-289.665
-288.156-282.349-279.429-265.879-263.845 -261.68 -256.89-254.035-200.262-143.438
     -55     -28      71     124     176 309.678
     922  921.34  921.31   921.2  921.08  921.07  920.87  920.78   920.7  920.64
  920.54  920.12     920  918.78  918.74   918.7  918.61  918.26  914.98  911.23
     908     906     906  909.04     924     924
                                                                                
                                                                                
                                                
BR Coef=-1 , 0 , 0 ,, 0 ,,,0.8,0,,0,
WSPro=,,,, 1 ,,,, 0 ,,,, 0 ,,,,-1 ,-1 ,-1 , 0 , 0 , 0 , 0 , 0
Culvert=1,9,,1400,0.024,0.5,1,2,1,830.25,0,795.47,0,Culvert #1  , 0 ,7.5
Culvert Bottom n=0.024
BR U #Sta/Elev= 164
-183.957     902-179.659     900-178.904  899.64-176.739  898.54-171.621     896
-168.963  894.64-167.684     894-166.109  892.92-164.764     892-163.583   891.2
-161.844     890-161.549  889.79-158.891  888.06-158.793  888.01-158.793     888
-154.659  885.15-153.412  884.37 -152.92     884-152.625  883.78-150.328     882
-149.541  881.41-148.392  880.54-147.867  880.14-147.671     880-147.507  879.89
-141.371  876.21-140.945     876-137.959  874.92-135.433     874-134.875  873.82
-134.055  873.54 -131.89  872.81 -129.56     872-124.344  870.49-122.736     870
-117.979  868.44-116.601     868-106.955  864.39 -106.07  864.07-105.906     864
-105.413  863.78 -98.589  860.76 -94.357  858.89  -93.57  858.55 -92.323     858
 -92.126  857.94 -84.613     856 -81.594  855.13 -77.526     854  -73.72     853
 -70.899     852 -66.109  850.89 -64.501  850.57  -63.55   850.4 -61.778     850
 -59.383  849.19 -58.957  849.08 -57.251  848.65 -56.857  848.52 -56.365  848.38
 -55.741   848.2 -55.676  848.18  -55.02     848 -54.429  847.76 -54.167  847.67
 -50.951  846.43 -49.902     846 -47.605  845.02  -47.08  844.79 -46.194  844.45
 -45.965  844.35  -45.44  844.15 -45.374  844.12 -45.046     844 -44.915  843.93
 -44.488  843.73  -44.16  843.58 -43.963  843.51 -43.241  843.21 -42.093  842.66
 -41.142   842.2 -40.715     842 -40.125  841.52 -39.173  840.73  -38.32     840
 -37.008  839.64 -35.892  839.33 -30.381     838 -28.904     838 -18.799   836.2
 -18.438  836.05 -18.307     836 -10.203     836  -9.252  834.77  -5.381  832.37
   -4.56  831.87   -1.16   830.3    .623  830.25    2.41   830.9   4.921  832.03
   5.446  832.24   7.874  833.35    8.52  836.16   8.727  839.72   9.285     840
  10.696  840.76   11.45  841.18    12.5  841.72  12.664  841.81  13.058     842
  17.487  844.78  19.587  846.42  19.816  846.73  20.735     848  20.899  848.19
  21.457  848.87  21.916  849.44  24.967  850.89  35.827     854  38.419  855.14
  40.354     856  43.865     858   47.08  859.83  54.298     864   55.61  864.83
  57.087  865.73  57.546     866  58.891  866.81   60.86     868  62.073   868.7
  63.189  869.34   65.65  870.72  66.896  871.38  68.045     872  70.079  873.06
  71.161  873.63   71.85     874  73.688  874.93  75.787     876  78.675  877.42
  82.972  879.57  92.782  884.44  93.176  884.65  94.259  885.19  95.833     886
   98.72  887.48  99.738     888 100.591  888.42 103.642     890 106.726  891.57
 107.546     892 112.697  895.05 114.764  896.31 116.207  897.21 117.454     898
 119.718  899.42 120.669     900 121.358  900.43 123.917     902 126.673  903.66
 127.198     904 130.151  905.77 130.545     906 133.661     908
BR U #Mann= 3
-183.957     .12  -5.381    .035    8.52     .12
BR D #Sta/Elev= 133
 -89.764     816 -89.173  815.74 -85.302     814 -84.186  813.34  -83.53  812.92
 -82.152     812 -78.248  810.25 -77.953  810.11 -77.723     810 -73.196     810
 -72.474  809.67 -71.522  809.24 -69.948  808.46 -68.996     808 -68.602  807.93
 -68.307   807.9 -67.585  807.86 -54.265  806.52 -52.461  806.43 -50.033  805.53
  -46.49  804.92 -46.227   804.9 -45.997  804.88 -43.537  804.45  -20.44  805.79
 -20.407  805.73 -20.374  805.63  -20.21  805.33 -18.898  802.75  -18.57  802.17
 -18.504     802 -18.406  801.84 -17.454     800 -16.207     800  -13.02  797.62
 -12.894  796.48   -5.02  796.43    -1.5  795.46       0  795.46     1.5  795.46
   3.412  796.38    5.02  796.38   5.938  796.37   26.02  797.65  27.165  798.54
  41.404     802   41.47  802.01  41.962  802.05  42.356  802.09  42.585  802.11
  42.782  802.13  43.143  802.17  47.146  802.58  53.412  803.01  58.202  803.41
  58.727  803.44  59.285  803.48  59.875  803.51  60.499  803.56  61.155   803.6
  61.877  803.66  62.631  803.71  63.419  803.78  63.812  803.81   66.24     804
  68.832  804.51  69.193  804.57  69.652  804.64  70.112  804.73  70.768  804.84
  71.194  804.92  71.555  804.99  72.441  805.13  72.769  805.19  73.064  805.24
  74.213  805.44  74.409  805.48  74.606  805.51  76.017  805.75  76.115  805.76
  77.526     806  77.822  806.09   84.58     808  85.138  808.16  85.269   808.2
  85.531  808.26  87.434   808.8  88.812  809.15  89.764  809.41  90.289  809.54
  90.912   809.7  91.699  809.92  91.962     810  92.454  810.16  93.045  810.35
  94.915  811.02  95.571  811.26  96.227  811.51  97.507  811.97  97.605     812
  98.261  812.18  98.392  812.21  99.081  812.41  99.409  812.51 100.033  812.69
 100.591  812.87 101.476  813.14 104.003     814 104.593  814.06 105.446  814.16
 106.234  814.24 106.955  814.32 107.612  814.38 108.399  814.39 109.154  814.46
 109.843  814.51 110.499  814.57 111.089  814.62 113.615  814.82 115.223  814.83
 116.404  814.91 116.667  814.93 118.438  814.93 119.029  814.97 119.291  814.99
 119.357  814.99 121.621  815.13 123.688  815.13 124.147  815.15 126.247  815.15
 126.706  815.17 127.133   815.2 129.101  815.19
BR D #Mann= 3
 -89.764     .13  -13.02    .035   26.02     .12
BC Design=,, 0 ,, 0 ,,,,,,
BC Use User HTab Curves=0
BC User HTab FreeFlow(D)= 0

Type RM Length L Ch R = 1 ,120.93  ,131.379,121.136,109.975
BEGIN DESCRIPTION:
POP-02 - Monongahela Blvd - DS
END DESCRIPTION:
XS GIS Cut Line= 4
 586482.615840324390096.90168107 586476.175416244390105.60067318
586477.1538242534390123.14496139586476.7301522474390161.45527387
#Sta/Elev= 30
 -89.764     816 -85.302     814 -82.152     812 -77.723     810 -73.196     810
 -68.996     808 -68.602  807.93 -54.265  806.52 -52.461  806.43 -50.033  805.53
 -43.537  804.45  -20.44  805.79 -17.454     800 -16.207     800  -13.02  797.62
 -12.894  796.48   5.938  796.37  23.033  796.42   26.02  797.65  27.165  798.54
  41.404     802  47.146  802.58   66.24     804  77.526     806  91.699  809.92
  97.507  811.97 104.003     814 113.615  814.82 121.621  815.13 129.101  815.19
#Mann= 3 ,-1 , 0
 -89.764     .13       0  -13.02     .04       0   26.02     .12       0
#XS Ineff= 2 , 0
       0   -23.8     908      50       0     908
Permanent Ineff=
       F       F
Bank Sta=-13.02,26.02
XS Rating Curve= 0 ,0
Minor Loss Coefficient=0.5
Exp/Cntr=0.5,0.3
Stream Node=Pompano Run     ,1               , 0 , 0 ,Upstream end
Stream Node=Pompano Run     ,1               , 0 , 1 ,Downstream end

Chan Stop Cuts=-1
Use User Specified Reach Order=0
Composite Channel Slope=5