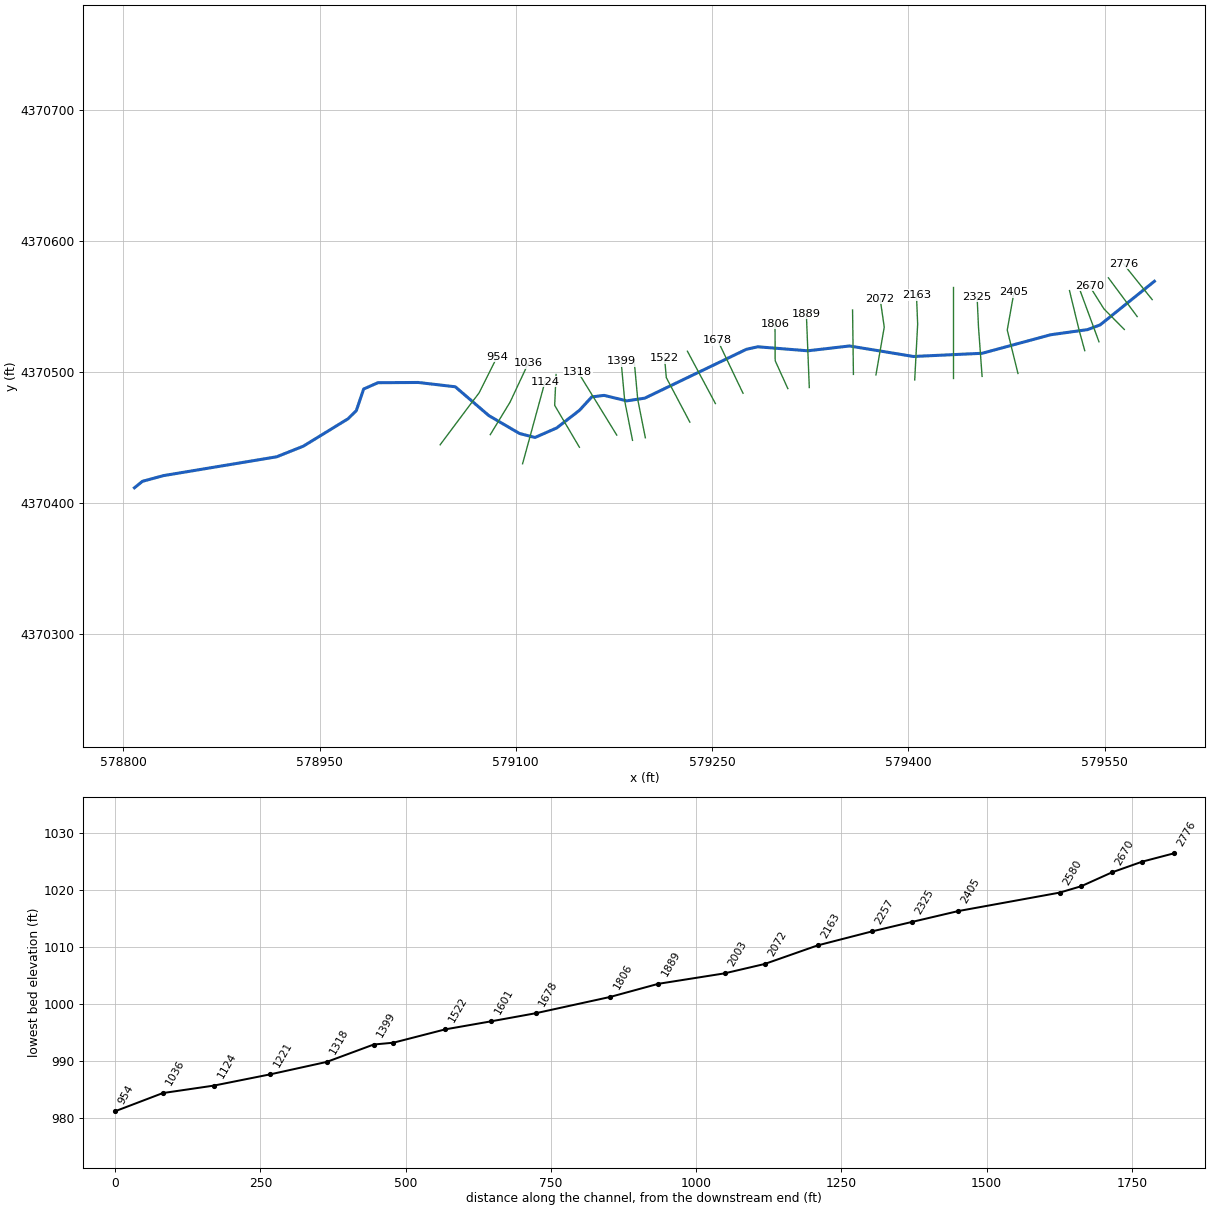
--- Reuben_Run.prj (project) ---

Proj Title=Reuben Run
Current Plan=p01
Default Exp/Contr=0.3,0.1
English Units
Geom File=g01
Flow File=f01
Flow File=f02
Plan File=p01
Plan File=p02
Y Axis Title=Elevation
X Axis Title(PF)=Main Channel Distance
X Axis Title(XS)=Station
BEGIN DESCRIPTION:
Detailed Study for Reuben Run
Upper Monongahela Watershed, Marion County, WV
Submitted by RAMPP for FEMA Region III
Model date: October 2015
HEC-RAS version 4.1.0
Vertical Datum: NAVD88 (feet)
Horizontal Datum: NAD_1983_UTM_Zone_17N
END DESCRIPTION:
DSS Export Rating Curves= 0
DSS Export Rating Curve Sorted= 0
DSS Export Volume Flow Curves= 0
DXF Filename=..\..\..\..\..\DETAILED\Basin_HUC_Stream\HEC-RAS\Reuben Run\Reuben_Run.
DXF OffsetX= 0
DXF OffsetY= 0
DXF ScaleX= 1
DXF ScaleY= 10

--- Reuben_Run.p01 (plan) ---

Plan Title=Reuben Run - Multiprofile
Program Version=4.10
Short Identifier=Multiprofile
Geom File=g01
Flow File=f01
Subcritical Flow
K Sum by GR= 0
Std Step Tol= 0.01
Critical Tol= 0.01
Num of Std Step Trials= 20
Max Error Tol= 0.3
Flow Tol Ratio= 0.001
Split Flow NTrial= 30
Split Flow Tol= 0.02
Split Flow Ratio= 0.02
Log Output Level= 0
Friction Slope Method= 1
Unsteady Friction Slope Method= 2
Unsteady Bridges Friction Slope Method= 1
Parabolic Critical Depth
Global Vel Dist= 0 , 0 , 0
Global Log Level= 0
CheckData=True
Encroach Param=-1 ,0,0, 0
Computation Interval=1HOUR
Output Interval=1HOUR
Run HTab= 0
Run UNet= 0
Run PostProcess= 0
Run WQNet= 0
UNET Theta= 1
UNET Theta Warmup= 1
UNET ZTol= 0.02
UNET ZSATol= 0.05
UNET MxIter= 20
UNET MaxInSteps= 0
UNET DtIC= 0
UNET DtMin= 0
UNET MaxCRTS= 20
UNET WFStab= 2
UNET SFStab= 1
UNET WFX= 1
UNET SFX= 1
UNET DSS MLevel= 4
UNET DZMax Abort= 100
UNET Convert EG Bridges= 0
UNET Use Existing IB Tables=-1
UNET Froude Reduction=False
UNET Froude Limit= 1
UNET Froude Power= 10
UNET Time Slicing=0,0, 5
UNET Junction Losses=0
Instantaneous Interval=1HOUR
DSS File=dss
Write IC File= 0
Write IC File at Sim End=0
Echo Input=False
Echo Parameters=False
Echo Output=False
Write Detailed= 0
WQ AD Non Conservative
WQ ULTIMATE=-1
WQ Max Comp Step=1HOUR
WQ Output Interval=15MIN
WQ Output Selected Increments= 0
WQ Output face flow=0
WQ Output face velocity=0
WQ Output face area=0
WQ Output face dispersion=0
WQ Output cell volume=0
WQ Output cell surface area=0
WQ Output cell continuity=0
WQ Output cumulative cell continuity=0
WQ Output face conc=0
WQ Output face dconc_dx=0
WQ Output face courant=0
WQ Output face peclet=0
WQ Output face adv mass=0
WQ Output face disp mass=0
WQ Output cell mass=0
WQ Output cell source sink temp=0
WQ Output cell source sink nsm=0
WQ Output MaxMinRange=-1
WQ Daily Max Min Mean=-1
WQ Daily Range=0
WQ Daily Time=0
WQ Create Restart=0
WQ Fixed Restart=0
WQ System Summary=0
WQ Use Fixed Temperature=0
Sorting and Armoring Iterations= 10
XS Update Threshold= 0.02
Hydraulics Update Threshold= 0.02
Energy Slope Method= 1
Volume Change Method= 0
XS Weighting Method= 0
Number of US Weighted Cross Sections= 1
Number of DS Weighted Cross Sections= 1
Upstream XS Weight=0.25
Main XS Weight=0.5
Downstream XS Weight=0.25
Number of DS XS's Weighted with US Boundary= 1
Upstream Boundary Weight= 1
Weight of XSs Associated with US Boundary= 0
Number of US XS's Weighted with DS Boundary= 1
Downstream Boundary Weight= 0.5
Weight of XSs Associated with DS Boundary= 0.5
Sediment Output Level= 4
Mass or Volume Output= 0
Output Increment Type= 1
Profile and TS Output Increment= 10
XS Output Flag= 0
XS Output Increment= 10
Disregard all LS=0
Disregard all Conn=0
Disregard all Breaches=0
Disregard all Pumps=0

--- Reuben_Run.p02 (plan) ---

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Plan Title=Reuben Run - Floodway
Short Identifier=Floodway
Geom File=g01
Flow File=f02
Encroach Param=-1 ,0,0, 2
Encroach River=Reuben Run
Encroach Reach=Reach 1
Encroach Node=2776
       1  -12.18   13.02
Encroach Node=2722
       1    -9.5   14.17
Encroach Node=2670
       1   -9.94    13.2
Encroach Node=2617
       1  -10.18     7.5
Encroach Node=2580
       1   -9.72   11.73
Encroach Node=2405
       1  -12.04      10
Encroach Node=2325
       1     -17    12.8
Encroach Node=2257
       1   -9.11    9.61
Encroach Node=2163
       1   -6.36   10.04
Encroach Node=2072
       1   -8.88       8
Encroach Node=2003
       1   -9.32   11.12
Encroach Node=1889
       1   -12.4    14.3
Encroach Node=1806
       1      -7   13.68
Encroach Node=1678
       1   -12.6     8.5
Encroach Node=1601
       1   -10.1   10.86
Encroach Node=1522
       1     -19    10.2
Encroach Node=1433
       1  -12.03      16
Encroach Node=1399
       1   -9.31    26.5
Encroach Node=1318
       1      -9       8
Encroach Node=1221
       1   -14.3    13.5
Encroach Node=1124
       1  -12.66   14.93
Encroach Node=1036
       1  -10.04   13.09
Encroach Node=954
       1     -15      21
Encroach Node=915
       1     -15      15
Encroach Node=837
       1  -17.01   17.81
Encroach Node=818
       1  -14.86   18.06
Encroach Node=783
       1  -16.85   12.04
Encroach Node=725
       1     -26   11.27
Encroach Node=706
       1  -20.01    12.2
Encroach Node=687
       1  -21.88    9.38
Encroach Node=644
       1   -14.7   10.53
Encroach Node=585
       1  -13.74   10.97
Encroach Node=505
       1   -16.5    10.5
Encroach Node=461
       1  -19.79   11.31
Encroach Node=394
       1  -19.88    8.76
Encroach Node=323
       1     -15      12
Encroach Node=284
       1  -20.62   14.37
Encroach Node=265
       1     -12   14.27
Encroach Node=229
       1    -8.8       9
Encroach Node=165
       1  -12.87   13.52
Encroach Node=93
       1  -14.31   12.81
Encroach Node=38
       1  -14.38   13.42

--- Reuben_Run.f01 (steady flow) ---

Flow Title=Reuben Run - Multiprofile
Program Version=4.10
Number of Profiles= 6
Profile Names=10PCT,4PCT,2PCT,1PCT,1PCT_PLUS,0.2PCT
River Rch & RM=Reuben Run,Reach 1         ,2776
     286     383     462     546     723     760
River Rch & RM=Reuben Run,Reach 1         ,2405
     324     433     522     615     816     855
River Rch & RM=Reuben Run,Reach 1         ,1678
     331     443     534     629     834     874
River Rch & RM=Reuben Run,Reach 1         ,837
     332     444     535     630     835     875
River Rch & RM=Reuben Run,Reach 1         ,644
     333     446     537     633     839     879
River Rch & RM=Reuben Run,Reach 1         ,323
     334     447     539     635     841     881
River Rch & RM=Reuben Run,Reach 1         ,165
     335     447     539     636     842     882
Boundary for River Rch & Prof#=Reuben Run,Reach 1         , 1
Up Type= 0
Dn Type= 3
Dn Slope=0.025
Boundary for River Rch & Prof#=Reuben Run,Reach 1         , 2
Up Type= 0
Dn Type= 3
Dn Slope=0.025
Boundary for River Rch & Prof#=Reuben Run,Reach 1         , 3
Up Type= 0
Dn Type= 3
Dn Slope=0.025
Boundary for River Rch & Prof#=Reuben Run,Reach 1         , 4
Up Type= 0
Dn Type= 3
Dn Slope=0.025
Boundary for River Rch & Prof#=Reuben Run,Reach 1         , 5
Up Type= 0
Dn Type= 3
Dn Slope=0.025
Boundary for River Rch & Prof#=Reuben Run,Reach 1         , 6
Up Type= 0
Dn Type= 3
Dn Slope=0.025
DSS Import GetInterval= 0
DSS Import GetPeak= 0
DSS Import FillOption= 0

--- Reuben_Run.f02 (steady flow) ---

Flow Title=Reuben Run - Floodway
Program Version=4.10
Number of Profiles= 2
Profile Names=1PCT,FLOODWAY
River Rch & RM=Reuben Run,Reach 1         ,2776
     546     546
River Rch & RM=Reuben Run,Reach 1         ,2405
     615     615
River Rch & RM=Reuben Run,Reach 1         ,1678
     629     629
River Rch & RM=Reuben Run,Reach 1         ,837
     630     630
River Rch & RM=Reuben Run,Reach 1         ,644
     633     633
River Rch & RM=Reuben Run,Reach 1         ,323
     635     635
River Rch & RM=Reuben Run,Reach 1         ,165
     636     636
Boundary for River Rch & Prof#=Reuben Run,Reach 1         , 1
Up Type= 0
Dn Type= 3
Dn Slope=0.025
Boundary for River Rch & Prof#=Reuben Run,Reach 1         , 2
Up Type= 0
Dn Type= 3
Dn Slope=0.025
DSS Import GetInterval= 0
DSS Import GetPeak= 0
DSS Import FillOption= 0

--- Reuben_Run.g01 (geometry) ---

Geom Title=Reuben Run
Program Version=4.10

River Reach=Reuben Run      ,Reach 1
Reach XY= 30
579588.0772455114370569.31397733579546.5671425984370535.96398012
579536.9372912794370532.36398727579508.7871821314370528.44395442
579456.3972430834370514.27410705579403.9070248344370511.83387822
 579355.007045834370519.87389272579323.1572742364370516.17392547
579284.9472409644370519.24387111579276.2671464574370517.33399428
579198.5672246974370479.99416502579184.867074127 4370477.9239634
579167.4770147124370482.09393225579158.0571705964370480.93386343
 579148.637021684370470.66393211579131.2771374654370457.22408074
 579114.667061264370449.92412065579102.8072931134370452.99406629
579079.4172456244370466.64392486579053.7372357074370488.67395473
579025.4170481574370491.97402437578994.6072541764370491.78413397
578983.7271132414370486.97408511578978.1172691724370470.48410011
578971.7271370934370464.18388403578937.6471438724370443.29411097
 578917.267301224370435.17393407578830.8071225524370420.80413789
578814.6670479524370416.44397384578808.5170982764370411.46415138

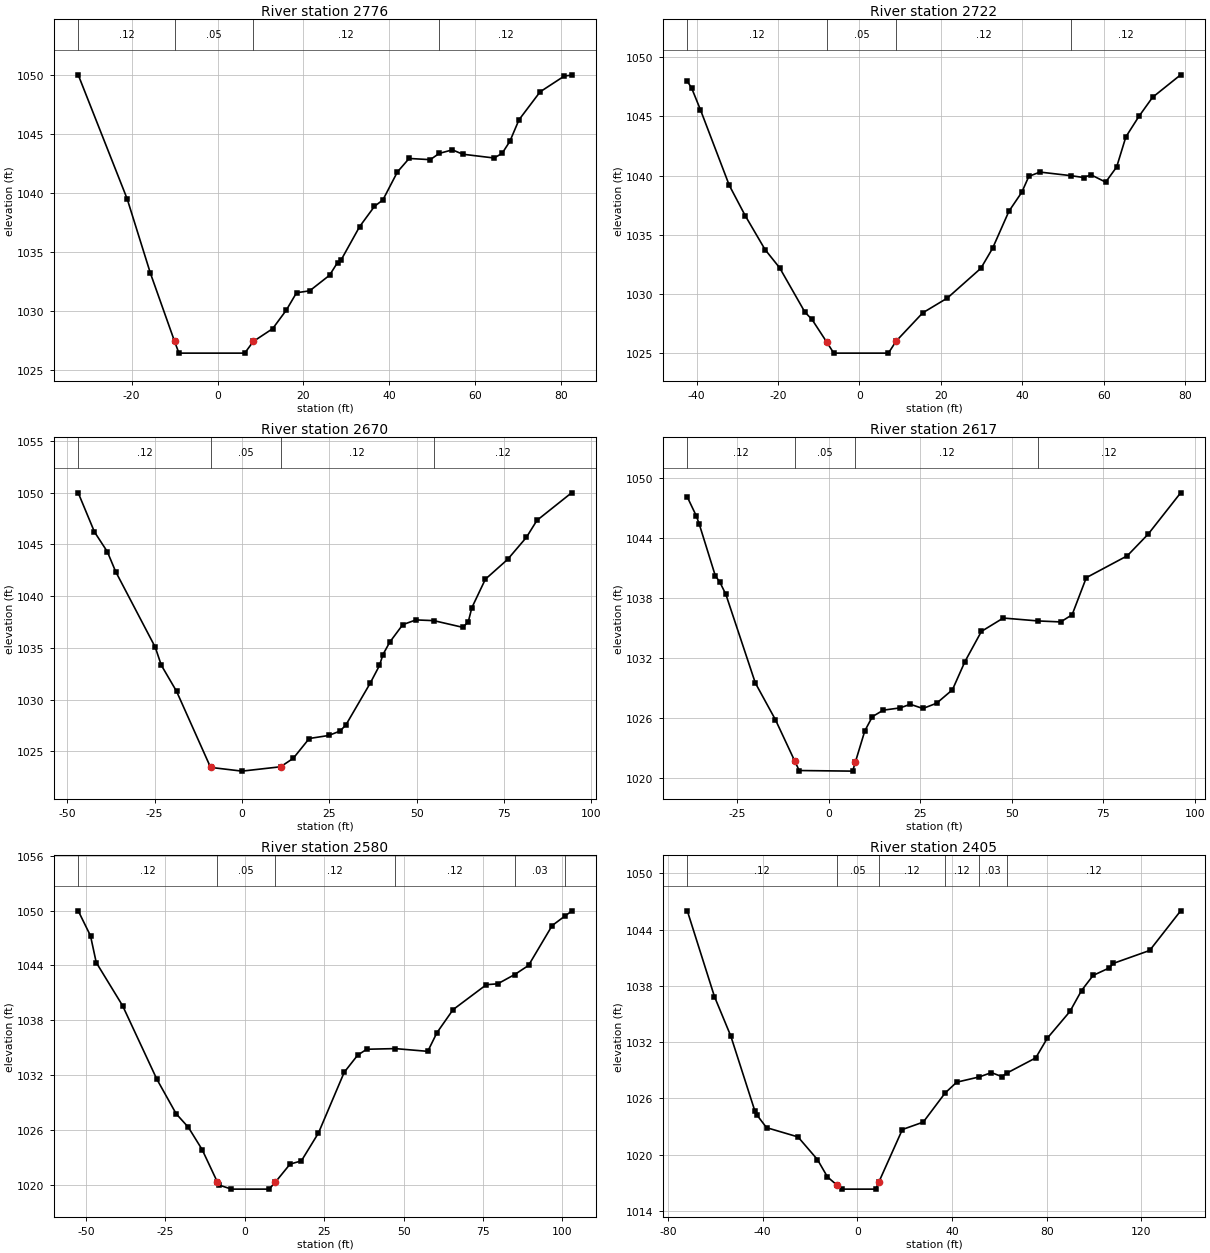
Type RM Length L Ch R = 1 ,2776    ,54.34,54,53.68
XS GIS Cut Line= 2
 579586.377071094370555.30414995579564.4171452184370582.59411349
#Sta/Elev= 30
 -32.448    1050  -21.03 1039.47  -15.65  1033.2     -10  1027.4   -8.99 1026.41
   6.332 1026.41   8.333  1027.4  12.828 1028.48   16.01 1030.05  18.406 1031.53
  21.457 1031.69  26.083 1033.01  27.953 1034.09   28.74 1034.28  33.104 1037.14
  36.549 1038.85  38.517  1039.4  41.896 1041.77  44.619 1042.91  49.541 1042.81
   51.64 1043.34  54.692 1043.64  57.119 1043.27  64.403 1042.95  66.273 1043.34
  68.077 1044.36   70.21 1046.19  75.131 1048.56  80.774  1049.9  82.448 1049.97
#Mann= 4 ,-1 , 0
 -32.448     .12       0     -10     .05       0   8.333     .12       0
   51.64     .12       0
Bank Sta=-10,8.333
XS Rating Curve= 0 ,0
Exp/Cntr=0.3,0.1

Type RM Length L Ch R = 1 ,2722    ,50.86,52,53.09
XS GIS Cut Line= 2
579574.9071421484370542.33399539579552.8972290764370571.97396696
#Sta/Elev= 30
 -42.257 1047.97 -41.207 1047.41 -39.042 1045.57 -31.955 1039.17 -28.051 1036.61
 -23.163 1033.73 -19.587 1032.19 -13.386 1028.44 -11.647 1027.82      -8 1025.89
  -6.299 1024.97   7.119 1024.97       9 1025.98  15.551 1028.38  21.588 1029.63
  29.823 1032.15  32.677 1033.83  36.713 1036.98  39.862 1038.58  41.601 1039.93
  44.324 1040.29   51.87 1039.99  55.052 1039.83  56.857 1040.06  60.466 1039.44
  63.156 1040.72   65.42 1043.27  68.635 1045.01  71.982 1046.62  78.871 1048.52
#Mann= 4 ,-1 , 0
 -42.257     .12       0      -8     .05       0       9     .12       0
   51.87     .12       0
Bank Sta=-8,9
XS Rating Curve= 0 ,0
Exp/Cntr=0.3,0.1

Type RM Length L Ch R = 1 ,2670    ,56.62,53,49.68
XS GIS Cut Line= 3
579565.0672836264370532.48407847579549.4770682344370548.23400907
579538.3671080964370565.92399168
#Sta/Elev= 30
 -46.883 1049.97 -42.224 1046.19  -38.55 1044.29 -36.155 1042.36 -24.836 1035.07
 -23.097 1033.33 -18.734 1030.81   -8.99 1023.46       0  1023.1  11.056 1023.52
  14.698 1024.34  19.259 1026.25  24.803 1026.54  28.084 1026.97  29.757 1027.56
  36.713 1031.59   39.37  1033.3  40.354 1034.35  42.323 1035.56   46.03 1037.24
  49.803  1037.7  54.921 1037.63  63.255 1036.98  64.797 1037.53  65.814 1038.88
  69.685 1041.63   76.05 1043.54   81.43 1045.67  84.449 1047.31  94.357 1049.97
#Mann= 4 ,-1 , 0
 -46.883     .12       0   -8.99     .05       0  11.056     .12       0
  54.921     .12       0
Bank Sta=-8.99,11.056
XS Rating Curve= 0 ,0
Exp/Cntr=0.3,0.1

Type RM Length L Ch R = 1 ,2617    ,37.54,37,35.8
XS GIS Cut Line= 2
579545.6972433874370523.07398796579531.5170328124370561.59400283
#Sta/Elev= 30
 -38.615  1048.1 -36.188 1046.23   -35.4 1045.44 -30.971 1040.22 -29.757  1039.6
 -28.084 1038.35 -20.046 1029.49 -14.567 1025.82    -9.3 1021.69  -8.071 1020.73
   6.529 1020.67   7.251 1021.56   9.843  1024.7  11.909 1026.12  14.862 1026.77
  19.521    1027  22.244 1027.36  25.689 1026.94  29.429 1027.46   33.76 1028.81
  37.172 1031.63  41.667 1034.65  47.638 1035.99  57.119  1035.7   63.32  1035.6
  66.437 1036.32  70.308 1040.03  81.496 1042.22  87.205 1044.39  96.063 1048.52
#Mann= 4 ,-1 , 0
 -38.615     .12       0    -9.3     .05       0   7.251     .12       0
  57.119     .12       0
Bank Sta=-9.3,7.251
XS Rating Curve= 0 ,0
Exp/Cntr=0.3,0.1

Type RM Length L Ch R = 1 ,2580    ,175.12,175,175.09
XS GIS Cut Line= 3
579534.8372192534370516.29401667   579530.5870884370531.70409526
579523.1770951094370562.18409564
#Sta/Elev= 30
 -52.461 1049.97 -48.589 1047.24 -46.785 1044.32 -38.484  1039.6  -27.69 1031.56
 -21.621 1027.79 -17.782 1026.31 -13.451 1023.88    -8.7 1020.37  -8.235 1020.01
  -4.199 1019.55   7.644 1019.55   9.613 1020.31  14.239 1022.28  17.815 1022.64
  23.196 1025.69  31.299 1032.32  35.531 1034.19  38.386 1034.84  47.375 1034.91
  57.612 1034.61  60.499 1036.65  65.584 1039.17  76.083  1041.9  79.626 1041.99
  85.007 1043.01  89.337    1044  96.785 1048.36 100.722 1049.38 102.887 1049.93
#Mann= 6 ,-1 , 0
 -52.461     .12       0    -8.7     .05       0   9.613     .12       0
  47.375     .12       0  85.007     .03       0 100.722     .12       0
Bank Sta=-8.7,9.613
XS Rating Curve= 0 ,0
Exp/Cntr=0.3,0.1

Type RM Length L Ch R = 1 ,2405    ,81.56,80,78.42
XS GIS Cut Line= 3
579483.7871810224370498.83415806 579475.597204924370532.04394727
579480.7471057844370560.89387722
#Sta/Elev= 30
  -71.85    1046 -60.367 1036.84 -53.478 1032.64  -43.34 1024.67 -42.421 1024.21
 -38.386 1022.87 -25.098 1021.88 -16.864 1019.46 -12.664 1017.62  -8.596 1016.73
  -6.463 1016.31   7.743 1016.31       9 1017.03  18.996 1022.67  27.822 1023.46
  37.073 1026.57  41.962 1027.72  51.476 1028.28  56.627 1028.74  61.056 1028.31
  62.992 1028.67  75.328 1030.31  80.217 1032.41  89.797 1035.27  94.685  1037.5
  99.573 1039.11 106.332  1039.9 108.071 1040.39 123.458 1041.77 136.549    1046
#Mann= 6 ,-1 , 0
  -71.85     .12       0  -8.596     .05       0       9     .12       0
  37.073     .12       0  51.476     .03       0  62.992     .12       0
Bank Sta=-8.596,9
XS Rating Curve= 0 ,0
Exp/Cntr=0.3,0.1

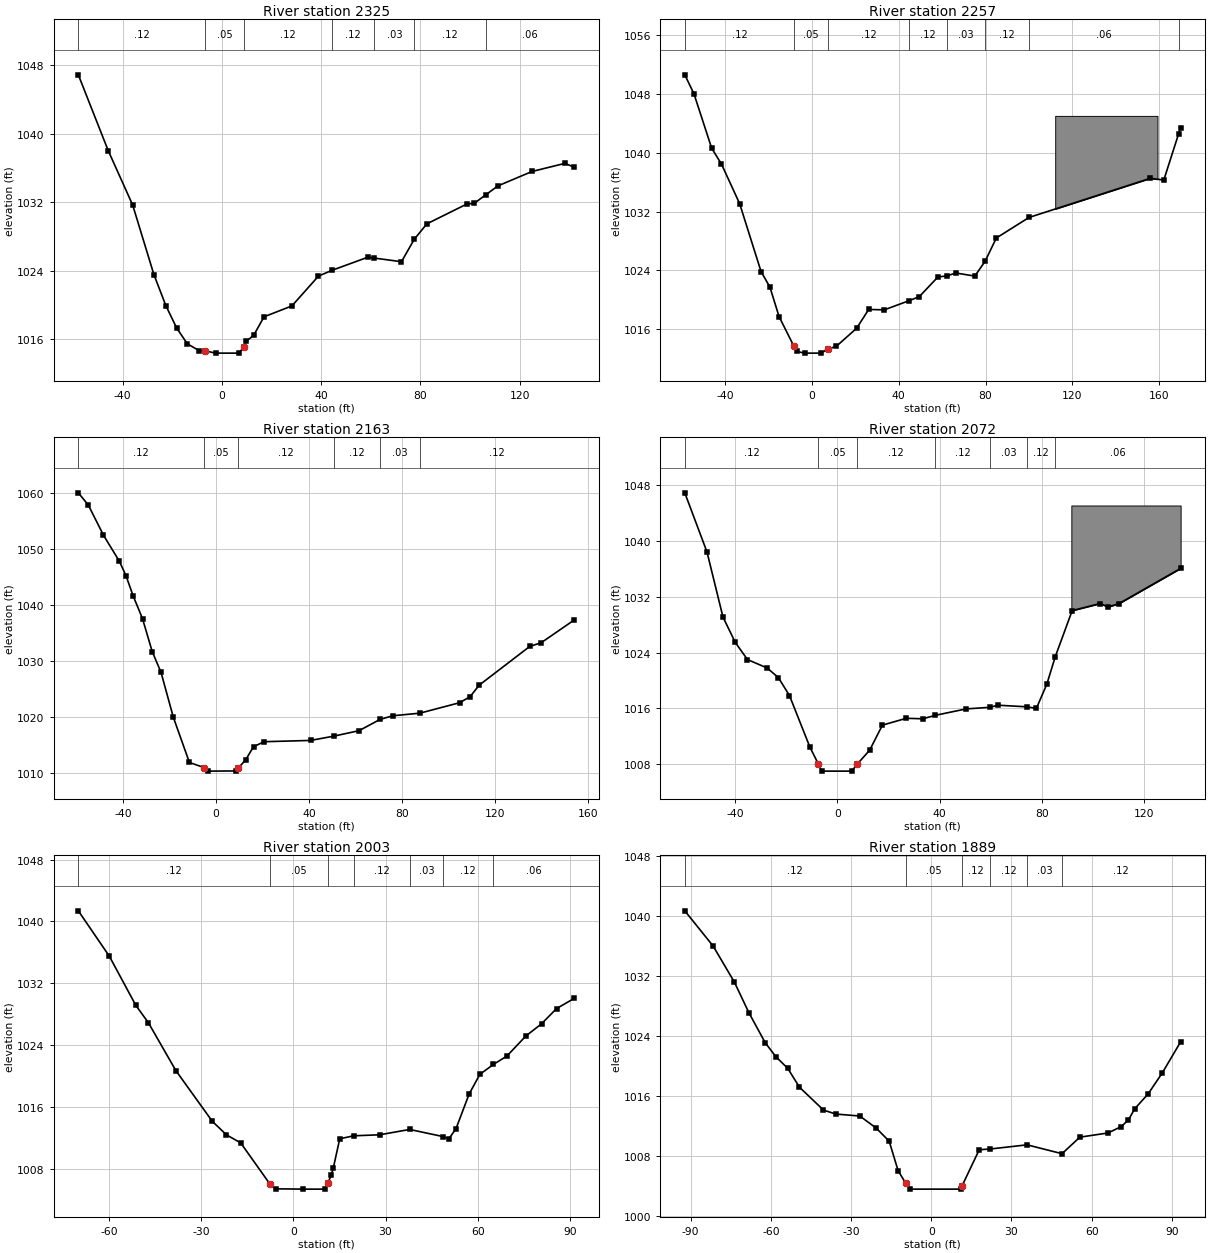
Type RM Length L Ch R = 1 ,2325    ,68.69,68,67.29
XS GIS Cut Line= 3
579456.3771262834370496.61399483579453.6272206494370534.29398089
579452.5671262364370557.36398838
#Sta/Elev= 30
 -57.808 1046.88 -45.768 1038.03 -35.925 1031.69 -27.362 1023.56 -22.507 1019.91
 -18.176 1017.32 -13.911 1015.49  -9.219  1014.7  -6.693 1014.67  -2.559  1014.4
   6.988  1014.4     8.8 1015.16   9.908 1015.81  12.795 1016.47  16.995 1018.64
  28.215 1019.91  38.911 1023.39  44.226 1024.05   58.76 1025.59   61.45 1025.49
  72.343 1025.07  77.493 1027.69  82.579 1029.49  98.589 1031.79 101.673 1031.89
 106.266 1032.87 111.188 1033.92 124.934  1035.6 138.222 1036.55 141.896 1036.09
#Mann= 7 ,-1 , 0
 -57.808     .12       0  -6.693     .05       0     8.8     .12       0
  44.226     .12       0   61.45     .03       0  77.493     .12       0
 106.266     .06       0
Bank Sta=-6.693,8.8
XS Rating Curve= 0 ,0
Exp/Cntr=0.3,0.1

Type RM Length L Ch R = 1 ,2257    ,94.38,94,93.52
XS GIS Cut Line= 2
579434.3772716114370495.51397162579434.3772716114370565.09402127
#Sta/Elev= 30
 -58.497 1050.59 -54.265    1048 -46.129 1040.62 -41.601 1038.45 -33.235 1033.07
 -23.392 1023.85 -19.291 1021.72 -15.092 1017.72  -8.235 1013.68  -6.955 1012.99
  -3.314 1012.76   4.199 1012.76   7.644 1013.35  11.253 1013.68  20.604 1016.14
  26.181  1018.7  33.333 1018.64  44.685 1019.88  49.475 1020.44  58.005  1023.1
  62.139 1023.26  66.339 1023.65  75.033 1023.23   79.79 1025.26  84.941 1028.41
  99.967  1031.2 155.807 1036.52 162.041 1036.29 168.832 1042.55 169.783 1043.41
#Mann= 8 ,-1 , 0
 -58.497     .12       0  -8.235     .05       0   7.644     .12       0
  44.685     .12       0  62.139     .03       0   79.79     .12       0
  99.967     .06       0 168.832     .12       0
#Block Obstruct= 1 ,-1
 112.041 159.121 1045.01
Bank Sta=-8.235,7.644
XS Rating Curve= 0 ,0
Exp/Cntr=0.3,0.1

Type RM Length L Ch R = 1 ,2163    ,91.78,91,89.81
XS GIS Cut Line= 3
579404.877203246 4370493.9241348579407.1272368744370536.65404732
579406.207045663 4370558.8739676
#Sta/Elev= 30
 -59.318 1059.97  -55.02 1057.78 -48.491  1052.4 -41.634 1047.74 -38.845 1045.21
 -35.696 1041.54 -31.693  1037.5 -27.526 1031.63 -23.753 1027.95 -18.438 1019.91
 -11.516 1011.84  -5.151 1010.93  -3.412  1010.3   8.333 1010.33    9.38 1010.79
  12.664  1012.3  16.076 1014.67  20.669 1015.55   40.65 1015.78  50.558 1016.54
  61.483 1017.52  70.472 1019.52  75.919 1020.18  87.598 1020.64 104.757 1022.51
 109.252 1023.59 113.222 1025.66 134.908 1032.55 139.895 1033.23 154.035 1037.27
#Mann= 6 ,-1 , 0
 -59.318     .12       0  -5.151     .05       0    9.38     .12       0
  50.558     .12       0  70.472     .03       0  87.598     .12       0
Bank Sta=-5.151,9.38
XS Rating Curve= 0 ,0
Exp/Cntr=0.3,0.1

Type RM Length L Ch R = 1 ,2072    ,67.05,69,70.77
XS GIS Cut Line= 3
 579375.247290084370497.75394684579381.5971885594370534.27386409
579378.4172101194370556.09388676
#Sta/Elev= 30
 -59.646 1046.82 -50.951 1038.35 -44.718 1029.07 -39.928 1025.46 -35.138    1023
 -27.395 1021.78 -23.031 1020.41 -18.701 1017.85 -10.696 1010.47    -7.5 1008.14
  -6.102 1007.05   5.676 1007.05    7.71 1008.01  12.664 1010.04  17.651 1013.62
  27.001  1014.6  33.465 1014.53  38.419 1015.03  50.394 1015.94  59.711 1016.17
  62.861 1016.47  74.213 1016.24  77.887 1016.01  81.988 1019.49  85.269 1023.39
  91.896 1029.99 102.789    1031 105.971 1030.51 110.236    1031 134.318 1036.02
#Mann= 7 ,-1 , 0
 -59.646     .12       0    -7.5     .05       0    7.71     .12       0
  38.419     .12       0  59.711     .03       0  74.213     .12       0
  85.269     .06       0
#Block Obstruct= 1 ,-1
  91.568 134.318 1045.01
Bank Sta=-7.5,7.71
XS Rating Curve= 0 ,0
Exp/Cntr=0.3,0.1

Type RM Length L Ch R = 1 ,2003    ,113.71,114,114.15
XS GIS Cut Line= 2
579358.0370626684370498.15414925579357.3771706594370547.36410986
#Sta/Elev= 30
 -70.046 1041.37 -59.941  1035.5 -51.345 1029.17 -47.211  1026.9 -38.287 1020.73
 -26.411 1014.17 -21.818 1012.43 -17.159 1011.38    -7.6 1006.04  -5.807 1005.45
   3.248 1005.41  10.367 1005.41  11.122 1006.14  12.303 1007.18  13.025  1008.2
  15.092 1011.91  19.587  1012.3  28.084 1012.43  37.861 1013.12  48.753  1012.2
  50.623 1011.91  52.953 1013.22  57.251 1017.72  60.728 1020.24  65.125 1021.52
  69.521  1022.6  75.722  1025.2  80.807 1026.77  85.696 1028.74  91.437 1030.05
#Mann= 7 ,-1 , 0
 -70.046     .12       0    -7.6     .05       0  11.122     .12       0
  19.587     .12       0  37.861     .03       0  48.753     .12       0
  65.125     .06       0
Bank Sta=-7.6,11.122
XS Rating Curve= 0 ,0
Exp/Cntr=0.3,0.1

Type RM Length L Ch R = 1 ,1889    ,83.38,83,82.67
XS GIS Cut Line= 2
579324.3072846514370488.10397872579322.0572510234370544.58402902
#Sta/Elev= 30
 -92.192 1040.65 -81.594 1035.96 -73.622 1031.14 -68.209 1027.07 -62.139  1023.1
 -58.169 1021.23 -53.707 1019.68 -49.311 1017.16 -40.322 1014.11 -35.728 1013.58
 -26.739 1013.32 -20.604 1011.71 -15.748 1009.97 -12.402 1006.04    -9.5 1004.33
  -7.874 1003.58  10.991 1003.58    11.5    1004  17.946 1008.83  21.949 1008.92
  35.827 1009.48  48.917  1008.3  55.577  1010.5  66.109 1011.06  71.063 1011.91
  73.753  1012.8  76.083 1014.27   81.07 1016.24  86.417 1019.06  93.274  1023.2
#Mann= 6 ,-1 , 0
 -92.192     .12       0    -9.5     .05       0    11.5     .12       0
  21.949     .12       0  35.827     .03       0  48.917     .12       0
Bank Sta=-9.5,11.5
XS Rating Curve= 0 ,0
Exp/Cntr=0.3,0.1

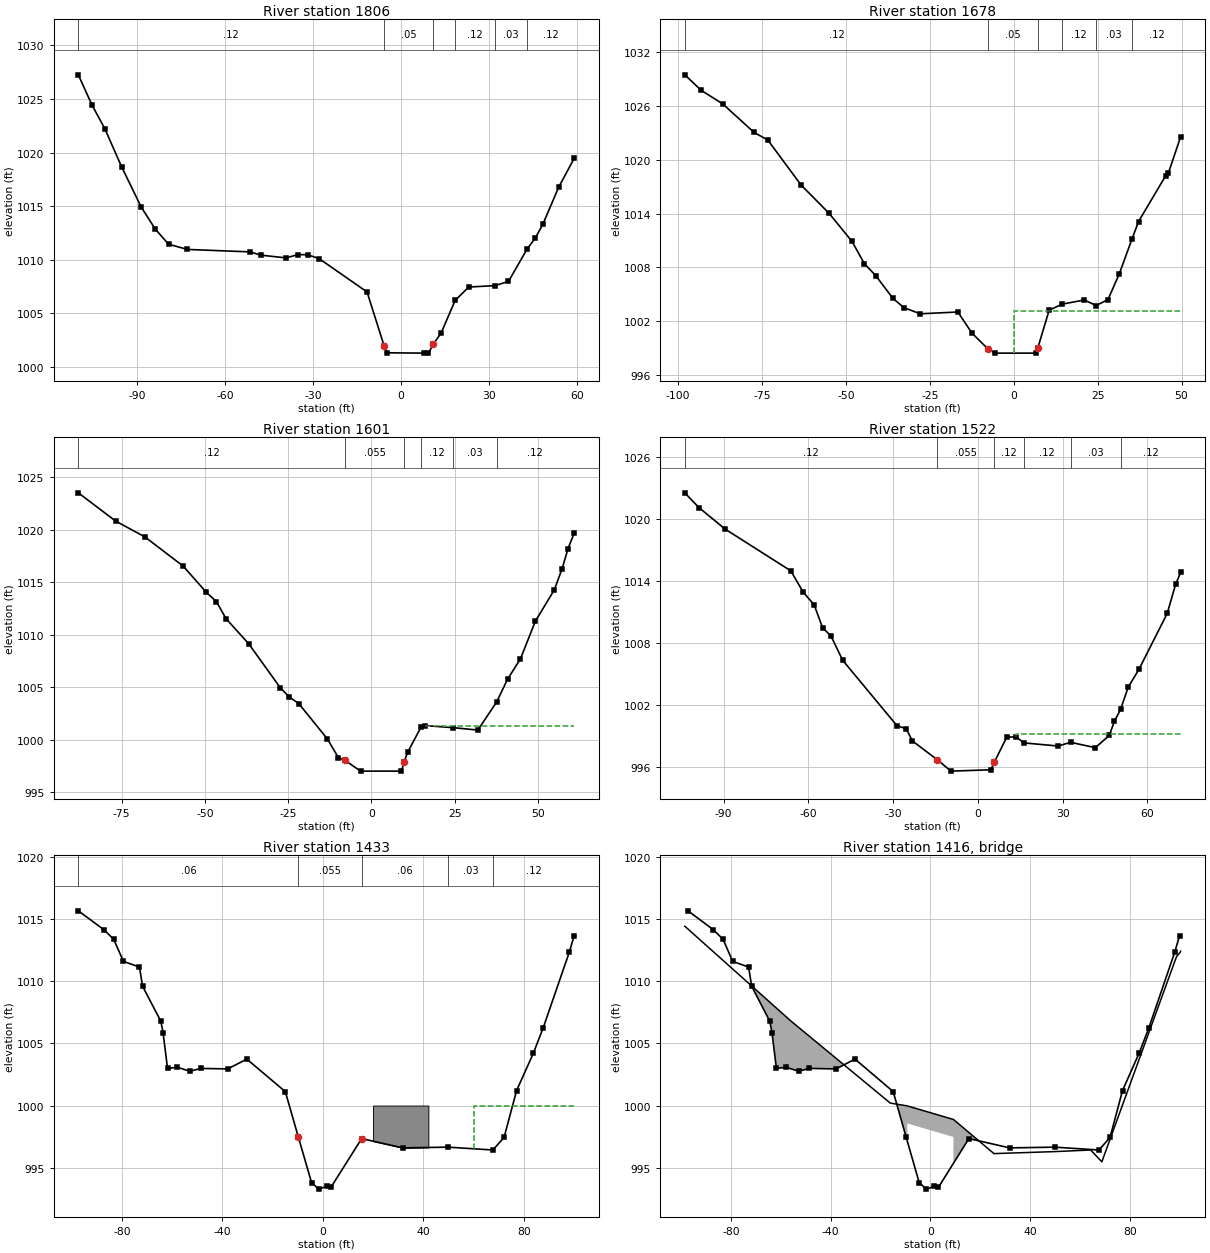
Type RM Length L Ch R = 1 ,1806    ,124.21,128,131.18
XS GIS Cut Line= 3
579307.8971572484370487.30387871579298.2371307284370508.60391258
579298.1072859274370536.78389212
#Sta/Elev= 30
-110.105 1027.26-105.446 1024.44-101.083 1022.24 -95.276 1018.64 -88.681 1014.93
 -83.858 1012.86 -79.331 1011.45   -72.9 1010.96 -51.444 1010.73 -47.933 1010.43
 -39.206 1010.17 -35.269 1010.47  -31.89 1010.47  -27.92  1010.1 -11.581 1006.99
  -5.741 1001.94  -4.757 1001.31   7.874 1001.28   9.383 1001.28  10.991  1002.1
  13.681 1003.15  18.471  1006.2   23.13 1007.45  31.955 1007.58   36.68 1007.97
  43.012 1010.99  45.866 1012.04  48.425 1013.32  53.806 1016.77  59.088 1019.46
#Mann= 6 ,-1 , 0
-110.105     .12       0  -5.741     .05       0  10.991     .12       0
  18.471     .12       0  31.955     .03       0  43.012     .12       0
Bank Sta=-5.741,10.991
XS Rating Curve= 0 ,0
Exp/Cntr=0.3,0.1

Type RM Length L Ch R = 1 ,1678    ,76.55,77,77.35
XS GIS Cut Line= 2
579273.6470856254370483.73406107579254.1971877844370524.35414797
#Sta/Elev= 30
 -97.999 1029.49  -93.11 1027.76 -86.713 1026.25 -77.362 1023.06 -73.261 1022.21
 -63.353 1017.19  -55.02 1014.04 -48.163 1010.89 -44.521 1008.43 -41.142 1007.09
 -35.958 1004.53  -32.71 1003.51 -27.854 1002.82 -16.634 1003.02 -12.434 1000.66
  -7.546  998.85  -5.512  998.43    6.66  998.43   7.218  999.05  10.564 1003.22
  14.469  1003.9  21.063 1004.36  24.541 1003.74  28.084  1004.4  31.463 1007.28
  35.302 1011.22  37.205 1013.12  45.308 1018.24  46.063  1018.5  49.738 1022.57
#Mann= 6 ,-1 , 0
 -97.999     .12       0  -7.546     .05       0   7.218     .12       0
  14.469     .12       0  24.541     .03       0  35.302     .12       0
#XS Ineff= 2 , 0
       0  -21.92 1003.08               0
Permanent Ineff=
       F       F
Bank Sta=-7.546,7.218
XS Rating Curve= 0 ,0
Exp/Cntr=0.3,0.1

Type RM Length L Ch R = 1 ,1601    ,78.99,79,78.94
XS GIS Cut Line= 2
579252.5372469644370475.87387857579231.1570506994370515.87400227
#Sta/Elev= 30
 -87.992 1023.52 -76.804 1020.83 -68.012 1019.32 -56.529 1016.54 -49.573 1014.04
 -46.555 1013.16 -43.635 1011.52 -36.877 1009.15 -27.362 1004.95  -24.77  1004.1
 -21.818 1003.44 -13.222 1000.07  -9.941  998.29  -7.907  998.03  -3.281  997.01
    8.99  997.01   9.777  997.87   10.86  998.82  14.829 1001.18  15.978 1001.35
  24.541 1001.15  31.923 1000.92  37.533 1003.58  40.846 1005.77  44.718 1007.71
   49.18 1011.29  54.856 1014.27  57.185 1016.27  58.989 1018.21  60.827 1019.68
#Mann= 6 ,-1 , 0
 -87.992     .12       0  -7.907    .055       0   9.777     .12       0
  14.829     .12       0  24.541     .03       0  37.533     .12       0
#XS Ineff= 2 , 0
       0                   15.98       0 1001.35
Permanent Ineff=
       F       F
Bank Sta=-7.907,9.777
XS Rating Curve= 0 ,0
Exp/Cntr=0.3,0.1

Type RM Length L Ch R = 1 ,1522    ,92.57,89,85.57
XS GIS Cut Line= 3
579233.027303523 4370461.6439856  579215.03709294370495.64412122
579213.717308884 4370510.5939518
#Sta/Elev= 30
-103.707 1022.54 -98.655  1021.1 -89.436 1019.03 -66.207 1014.99 -61.811 1012.93
 -57.907 1011.68 -54.954 1009.48 -52.001 1008.69 -47.835 1006.33 -28.642    1000
 -25.361   999.7 -23.163  998.52 -14.304  996.69  -9.514   995.6    4.56  995.73
   5.873  996.49  10.203  998.88  13.484  998.92  16.339  998.33  28.445  998.03
  32.808  998.39  41.568  997.87   46.49  999.05  48.327 1000.43  50.492 1001.57
  53.182 1003.71  57.054 1005.48  66.995 1010.86   69.98 1013.68  71.752 1014.83
#Mann= 6 ,-1 , 0
-103.707     .12       0 -14.304    .055       0   5.873     .12       0
  16.339     .12       0  32.808     .03       0  50.492     .12       0
#XS Ineff= 1 ,-1
   13.48  71.752   999.2
Permanent Ineff=
       F
Bank Sta=-14.304,5.873
XS Rating Curve= 0 ,0
Exp/Cntr=0.5,0.3

Type RM Length L Ch R = 1 ,1433    ,33.462,34,33.301
BEGIN DESCRIPTION:
US of Private bridge (Surveyed XS REU_06)
END DESCRIPTION:
XS GIS Cut Line= 3
579199.0171095024370449.69399665 579193.177141434370479.10414901
579190.4272357964370509.14401818
#Sta/Elev= 30
  -97.31 1015.68 -87.205 1014.17 -83.235 1013.39 -79.364 1011.61 -72.966 1011.15
 -71.752 1009.61 -64.469 1006.79 -63.583 1005.87 -61.811 1002.99 -57.841 1003.08
 -52.887 1002.76 -48.622 1002.99 -37.861 1002.95 -30.249 1003.74 -14.928 1001.12
   -9.75  997.47  -4.495   993.8  -1.608  993.27   1.608   993.5   3.215  993.41
  15.453  997.34  31.857  996.59  49.869  996.65  67.684  996.42  72.146  997.44
  77.133 1001.21  83.825 1004.23   87.73 1006.27   98.13 1012.37 100.033 1013.68
#Mann= 5 ,-1 , 0
  -97.31     .06       0   -9.75    .055       0  15.453     .06       0
  49.869     .03       0  67.684     .12       0
#XS Ineff= 2 , 0
       0                      60       0    1000
Permanent Ineff=
       F       F
#Block Obstruct= 1 ,-1
      20      42    1000
Bank Sta=-9.75,15.453
XS Rating Curve= 0 ,0
Exp/Cntr=0.5,0.3

Type RM Length L Ch R = 3 ,1416    ,,,
BEGIN DESCRIPTION:
Private bridge (Surveyed Structure REU_06)
END DESCRIPTION:
Bridge Culvert--1,0,-1,-1, 0
Deck Dist Width WeirC Skew NumUp NumDn MinLoCord MaxHiCord MaxSubmerge Is_Ogee
12,8.4,2.61,0, 12, 12, , , 0.98, 0, 0,0,,
 -98.589  -56.07 -16.109   -9.25    9.25  25.525  49.738  64.337  68.832  98.786
 100.361 100.459
 1014.44 1006.82  1000.2  999.97  998.88  996.13  996.29  996.42  995.47 1011.98
 1012.37 1012.43
                          998.56  997.47
                
 -98.589  -56.07 -16.109   -9.25    9.25  25.525  49.738  64.337  68.832  98.786
 100.361 100.459
 1014.44 1006.82  1000.2  999.97  998.88  996.13  996.29  996.42  995.47 1011.98
 1012.37 1012.43
                          998.56  997.47
                
BR Coef=-1 , 1 , 0 ,, 0 ,,,0.8,0,1.2,0,
WSPro=,,,, 1 ,,,, 0 ,,,, 0 ,,,,-1 ,-1 ,-1 , 0 , 0 , 0 , 0 , 0
BC Design=,, 0 ,, 0 ,,,,,,
BC Use User HTab Curves=0
BC User HTab FreeFlow(D)= 0

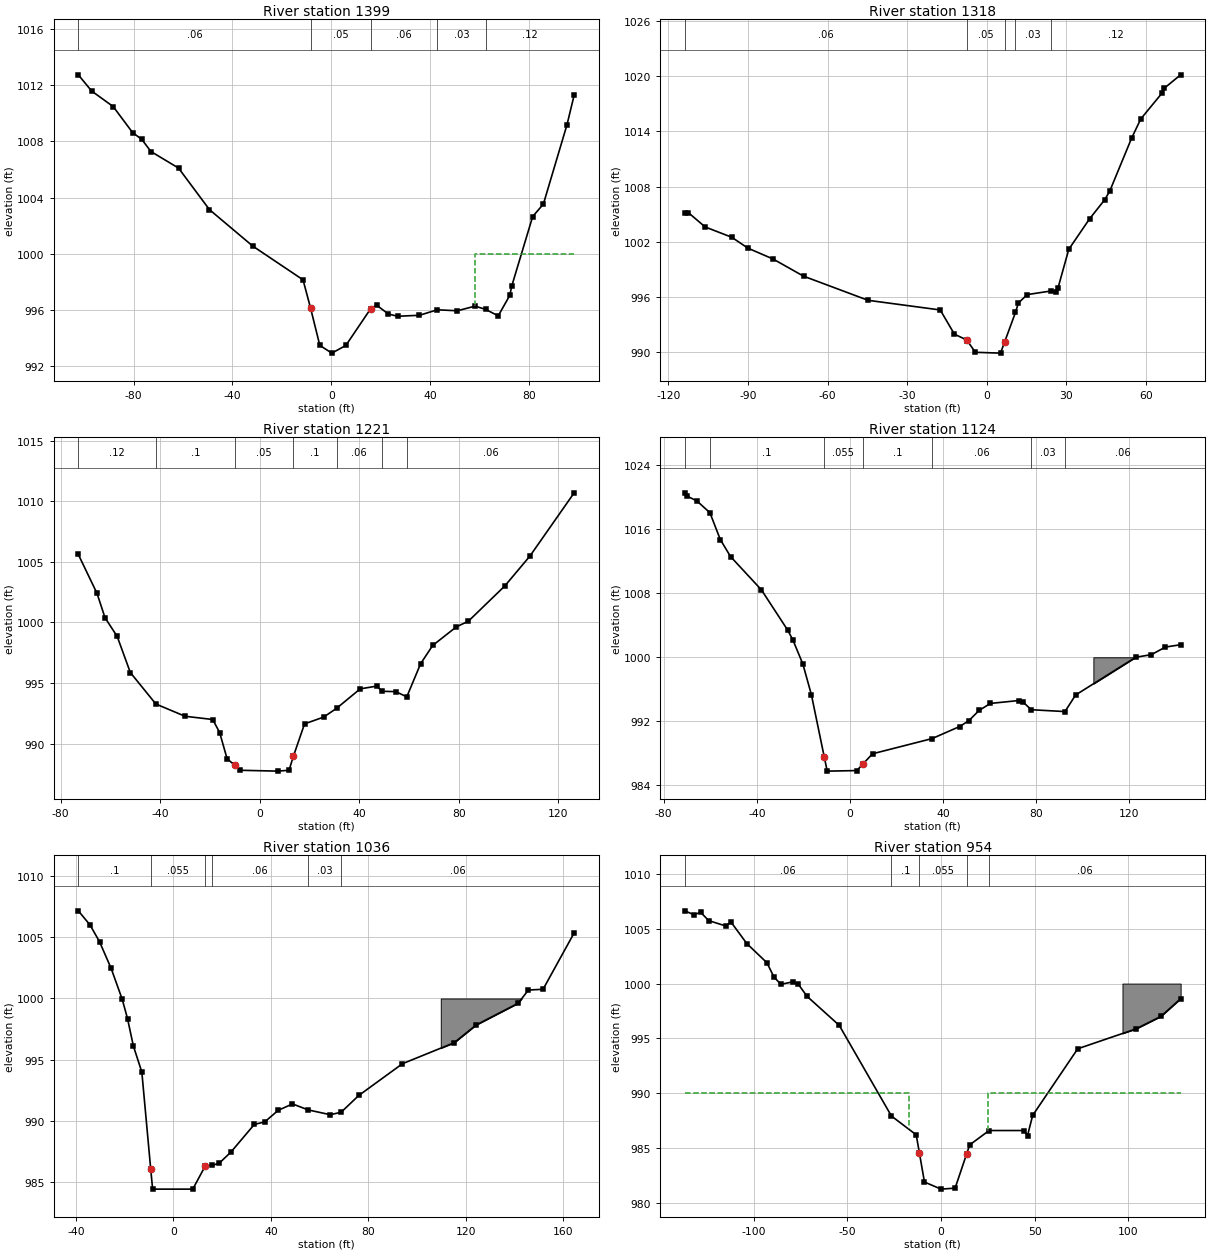
Type RM Length L Ch R = 1 ,1399    ,75.17,81,83.97
BEGIN DESCRIPTION:
DS of Private bridge (Channel from survey data REU_06)
END DESCRIPTION:
XS GIS Cut Line= 3
579189.2071213814370447.74388622579183.2671789084370477.67402739
579180.4672860734370508.22413177
#Sta/Elev= 30
-102.395 1012.73 -97.014 1011.58 -88.255 1010.47 -80.446 1008.63 -76.706 1008.14
 -72.999 1007.28 -61.811  1006.1 -49.311 1003.15 -31.791 1000.56 -11.417  998.16
   -8.38  996.16  -4.626   993.5    .262  992.95   5.938   993.5  15.945   996.1
  18.373  996.36   23.13  995.73  26.936  995.57  35.728  995.64  42.946  996.03
  51.083  995.96  58.235  996.29    62.5  996.06  67.618   995.6  72.277  997.05
   73.13  997.74  81.562 1002.66  85.892 1003.54  95.472 1009.19   98.36 1011.29
#Mann= 5 ,-1 , 0
-102.395     .06       0   -8.38     .05       0  15.945     .06       0
  42.946     .03       0    62.5     .12       0
#XS Ineff= 2 , 0
       0                   58.24       0    1000
Permanent Ineff=
       F       F
Bank Sta=-8.38,15.945
XS Rating Curve= 0 ,0
Exp/Cntr=0.5,0.3

Type RM Length L Ch R = 1 ,1318    ,97.07,97,96.22
XS GIS Cut Line= 2
579177.1672164324370451.73402307579147.3272960634370500.30390367
#Sta/Elev= 30
-113.845 1005.18-112.566 1005.18-106.168 1003.61 -96.129 1002.49 -90.059 1001.31
 -80.577 1000.13 -69.029  998.26 -44.718  995.64 -17.487  994.59 -12.139  991.96
  -7.349  991.31  -7.349  991.27  -4.232  989.99   5.249   989.9     6.8  991.11
  10.892  994.32  11.975  995.34  15.322  996.26  24.245  996.65  26.214  996.52
  26.969  997.01  31.004 1001.18  38.845 1004.49  44.619 1006.59  46.522 1007.55
  54.692 1013.25  58.169 1015.35  66.142 1018.14  67.093  1018.7  73.196 1020.14
#Mann= 5 ,-1 , 0
-113.845     .06       0  -7.349     .05       0     6.8     .06       0
  10.892     .03       0  24.245     .12       0
Bank Sta=-7.349,6.8
XS Rating Curve= 0 ,0
Exp/Cntr=0.3,0.1

Type RM Length L Ch R = 1 ,1221    ,104.81,97,90.95
XS GIS Cut Line= 3
579148.6272680794370442.45408216579129.7071126464370474.47393215
579130.7672070594370498.02399965
#Sta/Elev= 30
 -72.933 1005.61  -65.42  1002.4 -62.205 1000.39 -57.316  998.85 -52.034  995.87
 -41.765  993.27 -30.052  992.26 -18.898  991.99 -16.109  990.91 -13.123  988.75
 -10.039  988.22  -7.776   987.8   7.251  987.73  11.778   987.8    13.5  988.94
  18.012  991.63  25.689  992.19  30.873  992.91  40.387  994.52  47.146  994.75
  49.049  994.32  54.724  994.29  59.121  993.86  64.665  996.59  69.521   998.1
  79.068  999.64  83.858  1000.1  98.556 1003.02 108.629 1005.48 126.411  1010.7
#Mann= 7 ,-1 , 0
 -72.933     .12       0 -41.765      .1       0 -10.039     .05       0
    13.5      .1       0  30.873     .06       0  49.049     .03       0
  59.121     .06       0
Bank Sta=-10.039,13.5
XS Rating Curve= 0 ,0
Exp/Cntr=0.3,0.1

Type RM Length L Ch R = 1 ,1124    ,90.81,88,85.96
XS GIS Cut Line= 2
579105.177113142 4370429.8341428579122.3172365544370492.49401318
#Sta/Elev= 30
 -70.965 1020.57 -69.849 1020.14 -65.748 1019.55 -60.171 1018.08 -55.709 1014.73
 -51.312  1012.6 -38.025 1008.43 -26.772 1003.41 -24.508 1002.17  -20.21  999.15
 -16.568  995.34     -11   987.5  -9.744  985.76   2.986  985.83   5.446  986.61
   9.744  987.93  35.335  989.83  47.178  991.34  51.083  992.06   55.61  993.37
  60.433  994.23  72.638  994.59  74.344  994.42  77.953  993.44  92.454  993.21
  97.014  995.28 122.835    1000 129.593 1000.33  135.63 1001.28 142.159 1001.57
#Mann= 7 ,-1 , 0
 -70.965     .12       0 -60.171      .1       0     -11    .055       0
   5.446      .1       0  35.335     .06       0  77.953     .03       0
  92.454     .06       0
#Block Obstruct= 1 ,-1
 104.659 135.531    1000
Bank Sta=-11,5.446
XS Rating Curve= 0 ,0
Exp/Cntr=0.3,0.1

Type RM Length L Ch R = 1 ,1036    ,82.73,82,80.81
XS GIS Cut Line= 3
579080.4971520374370452.11410868579095.5771322244370476.85411538
579109.5970179974370506.75408135
#Sta/Elev= 30
 -39.009 1007.15 -34.219    1006 -30.315 1004.63 -25.558 1002.46 -20.997  999.93
 -18.832  998.36 -16.437  996.13 -12.959     994  -9.318  986.09   -8.53  984.45
    7.94  984.45  13.091  986.35  15.945  986.38  18.865  986.58  23.589  987.47
  33.202  989.73  37.434  989.93  43.012  990.88  48.852   991.4  55.315  990.91
  64.337  990.52  68.799  990.72   76.05  992.09  93.963  994.68 115.157  996.39
 124.114  997.83 141.404  999.61 145.636 1000.69  151.64 1000.75 164.403 1005.35
#Mann= 6 ,-1 , 0
 -39.009      .1       0  -9.318    .055       0  13.091     .11       0
  15.945     .06       0  55.315     .03       0  68.799     .06       0
#Block Obstruct= 1 ,-1
 109.678 150.426    1000
Bank Sta=-9.318,13.091
XS Rating Curve= 0 ,0
Exp/Cntr=0.5,0.3

Type RM Length L Ch R = 1 ,954     ,37.593,39,38.73
BEGIN DESCRIPTION:
US of Private road (Surveyed XS REU_05)
END DESCRIPTION:
XS GIS Cut Line= 4
579042.1770859644370444.34414698579064.6670590424370474.44406175
579071.8972199314370483.94406827579085.8271897034370511.81406622
#Sta/Elev= 30
-136.745 1006.63-131.857 1006.27-128.314  1006.5-123.983 1005.74-114.895 1005.25
-112.106 1005.61-103.609 1003.64 -92.913  1001.9  -89.14 1000.59   -85.4  999.93
 -79.101 1000.16 -76.083  999.93 -71.555  998.85 -54.298  996.19 -26.444  987.93
 -13.222  986.22   -11.5  984.55  -8.825  981.92       0  981.27   7.546  981.36
    13.7  984.48  15.322   985.3  25.689  986.61  44.455  986.61  46.194  986.15
   48.95  987.99  72.999  994.06 104.068  995.87 117.388  997.01  127.92  998.62
#Mann= 5 ,-1 , 0
-136.745     .06       0 -26.444      .1       0   -11.5    .055       0
    13.7      .1       0  25.689     .06       0
#XS Ineff= 2 ,-1
-136.745   -17.2     990      25  127.92     990
Permanent Ineff=
       F       F
#Block Obstruct= 1 ,-1
  96.883  127.92    1000
Bank Sta=-11.5,13.7
XS Rating Curve= 0 ,0
Exp/Cntr=0.5,0.3