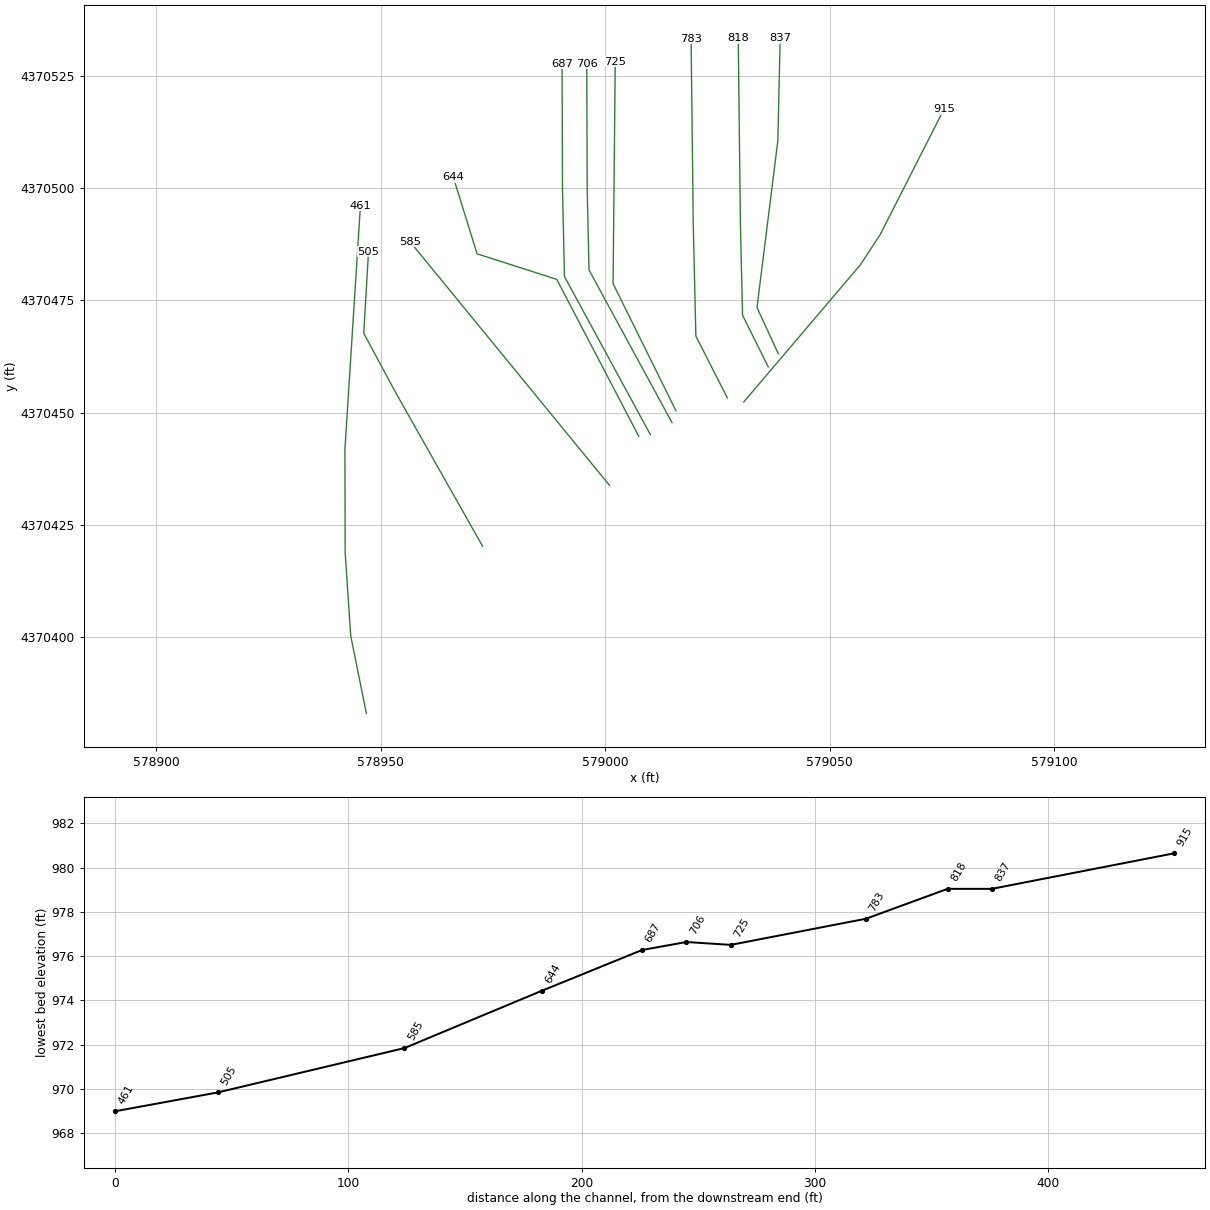
HEC-RAS study Reuben_Run.prj: Reuben Run

--- Reuben_Run.g01 (geometry) --- (continued)

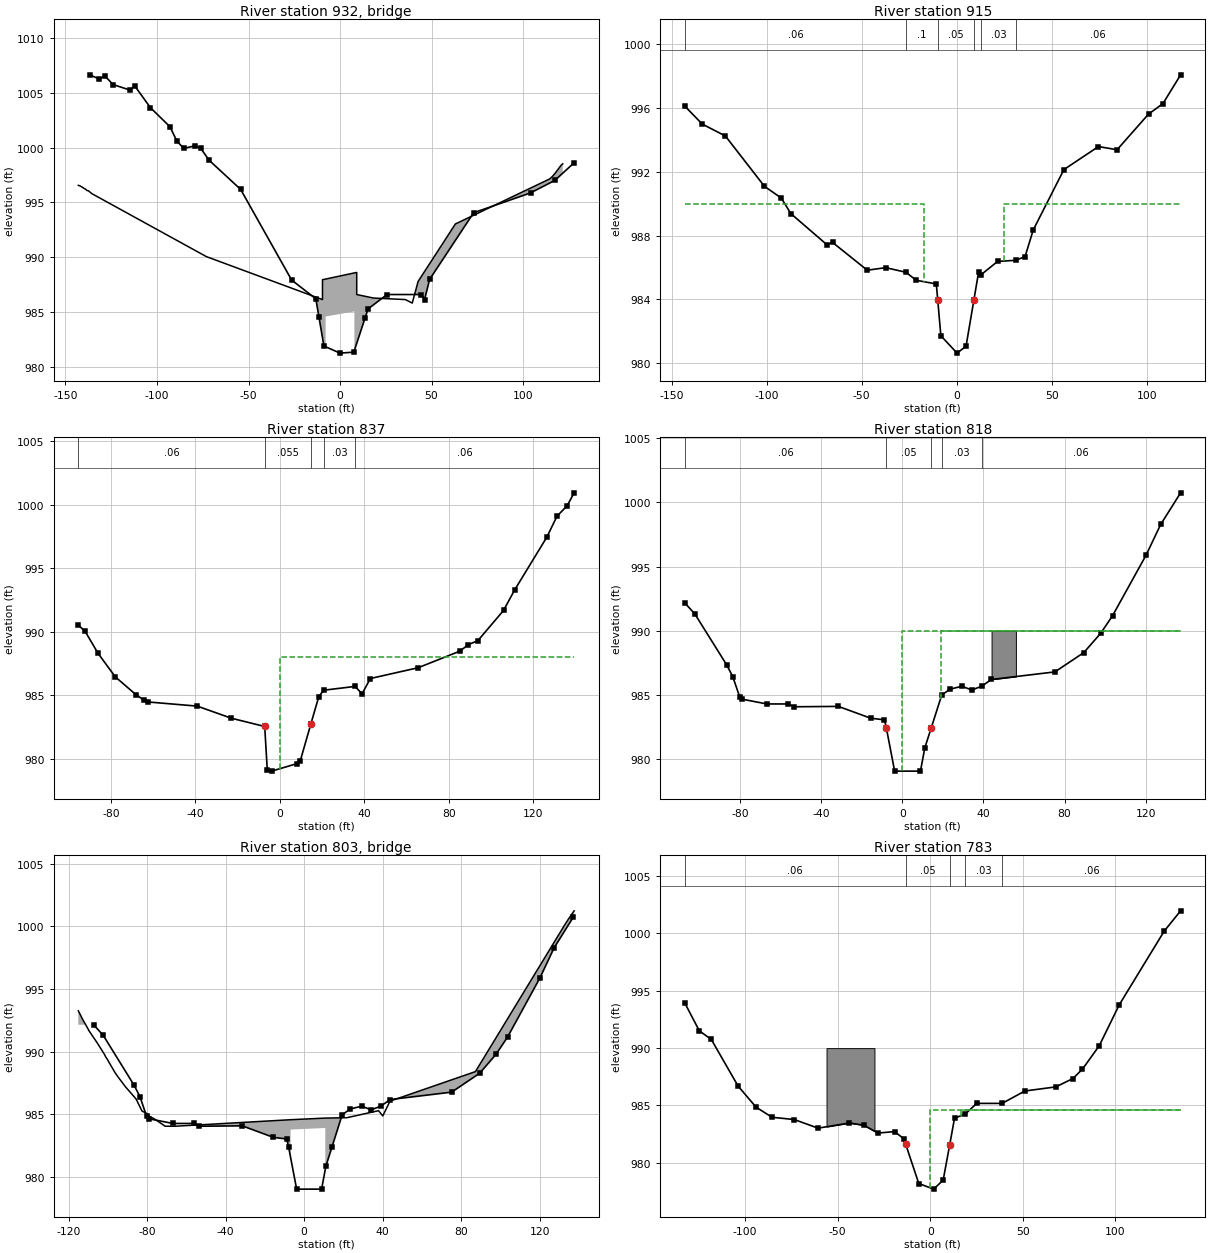
Type RM Length L Ch R = 3 ,932     ,,,
BEGIN DESCRIPTION:
Private road (Surveyed Structure REU_05)
END DESCRIPTION:
Bridge Culvert--1,0,-1,-1, 0
Deck Dist Width WeirC Skew NumUp NumDn MinLoCord MaxHiCord MaxSubmerge Is_Ogee
15.5,11.8,2.61,0, 25, 25, , , 0.98, 0, 0,0,,
-142.979-141.831-138.911-138.353-137.467-135.564 -72.966   -9.59   -9.58   -7.86
   -7.85    7.85    7.86   9.121    9.13  18.274  35.728  39.469  42.651  63.025
 114.633 116.076 117.552 120.768 121.686
  996.56  996.49  996.19   996.1  996.06   995.8  990.06  986.15  987.96  988.02
  988.02  988.58  988.58  988.62  986.61  986.29  986.15  985.83   987.8  993.04
  997.15  997.38  997.67  998.39  998.52
                                                                                
  984.61  985.07
                                        
-142.979-141.831-138.911-138.353-137.467-135.564 -72.966   -9.59   -9.58   -7.86
   -7.85    7.85    7.86   9.121    9.13  18.274  35.728  39.469  42.651  63.025
 114.633 116.076 117.552 120.768 121.686
  996.56  996.49  996.19   996.1  996.06   995.8  990.06  986.15  987.96  988.02
  988.02  988.58  988.58  988.62  986.61  986.29  986.15  985.83   987.8  993.04
  997.15  997.38  997.67  998.39  998.52
                                                                                
  984.61  985.07
                                        
BR Coef=-1 , 1 , 0 ,, 0 ,,,0.8,0,1.2,0,
WSPro=,,,, 1 ,,,, 0 ,,,, 0 ,,,,-1 ,-1 ,-1 , 0 , 0 , 0 , 0 , 0
BC Design=,, 0 ,, 0 ,,,,,,
BC Use User HTab Curves=0
BC User HTab FreeFlow(D)= 0

Type RM Length L Ch R = 1 ,915     ,73.2,78,81.94
BEGIN DESCRIPTION:
DS of Private road (Channel from survey data REU_05)
END DESCRIPTION:
XS GIS Cut Line= 4
579030.8470602244370452.38416148579056.8272981454370482.93396106
  579061.27707344370489.74410754579075.4371671754370517.60404709
#Sta/Elev= 30
-143.045   996.1-133.891  994.98-121.686  994.23-101.148  991.08 -92.323  990.35
 -87.238  989.37  -68.34  987.43 -65.322  987.57  -47.08  985.83 -37.336  985.99
 -26.706   985.7 -21.358   985.2 -10.761  984.97     -10  983.96  -8.366  981.73
    .164  980.64   4.888  981.07       9  983.96  11.516  985.73  12.927  985.56
   21.49  986.38  30.938  986.45  35.925  986.68  40.223  988.35  56.365  992.13
  74.541  993.57  84.318  993.37 100.853   995.6 108.465  996.26 117.749  998.06
#Mann= 6 ,-1 , 0
-143.045     .06       0 -26.706      .1       0     -10     .05       0
       9      .1       0  12.927     .03       0  30.938     .06       0
#XS Ineff= 2 ,-1
-143.045   -17.2     990      25 117.749     990
Permanent Ineff=
       F       F
Bank Sta=-10,9
XS Rating Curve= 0 ,0
Exp/Cntr=0.5,0.3

Type RM Length L Ch R = 1 ,837     ,17.93,19,20.81
BEGIN DESCRIPTION:
(Surveyed XS REU_04)
END DESCRIPTION:
XS GIS Cut Line= 4
579038.5572811194370463.09391921 579033.797219464370473.41414254
579038.437189918 4370510.5140942579038.9571787244370533.34391928
#Sta/Elev= 30
 -95.472  990.52 -92.257  990.03 -86.089  988.29 -77.953  986.45  -68.11  985.04
 -64.239  984.61 -62.598  984.48 -39.108  984.15 -22.999   983.2  -7.185  982.55
  -5.971  979.13  -3.937  979.04   8.136  979.63   9.678  979.86   14.73  982.78
  18.406  984.88  20.702   985.4  35.663   985.7  38.911  985.11  42.848  986.32
  65.518  987.17  85.367  988.48  89.206  988.98  93.799   989.3 105.938  991.67
 111.155  993.27 126.476  997.44 131.266  999.08 136.056   999.9 139.403 1000.92
#Mann= 5 ,-1 , 0
 -95.472     .06       0  -7.185    .055       0   14.73     .06       0
  20.702     .03       0  35.663     .06       0
#XS Ineff= 2 , 0
       0     -17     988               0
Permanent Ineff=
       F       F
Bank Sta=-7.185,14.73
XS Rating Curve= 0 ,0
Exp/Cntr=0.5,0.3

Type RM Length L Ch R = 1 ,818     ,34.51,35,34.469
BEGIN DESCRIPTION:
US of Driveway
END DESCRIPTION:
XS GIS Cut Line= 4
579036.3072474914370460.18399358 579030.577007424370471.70390972
579030.1070058154370492.08405717579029.6272506094370533.33416568
#Sta/Elev= 30
-107.218  992.16-102.297  991.31 -86.614  987.34 -83.596  986.42 -80.184  984.84
 -78.904  984.65 -66.765  984.28 -56.102  984.28 -53.609  984.06 -31.496  984.09
 -15.617  983.17  -8.793  983.04   -7.87  982.41  -3.773  979.04   8.957  979.04
  11.122  980.87    14.2  982.38  19.423  984.97  23.491  985.43  29.331  985.66
  34.219  985.37  39.108  985.66   43.93  986.19   75.23  986.78  89.501  988.29
  97.835   989.8 103.675  991.17  120.21   995.9 127.395  998.29 137.205 1000.75
#Mann= 5 ,-1 , 0
-107.218     .06       0   -7.87     .05       0    14.2     .06       0
  19.423     .03       0  39.108     .06       0
#XS Ineff= 2 , 0
       0  -14.85     990   18.85       0     990
Permanent Ineff=
       F       F
#Block Obstruct= 1 ,-1
      44      56     990
Bank Sta=-7.87,14.2
XS Rating Curve= 0 ,0
Exp/Cntr=0.5,0.3

Type RM Length L Ch R = 3 ,803     ,,,
BEGIN DESCRIPTION:
Driveway (Surveyed Structure REU_04)
END DESCRIPTION:
Bridge Culvert--1,0,-1,-1, 0
Deck Dist Width WeirC Skew NumUp NumDn MinLoCord MaxHiCord MaxSubmerge Is_Ogee
6.2,15.9,2.61,0, 35, 36, , , 0.98, 0, 0,0,,
-114.995-112.797-109.844-109.811-109.778-105.415-101.707-101.084-100.395 -96.228
 -94.752 -90.946   -85.5 -85.467 -85.434 -82.547 -80.054 -78.249  -76.97 -74.411
 -70.736 -70.572 -65.618   -6.86   -6.85   10.85   10.86  21.849  37.958  40.123
  43.798  87.335 132.938 135.005  137.63
  993.27  992.59  991.77  991.73  991.73  990.72   989.8   989.6  989.44  988.32
  987.99   987.2  986.22  986.22  986.19  985.27  985.07  984.78  984.71  984.45
  984.06  984.06  984.06  984.58  984.58  984.71  984.71  984.74   985.3  984.88
  986.06  988.42 1000.16 1000.66 1001.25
                                                                                
                                                                                
                                  983.79  983.92
                                        
 -132.48-116.995-114.797-111.844-111.811-111.778-107.415-103.707-103.084-102.395
 -98.228 -96.752 -92.946   -87.5 -87.467 -87.434 -84.547 -82.054 -80.249  -78.97
 -76.411 -72.736 -72.572 -67.618   -8.86   -8.85    8.85    8.86  19.849  35.958
  38.123  41.798  85.335 130.938 133.005  135.63
  993.93  993.27  992.59  991.77  991.73  991.73  990.72   989.8   989.6  989.44
  988.32  987.99   987.2  986.22  986.22  986.19  985.27  985.07  984.78  984.71
  984.45  984.06  984.06  984.06  984.58  984.58  984.71  984.71  984.74   985.3
  984.88  986.06  988.42 1000.16 1000.66 1001.25
                                                                                
                                                                                
                                          983.79  983.92
                                                
BR Coef=-1 , 0 , 0 ,, 0 ,,,0.8,-1,1.2,0,
WSPro=,,,, 1 ,,,, 0 ,,,, 0 ,,,,-1 ,-1 ,-1 , 0 , 0 , 0 , 0 , 0
BC Design=,, 0 ,, 0 ,,,,,,
BC Use User HTab Curves=0
BC User HTab FreeFlow(D)= 0

Type RM Length L Ch R = 1 ,783     ,58.12,58,57.7
BEGIN DESCRIPTION:
DS of Driveway (Channel from survey data REU_04)
END DESCRIPTION:
XS GIS Cut Line= 4
579027.1870217794370453.30404789579020.1872896924370467.06393926
579019.6072552854370491.90392037579019.1271952794370533.21407448
#Sta/Elev= 30
 -132.48  993.93-124.639   991.5-118.176  990.75-103.707  986.68 -93.996  984.84
   -85.4  983.96  -73.36  983.76 -60.564  983.01 -43.668  983.46  -35.86  983.27
 -28.182  982.58 -19.259  982.71 -14.239  982.09   -13.2  981.59  -6.168  978.18
    1.87  977.69   7.021  978.48    10.5  981.53  13.156  983.89  18.832  984.22
  25.098  985.17  38.812  985.17  51.115  986.25  67.815  986.61  77.067  987.34
  82.218  988.16   91.24  990.19 102.067  993.77 126.345  1000.2 135.203 1001.97
#Mann= 5 ,-1 , 0
 -132.48     .06       0   -13.2     .05       0    10.5     .06       0
  18.832     .03       0  38.812     .06       0
#XS Ineff= 2 , 0
       0  -16.85  984.58   16.85       0  984.58
Permanent Ineff=
       F       F
#Block Obstruct= 1 ,-1
 -55.971 -30.085  989.99
Bank Sta=-13.2,10.5
XS Rating Curve= 0 ,0
Exp/Cntr=0.5,0.3

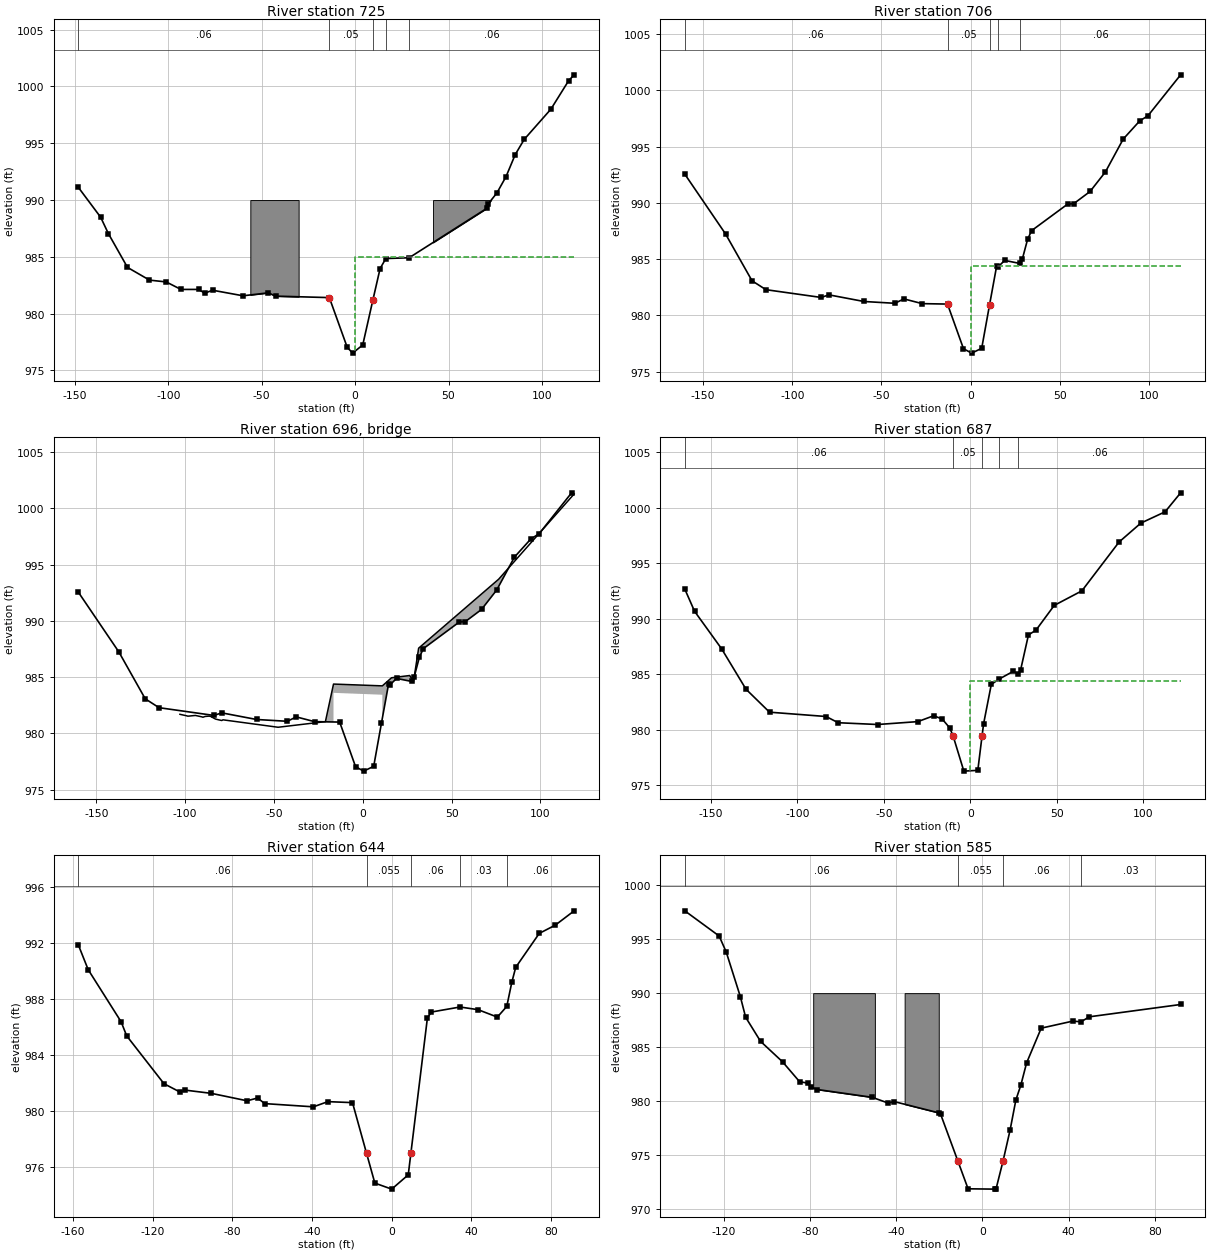
Type RM Length L Ch R = 1 ,725     ,18.73,19,19.26
BEGIN DESCRIPTION:
(Surveyed XS REU_03)
END DESCRIPTION:
XS GIS Cut Line= 3
579015.7271512374370450.47397986579001.7572526644370478.73412181
 579002.237007874370528.10410242
#Sta/Elev= 30
 -148.13  991.11-136.188  988.48-132.054  987.04-121.818  984.06-110.039  982.94
-101.083  982.78 -93.209  982.12  -83.76  982.12 -80.479  981.79  -76.28  982.05
 -60.007  981.56 -46.424  981.82  -42.52  981.53  -13.78   981.4  -4.232  977.03
  -1.312  976.51   4.101  977.23     9.5  981.17  13.386  983.96   16.47  984.84
  28.937  984.91  70.866   989.3  71.325  989.67  75.919  990.62  80.807  992.06
  85.728     994  90.551  995.34 104.823     998  114.37 1000.52 117.257 1001.02
#Mann= 5 ,-1 , 0
 -148.13     .06       0  -13.78     .05       0     9.5     .06       0
   16.47     .03       0  28.937     .06       0
#XS Ineff= 2 , 0
       0     -26     985               0
Permanent Ineff=
       F       F
#Block Obstruct= 2 ,-1
  -56.07 -30.217  989.99  41.732  75.591  989.99
Bank Sta=-13.78,9.5
XS Rating Curve= 0 ,0
Exp/Cntr=0.5,0.3

Type RM Length L Ch R = 1 ,706     ,18.307,19,18.675
BEGIN DESCRIPTION:
US of Pedestrian Bridge (Channel from survey data REU_03)
END DESCRIPTION:
XS GIS Cut Line= 4
579014.8770640264370447.78411982578996.4070981984370481.75408024
578995.9971421934370499.50410846578995.8971677924370527.73407521
#Sta/Elev= 30
-160.171  992.55-137.369  987.24-122.507  983.07-114.731  982.28 -83.793  981.59
 -79.429  981.82  -59.81  981.23  -42.52  981.07 -37.434  981.46 -27.198  981.04
 -13.025     981  -4.068  977.03    .525  976.64   6.135  977.07    10.5  980.91
  14.501  984.38  15.059  984.28  19.029  984.88  27.592  984.61  28.904  985.01
  31.824  986.75  34.088  987.53  54.364   989.9   57.71  989.93  66.831  991.01
  75.427  992.75    85.4  995.67  94.619  997.28  99.245  997.74 117.552 1001.38
#Mann= 5 ,-1 , 0
-160.171     .06       0 -13.025     .05       0    10.5     .06       0
  15.059     .03       0  27.592     .06       0
#XS Ineff= 2 , 0
       0     -20  984.38               0
Permanent Ineff=
       F       F
Bank Sta=-13.025,10.5
XS Rating Curve= 0 ,0
Exp/Cntr=0.5,0.3

Type RM Length L Ch R = 3 ,696     ,,,
BEGIN DESCRIPTION:
Pedestrian Bridge (Surveyed Structure REU_03)
END DESCRIPTION:
Bridge Culvert--1,0,-1,-1, 0
Deck Dist Width WeirC Skew NumUp NumDn MinLoCord MaxHiCord MaxSubmerge Is_Ogee
8.3,3.8,2.61,0, 24, 24, , , 0.98, 0, 0,0,,
-102.953 -99.213 -98.655 -98.064 -94.259 -90.486 -90.026 -88.812 -86.483 -85.597
 -82.972 -81.135 -79.429 -78.707 -47.703 -21.063   -16.5      11  16.175  26.378
  28.543   31.43  76.476 118.996
  981.69  981.56  981.53  981.53  981.59  981.46  981.43   981.5  981.53   981.5
  981.27   981.2  981.14   981.2  980.54  981.04  984.38  984.22  984.94  985.14
  984.61  987.57   993.7 1001.28
                                                                                
                                                   983.6  983.43
                                
-102.953 -99.213 -98.655 -98.064 -94.259 -90.486 -90.026 -88.812 -86.483 -85.597
 -82.972 -81.135 -79.429 -78.707 -47.703 -21.063   -16.5      11  16.175  26.378
  28.543   31.43  76.476 118.996
  981.69  981.56  981.53  981.53  981.59  981.46  981.43   981.5  981.53   981.5
  981.27   981.2  981.14   981.2  980.54  981.04  984.38  984.22  984.94  985.14
  984.61  987.57   993.7 1001.28
                                                                                
                                                   983.6  983.43
                                
BR Coef=-1 , 0 , 0 ,, 0 ,,,0.8,-1,,0,
WSPro=,,,, 1 ,,,, 0 ,,,, 0 ,,,,-1 ,-1 ,-1 , 0 , 0 , 0 , 0 , 0
BC Design=,, 0 ,, 0 ,,,,,,
BC Use User HTab Curves=0
BC User HTab FreeFlow(D)= 0

Type RM Length L Ch R = 1 ,687     ,33.46,43,52.79
BEGIN DESCRIPTION:
DS of Pedestrian Bridge
END DESCRIPTION:
XS GIS Cut Line= 4
579010.0371447674370445.15400059578990.9371573314370480.30414663
578990.4970261254370499.43400446578990.3970517244370527.71395841
#Sta/Elev= 30
-165.157  992.68-159.514  990.68-143.865   987.3-129.757  983.66-116.142  981.59
 -83.432   981.2 -76.411  980.64 -53.609  980.48 -30.348  980.74 -21.161  981.27
  -16.24  980.97 -11.942  980.18   -9.98  979.46   -3.74  976.28   4.331  976.35
     6.8  979.46   7.677  980.54  12.139  984.09  16.404  984.55  24.836  985.27
  27.723  985.04  29.101   985.4  33.629  988.55  37.992  988.98  48.556  991.21
  64.534  992.52  86.056  996.92  98.622  998.62 112.664  999.64 121.654 1001.35
#Mann= 5 ,-1 , 0
-165.157     .06       0   -9.98     .05       0     6.8     .06       0
  16.404     .03       0  27.723     .06       0
#XS Ineff= 2 , 0
       0  -21.88  984.38               0
Permanent Ineff=
       F       F
Bank Sta=-9.98,6.8
XS Rating Curve= 0 ,0
Exp/Cntr=0.5,0.3

Type RM Length L Ch R = 1 ,644     ,63.49,59,53.3
BEGIN DESCRIPTION:
(Channel from survey data REU_03)
END DESCRIPTION:
XS GIS Cut Line= 4
579007.4670711354370444.76416139578989.2171709094370479.68387862
 578971.477201094370485.37388509578966.197150625 4370502.3841637
#Sta/Elev= 30
-157.283  991.86-152.329  990.09-135.827  986.38-133.005  985.37-114.304  981.96
-106.201  981.36-103.543   981.5 -90.486  981.27 -72.572  980.74 -67.323  980.94
 -63.747  980.54 -39.304  980.31 -32.054  980.68 -19.685  980.61  -12.64     977
  -8.465  974.87       0  974.44   8.301  975.46    9.62     977  17.913  986.65
  19.882  987.07  34.285  987.43   43.34  987.24  53.018  986.71  57.743  987.47
  60.302  989.21  62.238  990.26  74.049  992.68  82.119  993.27  91.568  994.29
#Mann= 5 ,-1 , 0
-157.283     .06       0  -12.64    .055       0    9.62     .06       0
  34.285     .03       0  57.743     .06       0
Bank Sta=-12.64,9.62
XS Rating Curve= 0 ,0
Exp/Cntr=0.3,0.1

Type RM Length L Ch R = 1 ,585     ,81.26,80,78.48
XS GIS Cut Line= 2
579000.9672110554370433.80416285578956.5170073054370488.10397872
#Sta/Elev= 30
-138.222  997.61-122.277  995.28-118.996   993.8-112.434  989.67-109.974  987.76
-103.051  985.53 -92.815  983.63 -84.908  981.79 -81.004  981.66  -79.79   981.3
 -76.673  981.07 -51.247  980.35 -43.832  979.82 -40.945  979.95 -20.079   978.9
 -19.488  978.81  -11.41  974.44  -6.693  971.88    5.61  971.85   6.266  971.85
    9.53  974.44  12.795   977.3  15.518  980.12  17.782  981.46  20.472  983.53
  27.264  986.75  41.896   987.4  45.768  987.34  49.573   987.8  91.995  988.94
#Mann= 4 ,-1 , 0
-138.222     .06       0  -11.41    .055       0    9.53     .06       0
  45.768     .03       0
#Block Obstruct= 3 ,-1
 -36.155 -20.308  989.99 -78.609 -49.967  989.99-138.222-114.829  989.99
Bank Sta=-11.41,9.53
XS Rating Curve= 0 ,0
Exp/Cntr=0.3,0.1

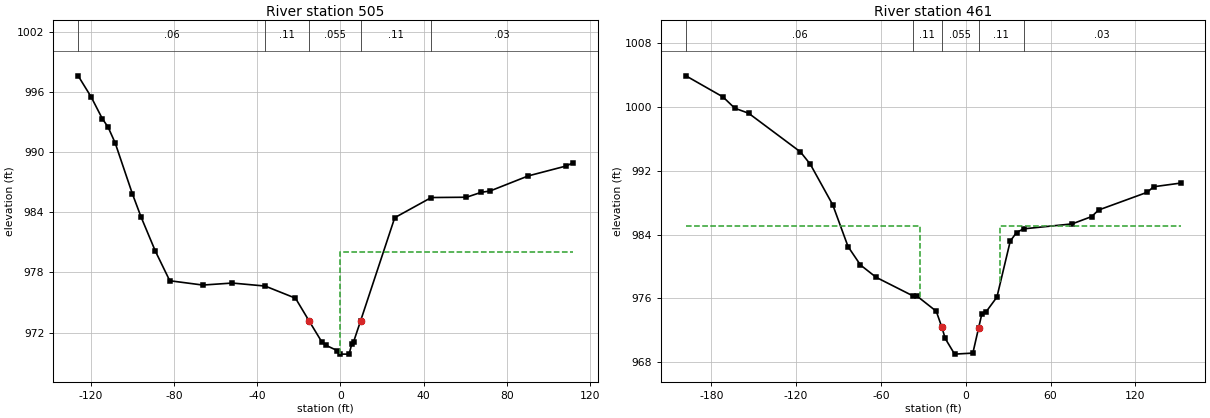
Type RM Length L Ch R = 1 ,505     ,49.94,44,40.17
BEGIN DESCRIPTION:
(Surveyed XS REU_02)
END DESCRIPTION:
XS GIS Cut Line= 4
578972.7070691054370420.26403228578953.4370032674370454.32390871
578946.2470759784370467.67414887578947.307170391 4370485.8740619
#Sta/Elev= 30
-126.115  997.61-119.882  995.51-114.501  993.34-111.713  992.49-108.301  990.91
-100.066  985.86 -95.801   983.5 -88.976  980.12 -82.054  977.17 -66.142  976.74
 -51.969  976.94 -36.188  976.64 -21.588  975.43  -15.16   973.2  -9.022   971.1
  -6.923  970.73  -1.575  970.21       0  969.85   4.167  969.85   5.512  970.87
   6.332  971.06    9.78   973.2  26.148  983.46  43.734  985.47  60.663   985.5
  67.749  985.99  71.982  986.12  90.387  987.63 108.694  988.62 111.844  988.94
#Mann= 5 ,-1 , 0
-126.115     .06       0 -36.188     .11       0  -15.16    .055       0
    9.78     .11       0  43.734     .03       0
#XS Ineff= 2 , 0
       0     -27     980               0
Permanent Ineff=
       F       F
Bank Sta=-15.16,9.78
XS Rating Curve= 0 ,0
Exp/Cntr=0.5,0.3

Type RM Length L Ch R = 1 ,461     ,65.713,67,64.662
BEGIN DESCRIPTION:
US of Bunner Ridge Road
END DESCRIPTION:
XS GIS Cut Line= 5
578946.8271103854370383.05404783578943.3472087424370400.30389924
578942.1072823274370418.86408587578942.0572951264370441.93409335
578945.5070215694370496.05407722
#Sta/Elev= 30
-197.958  1003.9-171.722 1001.25-163.429  999.84-153.625  999.21-116.968  994.36
 -109.97  992.81 -94.123  987.73 -83.271  982.48 -74.516  980.18 -63.478  978.64
 -37.458  976.31 -34.499  976.28 -20.903  974.38     -17  972.41 -14.552  970.96
  -7.923     969   4.994  969.13       9  972.24  11.315  974.02  14.243  974.28
  22.012  976.15  31.447  983.17  35.886  984.25  40.849  984.71  75.194  985.33
  89.037  986.25  93.907  987.07 128.375   989.3 132.845  989.99 151.991  990.45
#Mann= 5 ,-1 , 0
-197.958     .06       0 -37.458     .11       0     -17    .055       0
       9     .11       0  40.849     .03       0
#XS Ineff= 2 ,-1
-197.958  -32.41  985.01   24.51 151.991  985.01
Permanent Ineff=
       F       F
Bank Sta=-17,9
XS Rating Curve= 0 ,0
Skew Angle= 20
Exp/Cntr=0.5,0.3