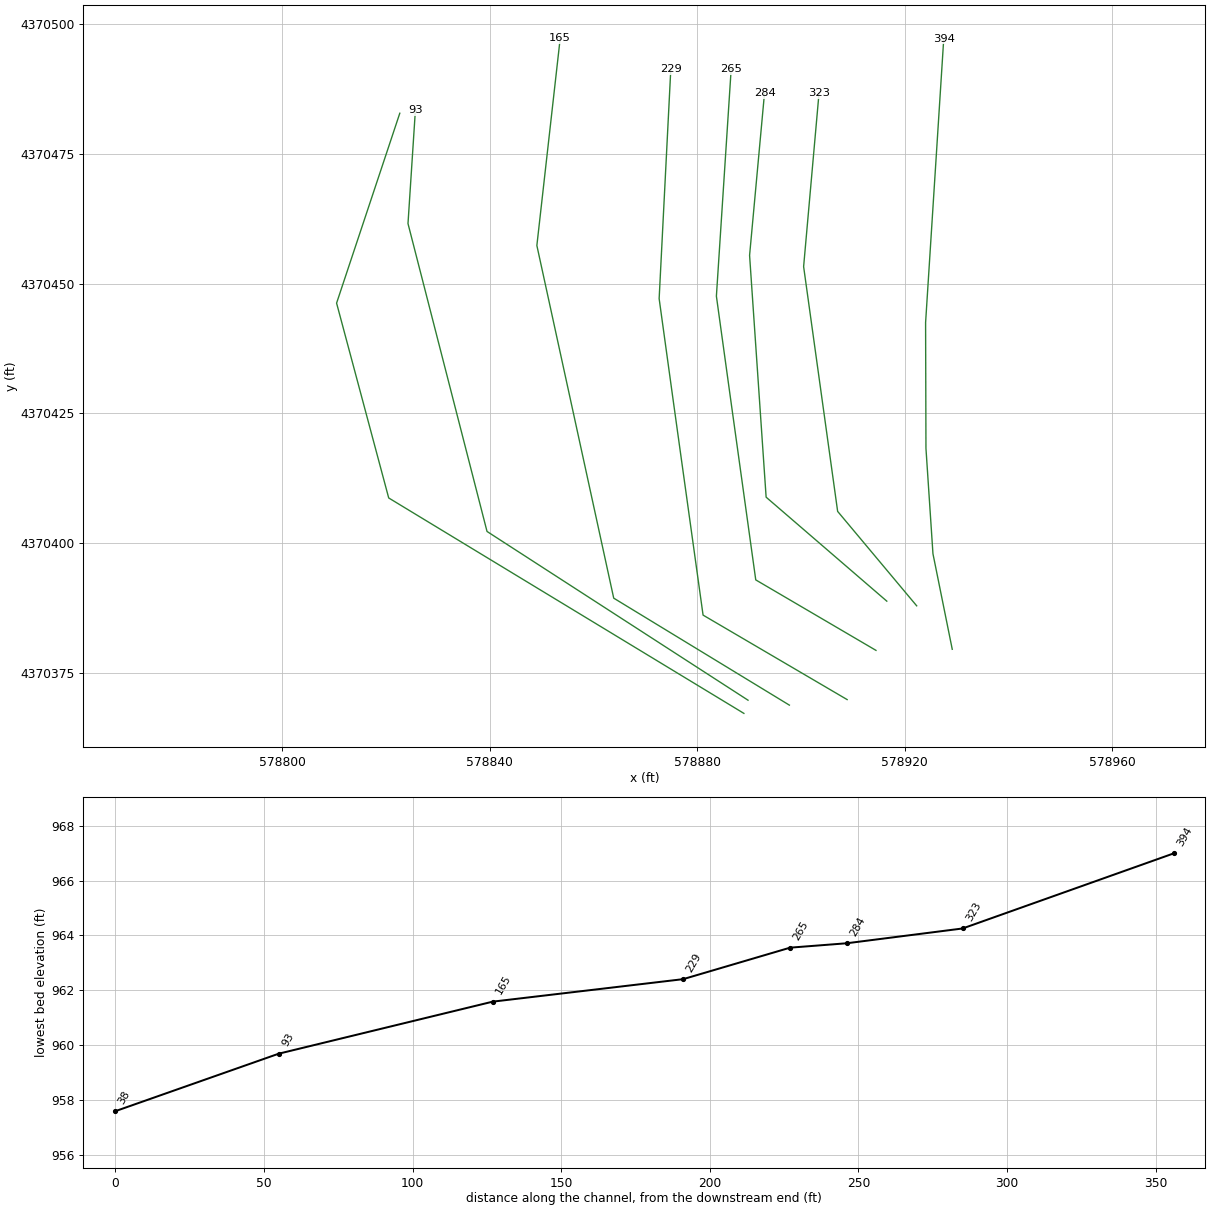
HEC-RAS study Reuben_Run.prj: Reuben Run

--- Reuben_Run.g01 (geometry) --- (continued)

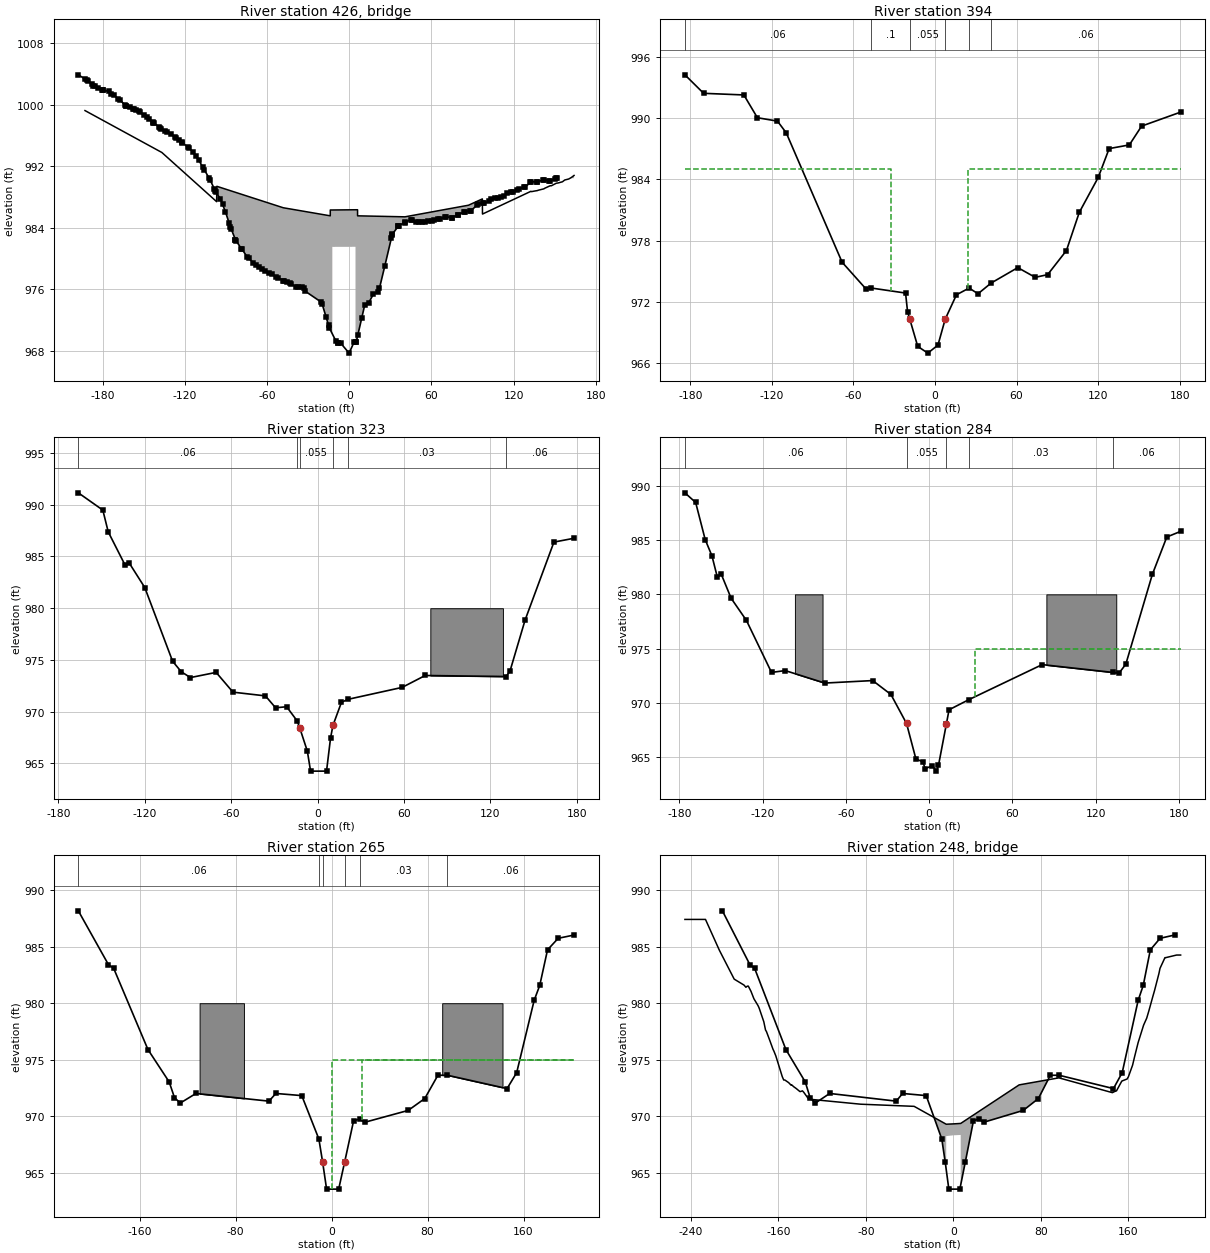
Type RM Length L Ch R = 3 ,426     ,,,
BEGIN DESCRIPTION:
Bunner Ridge Road (Surveyed Structure REU_02)
END DESCRIPTION:
Bridge Culvert--1,0,-1,-1, 0
Deck Dist Width WeirC Skew NumUp NumDn MinLoCord MaxHiCord MaxSubmerge Is_Ogee
22,25.4,2.61,20, 32, 32, , , 0.98, 0, 0,0,,
-193.093-136.951 -96.935 -96.781 -48.255 -13.923 -13.913 -12.409   4.505   6.008
   6.018  40.628  87.027   97.17  97.253 132.655 133.056  133.27 135.214 137.587
 137.772 142.118 142.675 146.683 147.575 151.184 152.447 155.685  157.35 160.248
 162.189 164.132
  999.25   993.8   987.4   989.4  986.61  985.56  986.32  986.32  986.35  986.35
  985.56  985.43  986.94  987.76  985.79  988.75  988.71  988.71  988.78  988.85
  988.88  989.07  989.14  989.47  989.47   989.8  989.83  989.99  990.22  990.35
  990.55  990.81
                                                          981.52  981.53
                                                                                
                                                                                
                
-193.141-136.999 -96.983 -96.828 -48.303  -13.97 -13.961 -12.457   4.457   5.961
    5.97   40.58  86.979  97.122  97.205 132.607 133.008 133.223 135.166 137.539
 137.724 142.071 142.627 146.635 147.528 151.136   152.4 155.637 157.302   160.2
 162.141 164.084
  999.25   993.8   987.4   989.4  986.61  985.56  986.32  986.32  986.35  986.35
  985.56  985.43  986.94  987.76  985.79  988.75  988.71  988.71  988.78  988.85
  988.88  989.07  989.14  989.47  989.47   989.8  989.83  989.99  990.22  990.35
  990.55  990.81
                                                          981.02  981.05
                                                                                
                                                                                
                
BR Coef=-1 , 1 , 0 ,, 0 ,,,0.8,0,1.2,0,
WSPro=,,,, 1 ,,,, 0 ,,,, 0 ,,,,-1 ,-1 ,-1 , 0 , 0 , 0 , 0 , 0
BR U #Sta/Elev= 164
-197.958  1003.9-193.272 1003.38-191.638 1003.18-190.806 1003.08-188.185 1002.69
-186.983 1002.49-186.058  1002.4-183.684 1002.17-180.539 1001.97-180.262 1001.94
-180.138 1001.94-175.915 1001.74-174.373 1001.44-171.722 1001.25 -168.67 1000.75
-167.467 1000.66-164.045  999.97-163.429  999.84-163.059  999.84-160.284   999.7
-157.972  999.48-157.109  999.51-155.752  999.38-153.625  999.21-152.977  999.05
-149.894  998.65-148.107  998.46-146.133  998.16-143.667  997.74-143.266  997.64
-142.403  997.61-138.672  997.05-138.487  996.98-137.501  996.88-134.479  996.62
-133.154  996.46-130.503  996.23-127.451  995.83-126.526  995.73 -124.46  995.41
-122.394  995.11-121.994  995.05-118.171  994.55-116.968  994.36 -114.07  993.86
-112.097  993.34 -109.97  992.81-107.226  991.93-105.901  991.54-102.355  990.45
 -101.77  990.26 -98.656  989.07 -97.823  988.75 -97.515  988.65 -94.123  987.73
 -92.612  987.04 -90.516  986.09 -87.896  984.65  -86.94  984.15 -86.324  983.86
 -83.271  982.48 -83.179  982.45 -82.809  982.35 -78.863  981.27 -78.338   981.2
 -74.516  980.18 -73.437  980.02 -70.138  979.46 -68.473   979.2 -65.699   978.9
 -63.478  978.64 -61.259  978.41 -58.392  978.18 -56.819  978.05 -53.336  977.59
 -52.349  977.53 -48.311  977.13  -47.94   977.1 -45.227   976.9 -43.439  976.77
 -42.977  976.74     -39  976.35 -37.458  976.31 -34.499  976.28 -33.204  976.12
 -32.186  975.75 -20.903  974.38 -19.793  974.05     -17  972.41   -15.2  971.33
 -14.552  970.96  -9.681  969.23   -8.54  969.06  -7.923     969   -6.32     969
   -.185   967.7   3.453  969.13   4.994  969.13   5.087  969.19   6.258  970.11
       9  972.24  11.315  974.02  14.243  974.28  17.542  975.36  20.779  975.66
  22.012  976.15  25.959  979.07  30.706  982.68  31.169  983.01  31.447  983.17
  35.763  984.22  35.886  984.25  35.917  984.25  40.295  984.68  40.849  984.71
  44.734  985.07  45.721  984.97   49.05  984.71   50.53  984.74  53.397  984.78
  55.339  984.81  57.775  984.91  60.242  984.94  62.122  984.97  65.082  985.11
    66.5  985.14  69.922   985.4  70.878  985.43  74.762  985.33  75.194  985.33
   79.51  985.73  79.633  985.73  83.949  986.06  84.289  986.09  88.358  986.22
  89.037  986.25   92.89  986.91  93.907  987.07  97.392  987.24  98.717   987.2
   101.8  987.43 103.527  987.73 106.209  987.83 108.243  987.89 110.618  988.02
 112.991  988.19 115.119  988.48 117.801  988.62 119.496  988.71 122.518  988.88
 123.936  989.01 127.327   989.3 128.375   989.3 132.168   989.9 132.845  989.99
 136.946  989.96 137.285  989.96 141.724  990.26 141.879  990.26 145.886  990.12
 146.288  990.12  150.11  990.39 150.943  990.45 151.991  990.45
BR U #Mann= 5
-197.958     .06 -37.458     .11     -17    .055       9     .11  40.849     .03
BC Design=,, 0 ,, 0 ,,,,,,
BC Use User HTab Curves=0
BC User HTab FreeFlow(D)= 0

Type RM Length L Ch R = 1 ,394     ,68.47,71,71.84
BEGIN DESCRIPTION:
DS of Bunner Ridge Road (Channel from survey data REU_02)
END DESCRIPTION:
XS GIS Cut Line= 5
578929.1871149674370379.49398378578925.4670309214370397.91396241
578924.1170717054370418.24412266578924.0472725044370442.49401096
578927.5472909474370497.20408764
#Sta/Elev= 30
  -183.9  994.23 -170.15  992.42-140.553  992.26-130.595  990.03-115.858   989.7
-109.384  988.55 -68.318  975.89 -50.869  973.29 -46.769  973.36 -21.642  972.87
 -20.194  971.06   -18.6  970.34 -12.702  967.65  -5.272  966.99   2.189  967.78
     7.5  970.31  15.785   972.7  25.095  973.36  31.631   972.8  41.281  973.85
  60.889  975.36  73.683  974.41  82.809  974.67  96.651  977.03 106.117  980.77
 120.051  984.19 128.067  987.01 142.927  987.37 151.929  989.21 180.631  990.58
#Mann= 6 ,-1 , 0
  -183.9     .06       0 -46.769      .1       0   -18.6    .055       0
     7.5      .1       0  25.095     .03       0  41.281     .06       0
#XS Ineff= 2 ,-1
  -183.9  -32.46  985.01   24.46 180.631  985.01
Permanent Ineff=
       F       F
Bank Sta=-18.6,7.5
XS Rating Curve= 0 ,0
Skew Angle= 20
Exp/Cntr=0.5,0.3

Type RM Length L Ch R = 1 ,323     ,39.76,39,38.45
XS GIS Cut Line= 4
578922.3272860834370387.87415508578907.0872858944370406.08412651
578900.5270754134370453.28393109 578903.497046654370486.72414911
#Sta/Elev= 30
-166.175  991.14-149.147  989.47-145.407  987.37-133.563  984.12-130.643  984.32
-120.013  981.99-100.689  974.87 -94.652  973.85 -88.287  973.29  -70.44  973.79
 -58.727  971.88 -36.188  971.52 -29.134  970.37 -21.457  970.47 -14.075  969.09
   -12.3 968.408  -7.054  966.17  -4.823  964.25   6.266  964.25   9.055  967.45
  10.728  968.67  16.634   970.9   21.26  971.19  58.793  972.34  74.803  973.49
 131.037  973.39 133.727  973.92 144.193  978.84 164.239  986.38 178.215  986.75
#Mann= 6 ,-1 , 0
-166.175     .06       0 -14.075      .1       0   -12.3    .055       0
  10.728      .1       0   21.26     .03       0 131.037     .06       0
#Block Obstruct= 1 ,-1
  78.379 128.806  979.99
Bank Sta=-12.3,10.728
XS Rating Curve= 0 ,0
Exp/Cntr=0.3,0.1

Type RM Length L Ch R = 1 ,284     ,17.9,19,19.33
BEGIN DESCRIPTION:
(Surveyed XS REU_01)
END DESCRIPTION:
XS GIS Cut Line= 4
578916.567175612 4370388.7739247578893.2972193244370408.82397374
578890.1071824844370455.45410712 578892.987237724370486.75401951
#Sta/Elev= 30
-175.984  989.34-168.241  988.45-161.385  985.04-156.496  983.53-152.592  981.56
-149.934  981.89-142.684  979.63 -131.66  977.59-113.583   972.8-103.707  972.97
 -75.197  971.82  -40.65  972.05 -27.526  970.77  -16.26 968.097  -9.514  964.83
  -4.593  964.57  -2.789  963.94   2.395  964.21   5.282  963.71   6.759  964.24
   12.43  968.04   14.37  969.36  28.445  970.28  81.496  973.52 132.448   972.8
 136.909  972.74 141.765  973.56  160.86  981.82 171.293  985.27 181.266  985.79
#Mann= 5 ,-1 , 0
-175.984     .06       0  -16.26    .055       0   12.43      .1       0
  28.445     .03       0 132.448     .06       0
#XS Ineff= 2 , 0
       0                      33       0     975
Permanent Ineff=
       F       F
#Block Obstruct= 2 ,-1
  84.514 134.875  979.99 -96.719 -76.804  979.99
Bank Sta=-16.26,12.43
XS Rating Curve= 0 ,0
Exp/Cntr=0.5,0.3

Type RM Length L Ch R = 1 ,265     ,36.103,36,36.106
BEGIN DESCRIPTION:
US of Private driveway
END DESCRIPTION:
XS GIS Cut Line= 5
578914.4771619864370379.28397658578891.2971216994370392.87409435
578886.4270272394370427.90414918578883.7072968054370447.58386622
 578886.557176844370491.38393156
#Sta/Elev= 30
-211.253  988.16-186.122   983.4-181.759  983.07-153.182  975.89-135.499  973.03
-131.102  971.65 -126.28  971.16-113.156  972.01 -52.297  971.33 -46.522  972.01
 -24.934  971.82 -10.663  967.98    -7.5  965.91  -4.232  963.55    5.84  963.55
   10.75  965.91  18.274  969.59  23.228  969.75  27.526  969.46  63.812  970.51
  77.625  971.56  88.583  973.62  96.555  973.62  146.26  972.44 154.265  973.85
 168.865  980.25 173.491  981.56 179.987  984.71 188.878  985.73   202.1  986.02
#Mann= 6 ,-1 , 0
-211.253     .06       0 -10.663      .1       0    -7.5    .055       0
   10.75      .1       0  23.228     .03       0  96.555     .06       0
#XS Ineff= 2 , 0
       0   -35.7     975      25       0     975
Permanent Ineff=
       F       F
#Block Obstruct= 4 ,-1
  92.159 142.454  979.99 190.256   202.1  979.99-110.138 -73.163  979.99
-206.594-176.542  979.99
Bank Sta=-7.5,10.75
XS Rating Curve= 0 ,0
Exp/Cntr=0.5,0.3

Type RM Length L Ch R = 3 ,248     ,,,
BEGIN DESCRIPTION:
Private driveway (Surveyed Structure REU_01)
END DESCRIPTION:
Bridge Culvert--1,0,-1,-1, 0
Deck Dist Width WeirC Skew NumUp NumDn MinLoCord MaxHiCord MaxSubmerge Is_Ogee
12.5,11.9,2.61,0, 68, 68, , , 0.98, 0, 0,0,,
 -245.51-226.706-214.042-200.459-191.437-189.764-188.451-187.533-185.105-182.415
 -178.74-177.953-177.395-173.392-171.818-170.997-167.815-164.993 -164.14-162.402
-160.696-156.496-155.184-154.167-150.722-148.425  -147.9-146.096-143.668 -140.42
-139.829-138.058-136.844-132.448 -130.61-130.577  -84.81 -35.958  -6.627       0
   6.627  60.072  60.105  96.391 145.308  147.31 148.917 149.049 153.871 154.528
  158.76 159.941 163.747 165.518 168.832 171.161 173.819 176.673 178.773 182.251
 183.793 187.828 188.812  193.34 193.734 194.062 204.003  207.68
   987.4   987.4  984.68  982.12  981.59   981.4   981.5   981.5  981.04  980.38
  979.79  979.63  979.49  978.35  977.62  977.49  976.67  975.92  975.75  975.33
   974.8  973.49   973.2   973.2  972.97  972.74  972.77  972.61  972.44  972.18
  972.18  972.24  972.11  971.52  971.49  971.49  971.06  970.87  969.29  969.32
  969.36  972.77  972.77  973.39  972.08  972.18  972.24  972.24   973.1  973.13
  973.29  973.49  974.51  975.23  976.51  977.23  978.05  978.67  979.36  980.58
   981.1  982.61  983.07  984.02  984.02  984.02  984.25  984.25
                                                                                
                                                                                
                                                                                
                                                                  968.24  968.31
  968.34
                                                                                
                                                                
 -245.51-226.706-214.042-200.459-191.437-189.764-188.451-187.533-185.105-182.415
 -178.74-177.953-177.395-173.392-171.818-170.997-167.815-164.993 -164.14-162.402
-160.696-156.496-155.184-154.167-150.722-148.425  -147.9-146.096-143.668 -140.42
-139.829-138.058-136.844-132.448 -130.61-130.577  -84.81 -35.958  -6.627       0
   6.627  60.072  60.105  96.391 145.308  147.31 148.917 149.049 153.871 154.528
  158.76 159.941 163.747 165.518 168.832 171.161 173.819 176.673 178.773 182.251
 183.793 187.828 188.812  193.34 193.734 194.062 204.003  207.68
   987.4   987.4  984.68  982.12  981.59   981.4   981.5   981.5  981.04  980.38
  979.79  979.63  979.49  978.35  977.62  977.49  976.67  975.92  975.75  975.33
   974.8  973.49   973.2   973.2  972.97  972.74  972.77  972.61  972.44  972.18
  972.18  972.24  972.11  971.52  971.49  971.49  971.06  970.87  969.29  969.32
  969.36  972.77  972.77  973.39  972.08  972.18  972.24  972.24   973.1  973.13
  973.29  973.49  974.51  975.23  976.51  977.23  978.05  978.67  979.36  980.58
   981.1  982.61  983.07  984.02  984.02  984.02  984.25  984.25
                                                                                
                                                                                
                                                                                
                                                                  968.24  968.31
  968.34
                                                                                
                                                                
BR Coef=-1 , 1 , 0 ,, 0 ,,,0.8,0,1.2,0,
WSPro=,,,, 1 ,,,, 0 ,,,, 0 ,,,,-1 ,-1 ,-1 , 0 , 0 , 0 , 0 , 0
BC Design=,, 0 ,, 0 ,,,,,,
BC Use User HTab Curves=0
BC User HTab FreeFlow(D)= 0

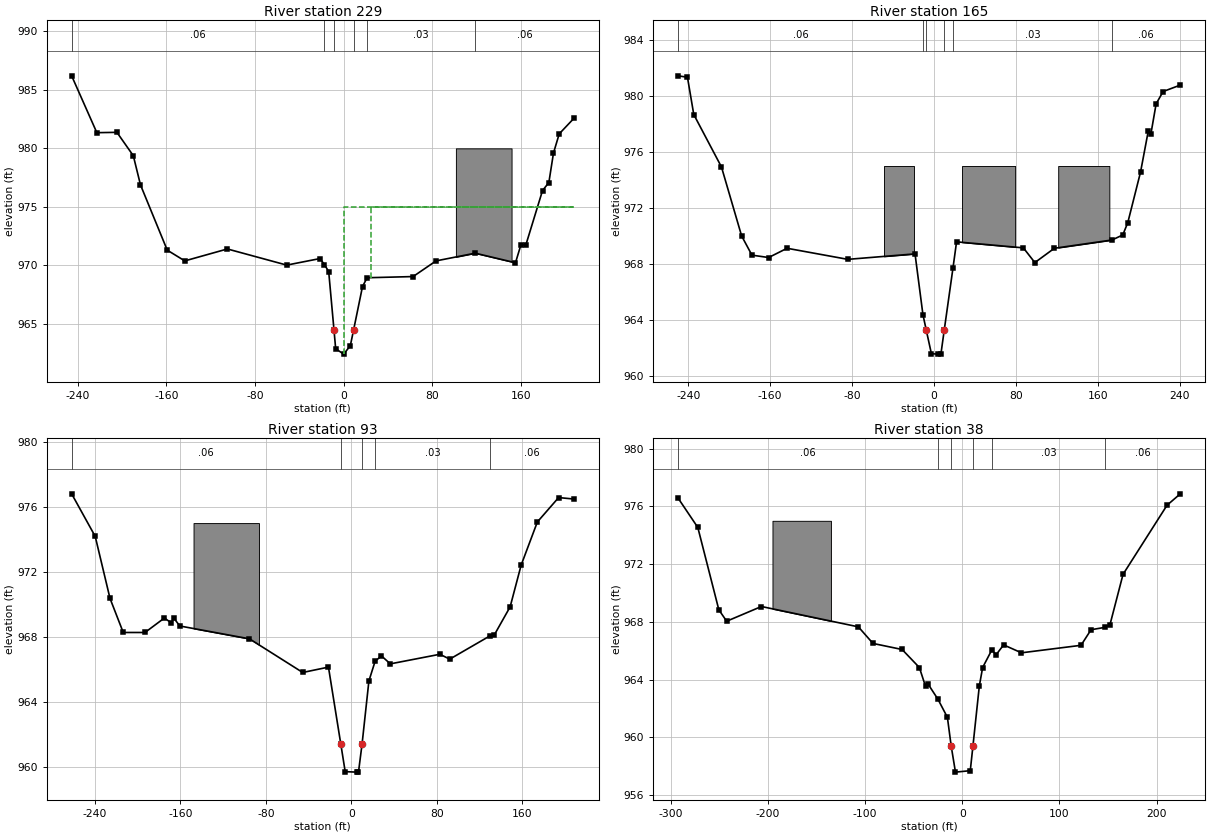
Type RM Length L Ch R = 1 ,229     ,63.37,64,64.87
BEGIN DESCRIPTION:
DS of Private driveway (Channel from survey data REU_01)
END DESCRIPTION:
XS GIS Cut Line= 5
578908.9173051174370369.79402846578881.1372231744370386.08406466
578875.5270743044370426.39386516578872.6671358694370447.10411102
578874.9171694974370491.38393156
#Sta/Elev= 30
-245.505  986.19-222.769  981.33-204.659  981.36-189.862  979.36-183.399  976.87
-159.252  971.29-143.406  970.37-104.987  971.39 -51.411  970.01 -21.391  970.57
 -17.388  970.05  -13.55  969.46    -8.8   964.5  -7.251  962.86       0   962.4
   5.971  963.12       9   964.5  16.962  968.18  21.161  968.93  62.631  969.03
  83.333  970.37 118.635  971.03  155.02  970.21 159.843  971.72 164.436  971.75
 179.396  976.38 185.138  977.07 189.304  979.59 194.488  981.23 207.677  982.55
#Mann= 6 ,-1 , 0
-245.505     .06       0 -17.388      .1       0    -8.8    .055       0
       9      .1       0  21.161     .03       0 118.635     .06       0
#XS Ineff= 2 , 0
       0  -21.39     975      25       0     975
Permanent Ineff=
       F       F
#Block Obstruct= 3 ,-1
 101.247 151.476  979.99 200.394  207.71  979.99-245.505 -221.26  979.99
Bank Sta=-8.8,9
XS Rating Curve= 0 ,0
Exp/Cntr=0.5,0.3

Type RM Length L Ch R = 1 ,165     ,71.62,72,72.33
XS GIS Cut Line= 4
578897.7771697794370368.72387565578863.907183761 4370389.3539591
578849.0871979774370457.35392554578853.5872652334370497.30406204
#Sta/Elev= 30
-249.902  981.43-240.781  981.33-234.613  978.67-207.579  974.93-187.894  970.01
-177.822  968.64-161.516  968.47-143.504  969.13 -84.219  968.34  -18.57  968.73
  -10.86   964.4    -7.6  963.29  -2.592  961.61   4.199  961.58   6.693  961.58
      10  963.32  18.537  967.75  21.982  969.59  87.205  969.16  98.425  968.11
 117.487  969.13  173.72  969.72 184.285  970.08 189.173  970.96  201.64  974.57
 209.088  977.46  211.68  977.26 216.831  979.43 223.655  980.31 240.453  980.77
#Mann= 6 ,-1 , 0
-249.902     .06       0  -10.86      .1       0    -7.6    .055       0
      10      .1       0  18.537     .03       0  173.72     .06       0
#Block Obstruct= 3 ,-1
  27.329  79.167     975 121.227 171.161     975 -48.852 -19.619     975
Bank Sta=-7.6,10
XS Rating Curve= 0 ,0
Exp/Cntr=0.3,0.1

Type RM Length L Ch R = 1 ,93      ,55.03,55,55.13
XS GIS Cut Line= 4
578889.8072592814370369.67393726578839.4771586594370402.21408086
 578824.23715847   4370461.58394578825.6672800884370483.49387867
#Sta/Elev= 30
 -261.68   976.8-239.633  974.18 -225.82  970.37-213.419  968.27-193.077  968.27
-174.934  969.16-168.438  968.86-166.142  969.16-160.531  968.67 -95.341  967.88
 -45.538  965.81 -21.457  966.14   -9.95  961.42  -5.807  959.71   4.856  959.68
   6.627  959.68      10  961.42  16.371  965.29  22.178   966.5  28.117  966.83
  36.417  966.34  82.776  966.93  91.995  966.63 130.085  968.08 133.596  968.11
 148.491  969.85  158.76  972.41  173.95  975.07 193.832  976.57 208.071  976.48
#Mann= 5 ,-1 , 0
 -261.68     .06       0   -9.95     .05       0      10      .1       0
  22.178     .03       0 130.085     .06       0
#Block Obstruct= 1 ,-1
-147.671 -86.483     975
Bank Sta=-9.95,10
XS Rating Curve= 0 ,0
Exp/Cntr=0.3,0.1

Type RM Length L Ch R = 1 ,38      ,32.1,38,48.64
XS GIS Cut Line= 4
578889.0071592714370367.13403883578820.5170744244370408.67401214
  578810.46720874370446.24396541578822.6570752514370482.86416186
#Sta/Elev= 30
 -292.52  976.57-272.244  974.54-250.591  968.83 -242.52  968.04-206.759  969.06
-106.955  967.65 -91.896   966.5 -61.909  966.08 -44.127  964.83 -37.795  963.52
 -35.138  963.68     -25  962.63 -15.289  961.38  -11.36  959.38  -6.988  957.58
   8.268  957.68      11  959.38  17.585  963.55  20.997  964.83  30.381  966.04
  34.941  965.72  42.585   966.4  60.958  965.85 122.277  966.37 132.612  967.45
 147.375  967.62 152.133  967.81 165.551  971.29  210.86  976.08 224.508  976.87
#Mann= 6 ,-1 , 0
 -292.52     .06       0     -25      .1       0  -11.36     .05       0
      11      .1       0  30.381     .03       0 147.375     .06       0
#Block Obstruct= 1 ,-1
-195.374-135.203     975
Bank Sta=-11.36,11
XS Rating Curve= 0 ,0
Exp/Cntr=0.3,0.1
Stream Node=Reuben Run      ,Reach 1         , 0 , 0 ,Upstream end
Stream Node=Reuben Run      ,Reach 1         , 0 , 1 ,Downstream end

Chan Stop Cuts=-1
Use User Specified Reach Order=0
Composite Channel Slope=5