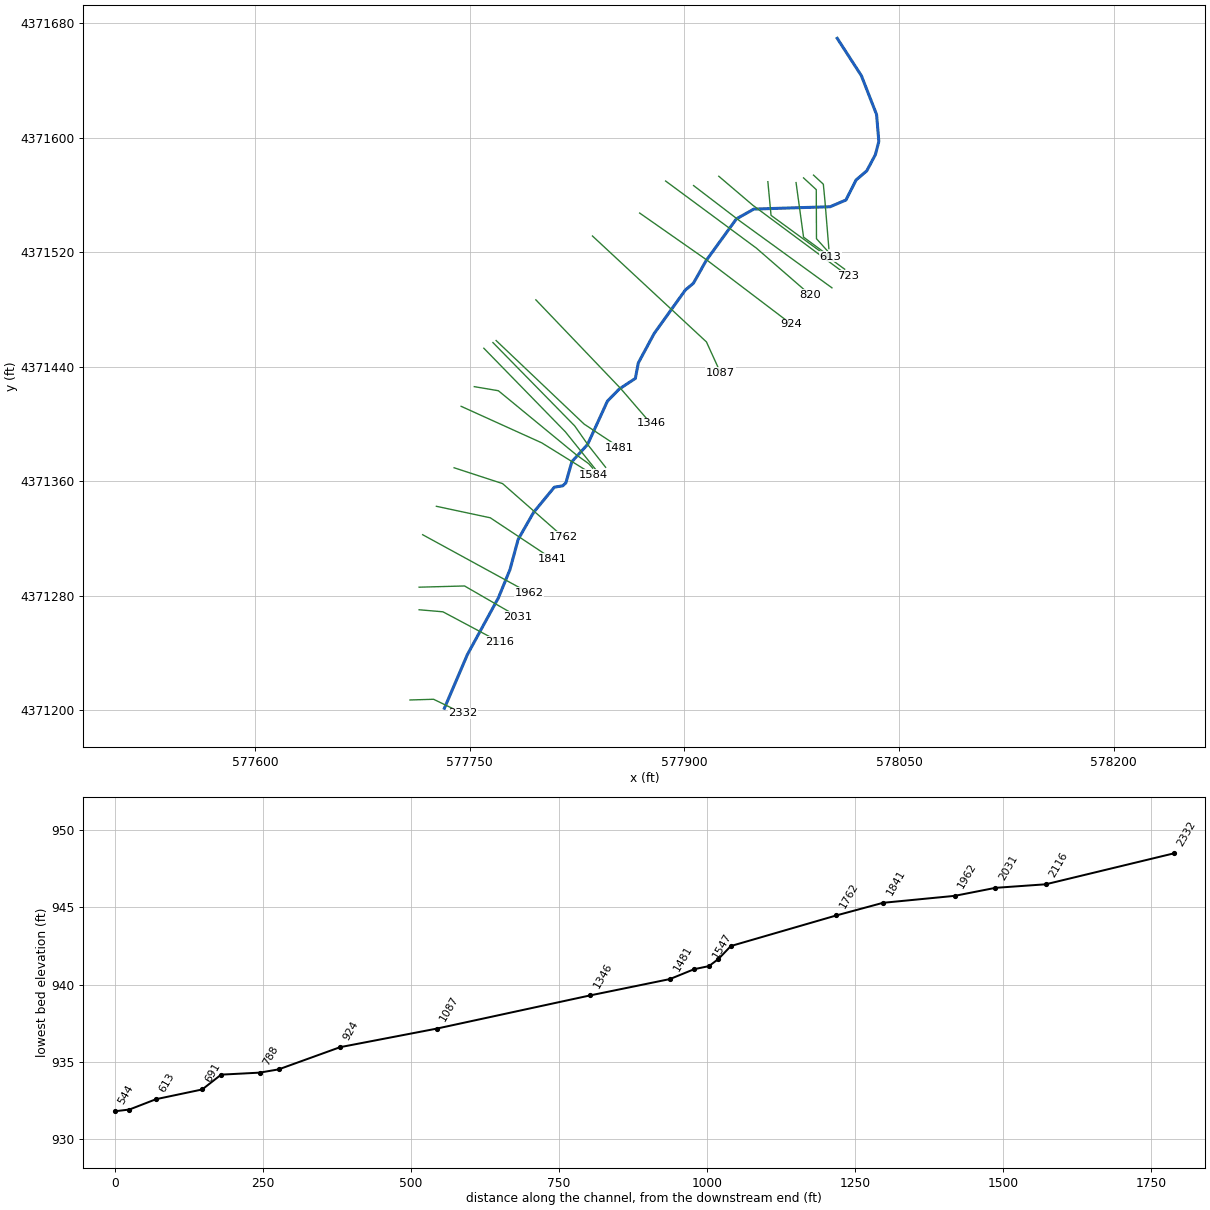
--- ScratchersRun.prj (project) ---

Proj Title=Scratchers Run
Current Plan=p01
Default Exp/Contr=0.3,0.1
English Units
Geom File=g01
Flow File=f01
Flow File=f02
Plan File=p01
Plan File=p02
Y Axis Title=Elevation
X Axis Title(PF)=Main Channel Distance
X Axis Title(XS)=Station
BEGIN DESCRIPTION:
Detailed Study for Scratchers Run
Upper Monongahela Watershed, Marion County, WV
Submitted by RAMPP for FEMA Region III
Model date: October 2015
HEC-RAS version 4.1.0
Vertical Datum: NAVD88 (feet)
Horizontal Datum: NAD_1983_UTM_Zone_17N
END DESCRIPTION:
DSS Export Rating Curves= 0
DSS Export Rating Curve Sorted= 0
DSS Export Volume Flow Curves= 0
DXF Filename=..\..\..\..\..\DETAILED\Basin_HUC_Stream\HEC-RAS\Scratchers Run\ScratchersRun.
DXF OffsetX= 0
DXF OffsetY= 0
DXF ScaleX= 1
DXF ScaleY= 10

--- ScratchersRun.p01 (plan) ---

Plan Title=Scratchers Run - Multiprofile
Program Version=4.10
Short Identifier=Multiprofile
Geom File=g01
Flow File=f01
Subcritical Flow
K Sum by GR= 0
Std Step Tol= 0.01
Critical Tol= 0.01
Num of Std Step Trials= 20
Max Error Tol= 0.3
Flow Tol Ratio= 0.001
Split Flow NTrial= 30
Split Flow Tol= 0.02
Split Flow Ratio= 0.02
Log Output Level= 0
Friction Slope Method= 1
Unsteady Friction Slope Method= 2
Unsteady Bridges Friction Slope Method= 1
Parabolic Critical Depth
Global Vel Dist= 0 , 0 , 0
Global Log Level= 0
CheckData=True
Encroach Param=-1 ,0,0, 0
Computation Interval=1HOUR
Output Interval=1HOUR
Run HTab= 0
Run UNet= 0
Run PostProcess= 0
Run WQNet= 0
UNET Theta= 1
UNET Theta Warmup= 1
UNET ZTol= 0.02
UNET ZSATol= 0.05
UNET MxIter= 20
UNET MaxInSteps= 0
UNET DtIC= 0
UNET DtMin= 0
UNET MaxCRTS= 20
UNET WFStab= 2
UNET SFStab= 1
UNET WFX= 1
UNET SFX= 1
UNET DSS MLevel= 4
UNET DZMax Abort= 98.43
UNET Convert EG Bridges= 0
UNET Use Existing IB Tables=-1
UNET Froude Reduction=False
UNET Froude Limit= 1
UNET Froude Power= 10
UNET Time Slicing=0,0, 5
UNET Junction Losses=0
Instantaneous Interval=1HOUR
DSS File=dss
Write IC File= 0
Write IC File at Sim End=0
Echo Input=False
Echo Parameters=False
Echo Output=False
Write Detailed= 0
WQ AD Non Conservative
WQ ULTIMATE=-1
WQ Max Comp Step=1HOUR
WQ Output Interval=15MIN
WQ Output Selected Increments= 0
WQ Output face flow=0
WQ Output face velocity=0
WQ Output face area=0
WQ Output face dispersion=0
WQ Output cell volume=0
WQ Output cell surface area=0
WQ Output cell continuity=0
WQ Output cumulative cell continuity=0
WQ Output face conc=0
WQ Output face dconc_dx=0
WQ Output face courant=0
WQ Output face peclet=0
WQ Output face adv mass=0
WQ Output face disp mass=0
WQ Output cell mass=0
WQ Output cell source sink temp=0
WQ Output cell source sink nsm=0
WQ Output MaxMinRange=-1
WQ Daily Max Min Mean=-1
WQ Daily Range=0
WQ Daily Time=0
WQ Create Restart=0
WQ Fixed Restart=0
WQ System Summary=0
WQ Use Fixed Temperature=0
Sorting and Armoring Iterations= 10
XS Update Threshold= 0.02
Hydraulics Update Threshold= 0.02
Energy Slope Method= 1
Volume Change Method= 0
XS Weighting Method= 0
Number of US Weighted Cross Sections= 1
Number of DS Weighted Cross Sections= 1
Upstream XS Weight=0.25
Main XS Weight=0.5
Downstream XS Weight=0.25
Number of DS XS's Weighted with US Boundary= 1
Upstream Boundary Weight= 1
Weight of XSs Associated with US Boundary= 0
Number of US XS's Weighted with DS Boundary= 1
Downstream Boundary Weight= 0.5
Weight of XSs Associated with DS Boundary= 0.5
Sediment Output Level= 4
Mass or Volume Output= 0
Output Increment Type= 1
Profile and TS Output Increment= 10
XS Output Flag= 0
XS Output Increment= 10
Disregard all LS=0
Disregard all Conn=0
Disregard all Breaches=0
Disregard all Pumps=0

--- ScratchersRun.p02 (plan) ---

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Plan Title=Scratchers Run - Floodway
Short Identifier=Floodway
Geom File=g01
Flow File=f02
Encroach Param=-1 ,0,0, 2
Encroach River=Scratchers Run
Encroach Reach=Reach 1
Encroach Node=2332
       1     -18       9
Encroach Node=2116
       1     -22     8.2
Encroach Node=2031
       1     -15    12.1
Encroach Node=1962
       1  -28.38   15.62
Encroach Node=1841
       1   -16.4      21
Encroach Node=1762
       1  -26.64   20.18
Encroach Node=1584
       1   -40.5    18.6
Encroach Node=1563
       1   -48.1      13
Encroach Node=1547
       1  -98.33      12
Encroach Node=1522
       1  -75.03   12.46
Encroach Node=1481
       1  -85.14   11.09
Encroach Node=1346
       1  -65.29   16.13
Encroach Node=1087
       1  -78.48   52.79
Encroach Node=924
       1  -29.59   81.59
Encroach Node=820
       1  -46.95   46.92
Encroach Node=788
       1  -15.08   23.52
Encroach Node=723
       1     -17   12.52
Encroach Node=691
       1    -8.9   13.27
Encroach Node=613
       1   -8.04    13.5
Encroach Node=568
       1  -21.21   30.57
Encroach Node=544
       1     -28      30
Encroach Node=504
       1  -21.47    9.56
Encroach Node=420
       1  -18.21      20
Encroach Node=339
       1   -8.89     9.5
Encroach Node=232
       1   -11.5   10.85
Encroach Node=65
       1     -19    17.8

--- ScratchersRun.f01 (steady flow) ---

Flow Title=Scratchers Run - Multiprofile
Program Version=4.10
Number of Profiles= 6
Profile Names=10PCT,4PCT,2PCT,1PCT,1PCT_PLUS,0.2PCT
River Rch & RM=Scratchers Run,Reach 1         ,2332
     506     672     807     947    1255    1304
River Rch & RM=Scratchers Run,Reach 1         ,1841
     525     696     835     980    1298    1349
River Rch & RM=Scratchers Run,Reach 1         ,1346
     529     702     843     989    1310    1360
River Rch & RM=Scratchers Run,Reach 1         ,691
     530     703     844     990    1312    1362
River Rch & RM=Scratchers Run,Reach 1         ,420
     531     704     845     991    1313    1364
Boundary for River Rch & Prof#=Scratchers Run,Reach 1         , 1
Up Type= 0
Dn Type= 3
Dn Slope=0.008
Boundary for River Rch & Prof#=Scratchers Run,Reach 1         , 2
Up Type= 0
Dn Type= 3
Dn Slope=0.008
Boundary for River Rch & Prof#=Scratchers Run,Reach 1         , 3
Up Type= 0
Dn Type= 3
Dn Slope=0.008
Boundary for River Rch & Prof#=Scratchers Run,Reach 1         , 4
Up Type= 0
Dn Type= 3
Dn Slope=0.008
Boundary for River Rch & Prof#=Scratchers Run,Reach 1         , 5
Up Type= 0
Dn Type= 3
Dn Slope=0.008
Boundary for River Rch & Prof#=Scratchers Run,Reach 1         , 6
Up Type= 0
Dn Type= 3
Dn Slope=0.008
DSS Import GetInterval= 0
DSS Import GetPeak= 0
DSS Import FillOption= 0

--- ScratchersRun.f02 (steady flow) ---

Flow Title=Scratchers Run - Floodway
Program Version=4.10
Number of Profiles= 2
Profile Names=1PCT,FLOODWAY
River Rch & RM=Scratchers Run,Reach 1         ,2332
     947     947
River Rch & RM=Scratchers Run,Reach 1         ,1841
     980     980
River Rch & RM=Scratchers Run,Reach 1         ,1346
     989     989
River Rch & RM=Scratchers Run,Reach 1         ,691
     990     990
River Rch & RM=Scratchers Run,Reach 1         ,420
     991     991
Boundary for River Rch & Prof#=Scratchers Run,Reach 1         , 1
Up Type= 0
Dn Type= 3
Dn Slope=0.008
Boundary for River Rch & Prof#=Scratchers Run,Reach 1         , 2
Up Type= 0
Dn Type= 3
Dn Slope=0.008
DSS Import GetInterval= 0
DSS Import GetPeak= 0
DSS Import FillOption= 0

--- ScratchersRun.g01 (geometry) ---

Geom Title=Scratchers Run
Program Version=4.10

River Reach=Scratchers Run  ,Reach 1
Reach XY= 30
577732.4127601764371201.30276434577748.514734776 4371238.8791184
577770.1299318434371278.41564129577778.2263343434371298.18009274
577783.916036013 4371319.2070258577794.8156841484371338.26464603
577809.2619851264371355.80649585577815.0309347984371356.67212786
577817.2535364254371358.73562388577821.4856844774371373.58639447
577832.4395870134371385.57204502577846.3302375844371415.89354939
577854.5598376864371424.29962869577865.8310370254371431.76082799
577867.8948378514371442.55592972577879.0072363884371463.19332837
577900.7562406574371493.51483275577906.4011367274371498.24441441
577915.307088037 4371514.0806034577936.4208890984371543.21125416
577948.6451980494371550.06925425578001.9419171084371551.71029747
578012.9384916444371556.38745353578020.070202132 4371570.3896609
578027.4786710234371576.73955938578033.5640030984371588.11682912
578035.9454055284371597.37726283578034.3577023084371616.16269667
578023.747614177 4371643.2737426578006.8842491694371669.36309892

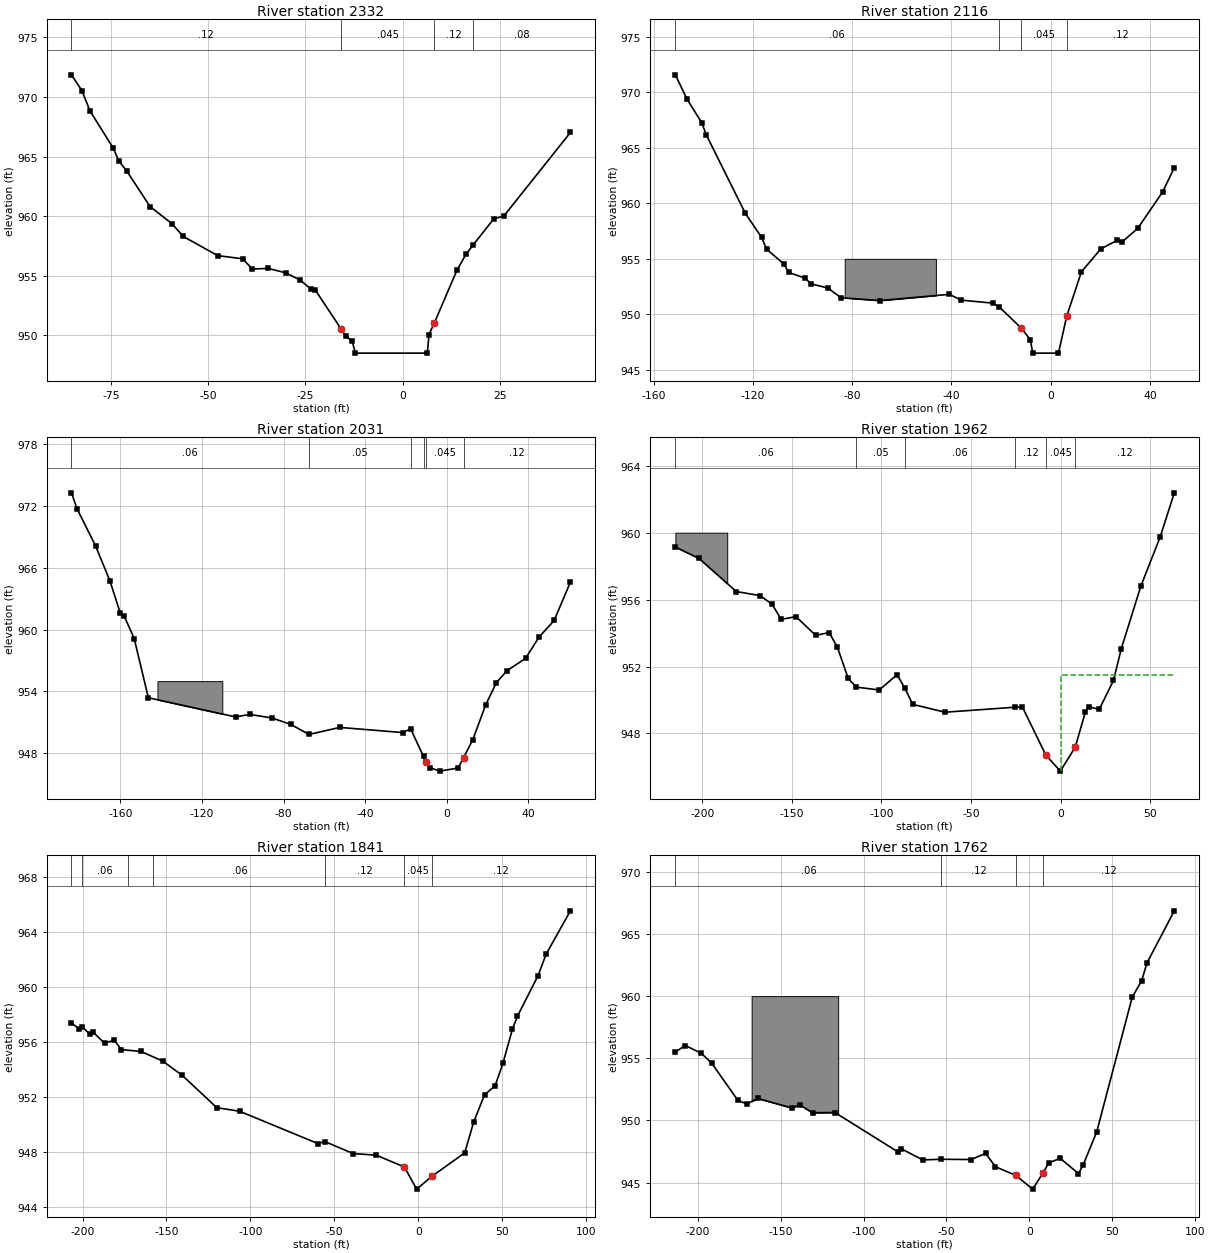
Type RM Length L Ch R = 1 ,2332    ,221.87,216,215.5
XS GIS Cut Line= 3
577708.3808038794371207.08207721577724.8729224834371207.56731881
577745.2107027354371197.71587789
#Sta/Elev= 30
 -85.105  971.86 -82.415  970.53 -80.381  968.85 -74.377  965.71 -72.933  964.63
 -70.932   963.8 -64.895   960.8 -59.219  959.35 -56.365  958.29 -47.474  956.68
 -41.076  956.42 -38.648  955.56 -34.482  955.61 -30.052  955.24 -26.378  954.64
 -23.655  953.91 -22.507  953.83 -15.846  950.55 -14.633  949.94 -12.959  949.51
 -12.139   948.5   6.365   948.5   6.791  950.06   8.202  951.06  13.976  955.46
  16.306   956.8  18.045  957.54  23.458  959.78  26.017     960  43.143  967.02
#Mann= 4 ,-1 , 0
 -85.105     .12       0 -15.846    .045       0   8.202     .12       0
  18.045     .08       0
Bank Sta=-15.846,8.202
XS Rating Curve= 0 ,0
Exp/Cntr=0.3,0.1

Type RM Length L Ch R = 1 ,2116    ,87.75,85,84.23
XS GIS Cut Line= 3
577714.7307023584371270.10587879577731.3816217644371268.68612037
577770.7697070514371247.72228091
#Sta/Elev= 30
-151.345  971.59-146.719  969.42-140.682  967.26-138.911  966.19 -123.13   959.1
-116.601  956.94-114.567  955.87-107.644  954.55 -105.61  953.77 -98.885  953.25
 -96.785  952.75 -89.797  952.37 -84.613   951.5 -68.865  951.24 -40.814   951.8
 -36.155  951.28 -23.425  951.01 -20.801  950.68     -12 948.788  -8.202  947.72
  -7.218   946.5    3.15   946.5     6.5  949.85  12.402  953.83  20.243   955.9
  26.772  956.66  28.609  956.49  35.138  957.75  45.112  961.02  49.869  963.22
#Mann= 4 ,-1 , 0
-151.345     .06       0 -20.801     .12       0     -12    .045       0
     6.5     .12       0
#Block Obstruct= 1 ,-1
 -83.071 -46.293     955
Bank Sta=-12,6.5
XS Rating Curve= 0 ,0
Exp/Cntr=0.3,0.1

Type RM Length L Ch R = 1 ,2031    ,66.73,69,68.92
XS GIS Cut Line= 3
577714.7477711584371285.88507018577746.4978731514371286.73149979
577783.5396080084371265.35313233
#Sta/Elev= 30
-183.924  973.27-181.201  971.72-172.146  968.13-165.125  964.75-160.039  961.62
-158.136  961.33-153.182  959.13 -146.26  953.39 -103.51  951.53 -96.654  951.77
 -85.728  951.43 -76.444   950.8  -67.52  949.83 -52.395  950.51 -21.621  950.01
 -17.717  950.37 -11.385  947.69 -10.302  947.15  -8.268  946.61   -3.43  946.27
   5.545  946.57   8.268  947.59  12.762  949.32  19.094  952.71  24.311  954.85
  29.495  956.01  38.615  957.21  45.177  959.26  52.625  960.89  60.597  964.61
#Mann= 6 ,-1 , 0
-183.924     .06       0  -67.52     .05       0 -17.717     .06       0
 -11.385     .12       0 -10.302    .045       0   8.268     .12       0
#Block Obstruct= 1 ,-1
-141.798-110.007     955
Bank Sta=-10.302,8.268
XS Rating Curve= 0 ,0
Exp/Cntr=0.3,0.1

Type RM Length L Ch R = 1 ,1962    ,124.17,121,117.69
XS GIS Cut Line= 2
577717.2178703894371322.54641464 577791.724707314371281.85348053
#Sta/Elev= 30
-215.026  959.14-201.969  958.47-181.004  956.48-167.815  956.24-161.024  955.72
-156.037  954.82-147.671  954.98-136.713  953.86-129.232  954.03-124.639  953.17
 -118.57  951.29-114.042  950.77 -101.28   950.6 -91.273  951.51 -86.909   950.7
 -82.546  949.74 -64.534  949.27 -25.295  949.57 -21.358  949.59  -8.202   946.7
    -.11  945.75   8.235   947.2   13.78  949.27  15.617   949.6  21.555  949.44
  29.528  951.17  33.891  953.07  44.783   956.8  55.577  959.74  63.484  962.38
#Mann= 6 ,-1 , 0
-215.026     .06       0-114.042     .05       0 -86.909     .06       0
 -25.295     .12       0  -8.202    .045       0   8.235     .12       0
#XS Ineff= 2 , 0
       0  -91.27  951.51               0
Permanent Ineff=
       F       F
#Block Obstruct= 1 ,-1
-215.026-186.089     960
Bank Sta=-8.202,8.235
XS Rating Curve= 0 ,0
Exp/Cntr=0.3,0.1

Type RM Length L Ch R = 1 ,1841    ,86.96,79,75.39
XS GIS Cut Line= 3
577726.8172417074371342.40443968577764.4938749734371334.36107238
577807.8855083094371305.57454083
#Sta/Elev= 30
-206.562  957.38  -202.1  956.99-200.066  957.12-195.702  956.57-193.537  956.71
-186.844  955.92-181.201  956.14-176.772  955.46-165.157  955.32-152.329  954.63
 -140.65  953.59 -119.98  951.23 -106.43  950.97  -59.81  948.62 -55.643  948.76
  -38.78  947.89 -24.967  947.77  -8.235  946.91    -.92   945.3   8.235  946.24
   27.69  947.94  33.104   950.2  39.534  952.17  45.833  952.83  50.459  954.45
  56.102  956.93  59.088  957.88  71.424  960.85   76.28  962.42  90.682  965.56
#Mann= 7 ,-1 , 0
-206.562     .05       0-200.098     .06       0-172.966     .05       0
 -157.71     .06       0 -55.381     .12       0  -8.235    .045       0
   8.235     .12       0
Bank Sta=-8.235,8.235
XS Rating Curve= 0 ,0
Exp/Cntr=0.3,0.1

Type RM Length L Ch R = 1 ,1762    ,157.89,178,175.02
XS GIS Cut Line= 3
 577739.178405864371369.32498561577773.0450390794371358.26531748
   577815.2196064371321.22358262
#Sta/Elev= 30
-213.583  955.51-207.677  956.03-197.999  955.41-191.732  954.62-175.951  951.63
-170.538  951.33-163.944  951.77 -143.34  951.01-138.484  951.25 -130.84  950.62
-117.323  950.64 -79.101  947.46 -77.231  947.72 -64.304  946.83 -53.084  946.88
 -35.203  946.86 -26.411  947.35  -20.44  946.28  -8.268  945.59    2.02  944.48
   8.268  945.79  11.713  946.59  18.602  946.96  29.626  945.73  32.448  946.42
   40.65  949.09  62.073  959.92  67.815  961.25  70.997  962.68  87.467  966.86
#Mann= 4 ,-1 , 0
-213.583     .06       0 -53.084     .12       0  -8.268    .045       0
   8.268     .12       0
#Block Obstruct= 1 ,-1
-167.585-115.354     960
Bank Sta=-8.268,8.268
XS Rating Curve= 0 ,0
Exp/Cntr=0.3,0.1

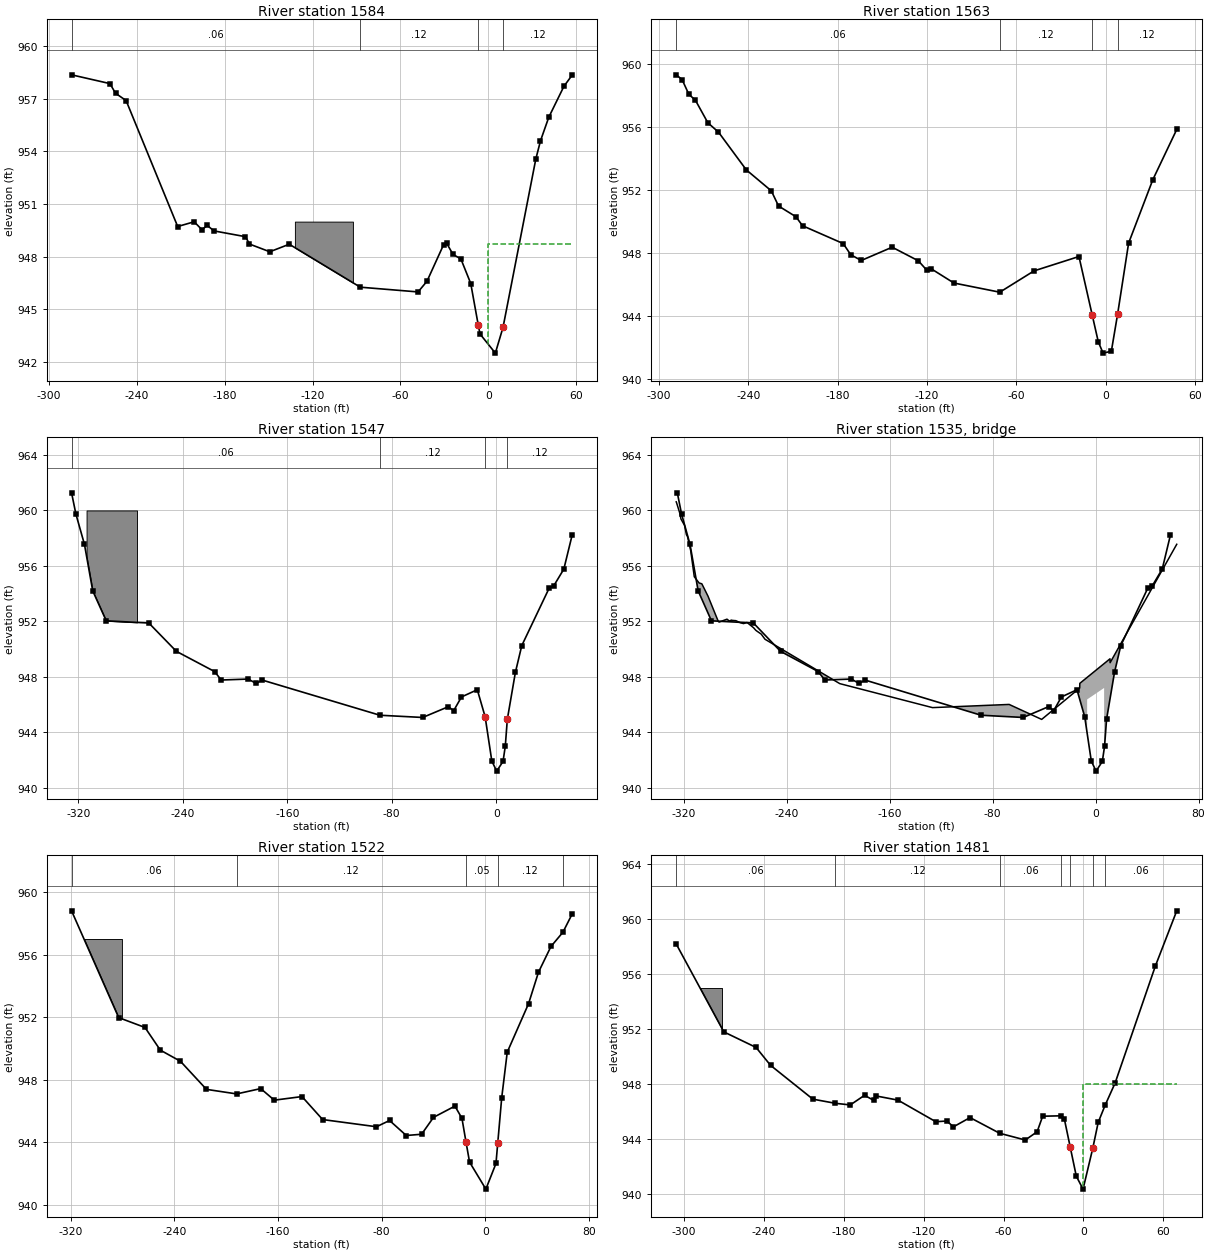
Type RM Length L Ch R = 1 ,1584    ,30.08,21,20.61
XS GIS Cut Line= 3
577744.0945251214371412.25454214577800.4508266174371386.72236023
 577836.302012664371364.49725835
#Sta/Elev= 30
 -284.35  958.37-258.202  957.87-254.364  957.32-247.146   956.9-211.975  949.72
-200.722  949.99 -195.44  949.54-191.765  949.78-187.238  949.47-165.715  949.14
-162.992  948.72-149.147  948.28 -135.86  948.71 -87.402  946.26 -47.999  945.99
 -41.929   946.6  -30.61  948.68 -28.478  948.76  -24.18  948.13 -18.799  947.87
 -12.073  946.47      -7 944.118  -5.741  943.59     4.7   942.5   9.941  943.97
  32.283  953.56  35.466   954.6  41.142  955.95  51.509  957.72  57.054  958.35
#Mann= 4 ,-1 , 0
 -284.35     .06       0 -87.402     .12       0      -7    .045       0
   9.941     .12       0
#XS Ineff= 2 , 0
       0 -135.86  948.71               0
Permanent Ineff=
       F       F
#Block Obstruct= 2 ,-1
-259.678-212.828     950-132.021 -92.454     950
Bank Sta=-7,9.941
XS Rating Curve= 0 ,0
Exp/Cntr=0.3,0.1

Type RM Length L Ch R = 1 ,1563    ,30.23,16,12.06
BEGIN DESCRIPTION:
(Channel from survey data SCR_03)
END DESCRIPTION:
XS GIS Cut Line= 5
577753.3071052354371425.99888872577770.1345038434371423.14138868
577824.8326933194371378.17089132577833.2994278234371372.13828965
577836.0161102574371369.00738401
#Sta/Elev= 30
 -288.32  959.29-284.383  958.99-279.856  958.06-275.427  957.68 -267.06  956.25
-259.941  955.66-241.273  953.27-224.475  951.94-219.619  950.98 -207.94   950.3
 -203.51  949.73-176.214   948.6-171.129  947.89-164.075  947.53 -143.34  948.37
-125.787  947.51 -119.98   946.9-117.421  947.02 -101.87   946.1 -71.096  945.52
 -48.097  946.87 -17.946  947.78      -9 944.055  -4.954  942.37  -1.739  941.66
   3.806  941.78       8 944.127  15.387  948.63   31.66  952.65  47.703  955.83
#Mann= 4 ,-1 , 0
 -288.32     .06       0 -71.096     .12       0      -9    .045       0
       8     .12       0
#XS Ineff= 2 , 0
       0 -143.34                       0
Permanent Ineff=
       F       F
Bank Sta=-9,8
XS Rating Curve= 0 ,0
Exp/Cntr=0.5,0.3

Type RM Length L Ch R = 1 ,1547    ,26.056,25,21.746
BEGIN DESCRIPTION:
US of Private driveway
END DESCRIPTION:
XS GIS Cut Line= 3
577759.9746053174371452.82768985577816.9658052214371394.40758752
577839.0321062944371366.94358318
#Sta/Elev= 30
 -325.23  961.27-321.916  959.74-315.354  957.55-309.022   954.2-298.688  952.04
-266.043  951.88 -244.98  949.84-215.682  948.38-210.597  947.77-189.928  947.84
-183.858  947.52-179.331  947.77 -89.075  945.23 -56.332  945.07 -36.581  945.85
 -32.644  945.55 -26.608  946.55 -14.501  947.07  -8.497  945.12   -3.38  941.93
     .34   941.2    5.21   941.9    6.93  942.99   8.497  944.94  14.665  948.32
  19.554  950.25  40.453  954.38  44.094  954.57  51.772  955.77  58.104  958.21
#Mann= 4 ,-1 , 0
 -325.23     .06       0 -89.075     .12       0  -8.497    .045       0
   8.497     .12       0
#XS Ineff= 2 , 0
       0    -136                       0
Permanent Ineff=
       F       F
#Block Obstruct= 1 ,-1
-313.747-275.098     960
Bank Sta=-8.497,8.497
XS Rating Curve= 0 ,0
Exp/Cntr=0.5,0.3

Type RM Length L Ch R = 3 ,1535    ,,,
BEGIN DESCRIPTION:
Private driveway (Surveyed Structure SCR_03)
END DESCRIPTION:
Bridge Culvert--1,0,-1,-1, 0
Deck Dist Width WeirC Skew NumUp NumDn MinLoCord MaxHiCord MaxSubmerge Is_Ogee
3,10.9,2.6,0, 40, 40, , , 0.98, 0, 0,0,,
-326.083-325.722-323.261-322.375-321.161-319.587-318.143-317.323-316.109-314.797
-312.041-308.301-306.168-301.378 -293.34-292.684-286.581 -284.81-283.235-282.382
-279.724-276.181-273.753-270.997-265.945-264.239-263.386-259.974-257.054-198.917
-126.837 -67.257 -41.962   -12.4 -12.303    -6.6     6.6  11.155   11.25  63.058
  960.62  960.53  959.79  959.38  959.18  958.92  958.25  958.12  957.64  957.09
  955.22  954.77  954.71  953.82  951.99  951.95  952.16  952.02  952.09  952.07
  952.05   951.9  951.84  951.92  951.54  951.36   951.3  951.08  950.71  947.51
  945.78  946.01  944.93  947.19  947.53947.9603948.9563   949.3  949.02  957.56
                                                                                
                                                                                
                                                                                
                                          946.37   947.2
-326.083-325.722-323.261-322.375-321.161-319.587-318.143-317.323-316.109-314.797
-312.041-308.301-306.168-301.378 -293.34-292.684-286.581 -284.81-283.235-282.382
-279.724-276.181-273.753-270.997-265.945-264.239-263.386-259.974-257.054-198.917
-126.837 -67.257 -41.962   -12.4 -12.303    -6.6     6.6  11.155   11.25  63.058
  960.62  960.53  959.79  959.38  959.18  958.92  958.25  958.12  957.64  957.09
  955.22  954.77  954.71  953.82  951.99  951.95  952.16  952.02  952.09  952.07
  952.05   951.9  951.84  951.92  951.54  951.36   951.3  951.08  950.71  947.51
  945.78  946.01  944.93  947.19  947.53947.9603948.9563   949.3  949.02  957.56
                                                                                
                                                                                
                                                                                
                                          946.37   947.2
BR Coef=-1 , 1 , 0 ,, 0 ,,,0.8,0,1.2,0,
WSPro=,,,, 1 ,,,, 0 ,,,, 0 ,,,,-1 ,-1 ,-1 , 0 , 0 , 0 , 0 , 0
BC Design=,, 0 ,, 0 ,,,,,,
BC Use User HTab Curves=0
BC User HTab FreeFlow(D)= 0

Type RM Length L Ch R = 1 ,1522    ,23.56,41,44.54
BEGIN DESCRIPTION:
DS of Private driveway
END DESCRIPTION:
XS GIS Cut Line= 4
577766.324503796 4371456.7964907577823.4562165024371398.57024118
577832.9437262194371385.02553861577845.0647079694371369.64228242
#Sta/Elev= 30
-319.259   958.8-282.907  951.97-262.631  951.34-250.787  949.89-235.302  949.18
 -215.19  947.38-191.896  947.09 -173.36  947.43-162.861  946.69-141.503  946.92
-125.591  945.45 -84.055  944.99  -73.95  945.39 -61.056  944.43 -49.245  944.51
 -40.059  945.59 -23.524  946.31  -18.11  945.53     -15 944.021 -12.238  942.73
     .34     941   8.136  942.64     9.5 943.942  12.566  946.85  16.831  949.76
  33.268  952.86  40.912  954.87  50.558  956.52  59.777  957.43  66.864  958.59
#Mann= 5 ,-1 , 0
-319.259     .06       0-191.896     .12       0     -15     .05       0
     9.5     .12       0  59.777     .06       0
#XS Ineff= 2 , 0
       0    -139                       0
Permanent Ineff=
       F       F
#Block Obstruct= 1 ,-1
-315.748-280.413     957
Bank Sta=-15,9.5
XS Rating Curve= 0 ,0
Exp/Cntr=0.5,0.3

Type RM Length L Ch R = 1 ,1481    ,142.78,135,128.22
BEGIN DESCRIPTION:
(Channel from survey data SCR_03)
)
END DESCRIPTION:
XS GIS Cut Line= 3
577768.5471054234371458.22508831577830.0712909834371399.81382519
 577854.907309694371383.45368499
#Sta/Elev= 30
-305.807  958.18-270.046  951.79-245.833  950.66-234.974  949.36-203.182   946.9
-186.385   946.6-175.098  946.48 -164.37  947.18-157.448  946.81-155.545  947.13
-139.272  946.83 -110.86  945.26-102.592  945.31 -97.605  944.89 -85.138  945.56
 -62.894  944.42 -43.668  943.93 -34.777  944.53  -30.61  945.66 -16.601  945.69
  -14.37  945.48     -10 943.455  -5.348   941.3   -.295  940.36       7 943.321
  11.089  945.21  16.207  946.44  23.819  948.08  54.035  956.58  70.079  960.59
#Mann= 7 ,-1 , 0
-305.807     .06       0-186.385     .12       0 -62.894     .06       0
 -16.601     .08       0     -10     .05       0       7     .08       0
  16.207     .06       0
#XS Ineff= 2 , 0
       0    -131     948               0
Permanent Ineff=
       F       F
#Block Obstruct= 1 ,-1
 -305.02-271.096     955
Bank Sta=-10,7
XS Rating Curve= 0 ,0
Exp/Cntr=0.3,0.1

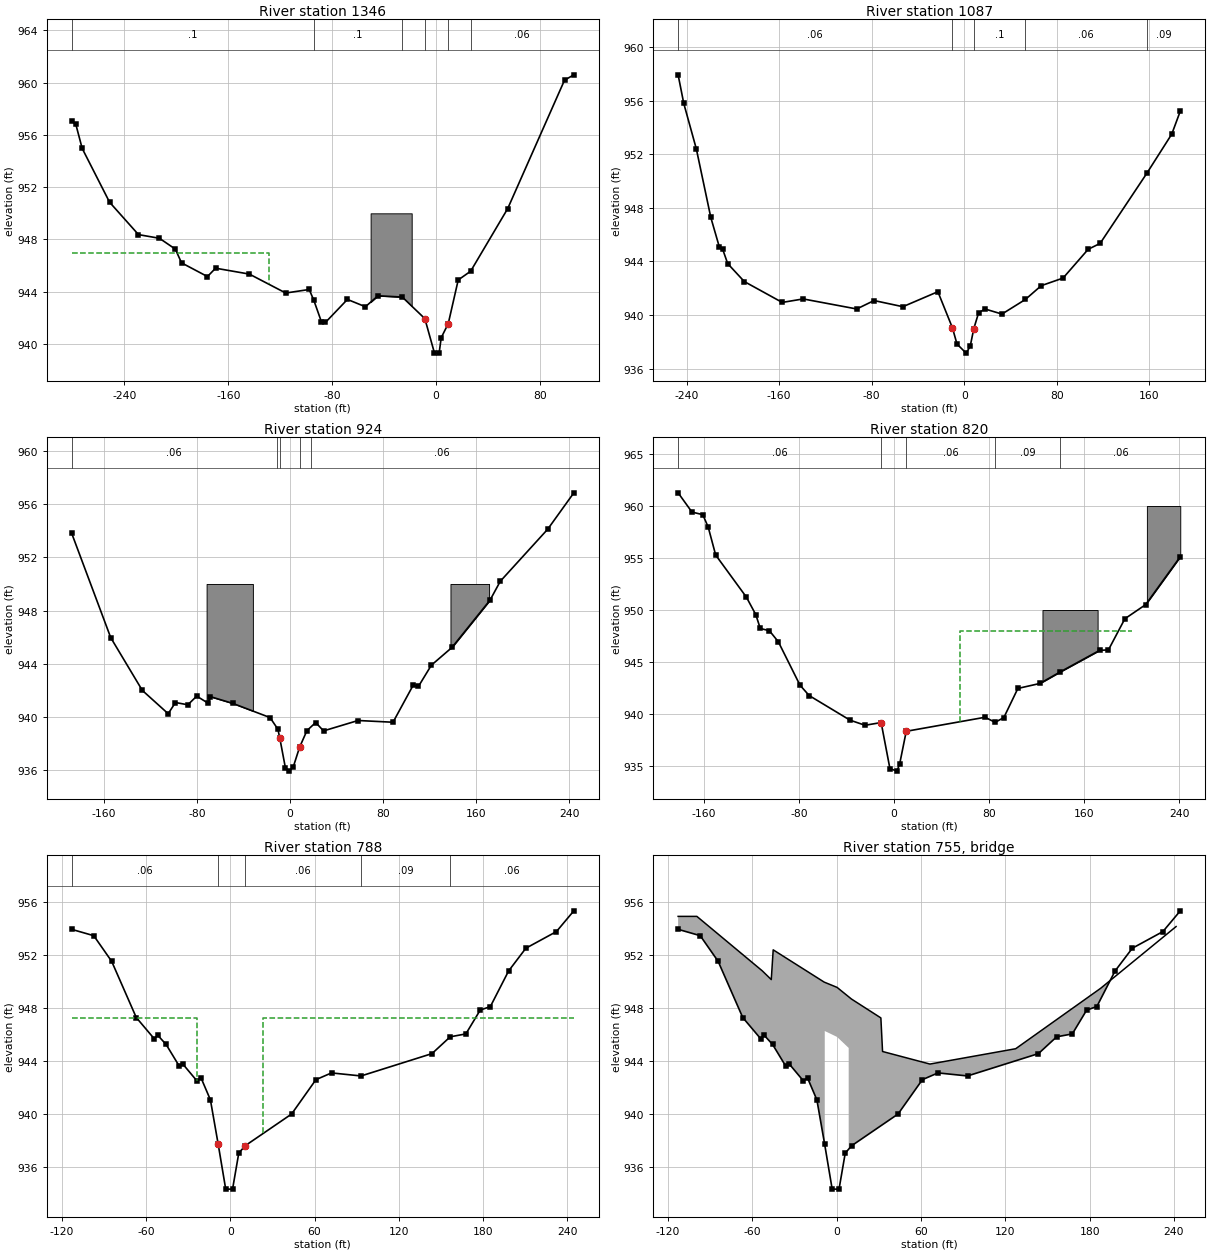
Type RM Length L Ch R = 1 ,1346    ,245.16,259,251.63
XS GIS Cut Line= 3
577796.3284065664371486.64128786577855.383407296 4371424.8875879
577876.656009159 4371400.2813884
#Sta/Elev= 30
-280.676  957.03-277.559  956.85-272.572  954.97-251.444  950.85-229.167  948.37
-213.025  948.09-200.755  947.26-195.997  946.21-176.017  945.16-169.751   945.8
-143.734  945.35-115.682   943.9 -97.605  944.17 -94.127  943.37 -88.255  941.72
 -85.072  941.65 -68.143  943.41 -54.265  942.85 -44.587  943.69  -25.82  943.59
  -8.465  941.94   -1.04   939.3    2.54   939.3    4.14  940.48    9.58  941.56
  17.257   944.9  26.837  945.57  55.381  950.36   99.18  960.19 106.365   960.6
#Mann= 6 ,-1 , 0
-280.676      .1       0 -94.127      .1       0  -25.82      .1       0
  -8.465     .04       0    9.58      .1       0  26.837     .06       0
#XS Ineff= 1 ,-1
-280.676 -128.71     947
Permanent Ineff=
       F
#Block Obstruct= 1 ,-1
 -50.262 -18.602     950
Bank Sta=-8.465,9.58
XS Rating Curve= 0 ,0
Exp/Cntr=0.3,0.1

Type RM Length L Ch R = 1 ,1087    ,153.98,163,166.21
XS GIS Cut Line= 3
577835.8573094554371531.25029242577915.491796839 4371457.2603963
 577925.281668164371435.82899364
#Sta/Elev= 30
-247.277  957.95-242.388  955.81-231.529  952.41-219.029  947.29-211.614  945.07
-208.924  944.95-204.429  943.84-190.092   942.5-157.316  940.94-139.206   941.2
 -92.946  940.45 -77.953  941.08 -53.051  940.62 -22.802  941.74 -10.236  939.04
  -6.299  937.83   1.608  937.15   5.118  937.66   8.235  938.98  12.369  940.16
  17.848  940.45  32.579  940.07  52.789  941.16   66.47  942.19  85.367  942.76
 107.054  944.91 117.388  945.35 157.743  950.59 179.298  953.52  186.68  955.24
#Mann= 5 ,-1 , 0
-247.277     .06       0 -10.236    .045       0   8.235      .1       0
  52.789     .06       0 157.743     .09       0
Bank Sta=-10.236,8.235
XS Rating Curve= 0 ,0
Exp/Cntr=0.3,0.1

Type RM Length L Ch R = 1 ,924     ,107.08,104,105.89
XS GIS Cut Line= 3
577868.8412418634371547.29374541577915.6902216424371514.52744021
577974.8866495734371469.61180685
#Sta/Elev= 30
-187.566  953.81-154.003  945.97 -126.87  942.01-104.659  940.26 -98.392   941.1
 -87.762  940.93 -80.118  941.58 -70.571  941.06 -68.373  941.54 -49.016  941.03
 -17.159  939.97 -10.433   939.1  -8.825  938.45  -3.904  936.17   -.492  935.95
   2.887  936.29   8.202  937.74  14.534  938.99  22.047   939.6  28.806  938.97
  58.465  939.75  88.484  939.62 105.676  942.38 110.335  942.31 121.391   943.9
 139.075  945.23  171.85  948.79  180.61   950.2 221.358  954.11 243.799  956.84
#Mann= 5 ,-1 , 0
-187.566     .06       0 -11.319     .08       0  -8.825    .045       0
   8.202     .08       0  17.749     .06       0
#Block Obstruct= 2 ,-1
 137.828 170.997     950 -71.654  -31.89     950
Bank Sta=-8.825,8.202
XS Rating Curve= 0 ,0
Exp/Cntr=0.3,0.1

Type RM Length L Ch R = 1 ,820     ,34.92,32,33.08
BEGIN DESCRIPTION:
(Surveyed XS SCR_02)
END DESCRIPTION:
XS GIS Cut Line= 3
577886.9747084874371569.66789449 577950.316111674371522.83659311
577988.0808321364371490.03706471
#Sta/Elev= 30
-181.791  961.27-170.144  959.42-161.024  959.17-156.463  957.97-150.197  955.29
-124.344  951.24-116.437  949.56-112.664  948.23-104.987  948.01 -97.474  946.95
 -79.265  942.78 -71.555  941.78 -37.139  939.41 -24.475  938.92 -10.958  939.18
  -3.576  934.76   2.297  934.51    4.56  935.16  10.171  938.34  76.509  939.69
  84.974   939.2   92.29  939.66 104.101  942.46 122.638  942.94 139.895  944.06
 172.867  946.12 180.315  946.17 194.127  949.16 211.614  950.52 240.781  955.13
#Mann= 5 ,-1 , 0
-181.791     .06       0 -10.958    .045       0  10.171     .06       0
  84.974     .09       0 139.895     .06       0
#XS Ineff= 1 ,-1
      55     200     948
Permanent Ineff=
       F
#Block Obstruct= 2 ,-1
 124.803 171.194     950 212.664 240.748     960
Bank Sta=-10.958,10.171
XS Rating Curve= 0 ,0
Exp/Cntr=0.5,0.3

Type RM Length L Ch R = 1 ,788     ,54.47,65,49.586
BEGIN DESCRIPTION:
US of Firehouse Road
END DESCRIPTION:
XS GIS Cut Line= 3
577906.5011111284371566.49279285577939.1939595324371541.49340134
578003.1800147234371495.05529197
#Sta/Elev= 30
-112.901  953.95 -97.173  953.47 -84.416  951.53 -66.903  947.28 -54.176  945.68
 -51.649  945.94 -45.643  945.24 -36.395  943.62 -33.749  943.76 -23.758  942.49
 -20.784  942.71 -14.124  941.05    -8.6   937.7   -3.24   934.3    1.64   934.3
   6.066  937.03  10.734  937.59  43.651  939.98  60.985  942.58  72.077  943.09
  93.099  942.86 143.588  944.55 156.552  945.82 167.702  946.04 177.902  947.84
 185.157  948.11 198.121   950.8 210.401  952.52 232.167  953.78 244.566  955.35
#Mann= 5 ,-1 , 0
-112.901     .06       0    -8.6    .045       0  10.734     .06       0
  93.099     .09       0 156.552     .06       0
#XS Ineff= 2 ,-1
-112.901  -23.52  947.25   23.52 244.566  947.25
Permanent Ineff=
       F       F
Bank Sta=-8.6,10.734
XS Rating Curve= 0 ,0
Skew Angle= 25
Exp/Cntr=0.5,0.3

Type RM Length L Ch R = 3 ,755     ,,,
BEGIN DESCRIPTION:
Firehouse Road (Surveyed Structure SCR_02)
END DESCRIPTION:
Bridge Culvert--1,0,-1,-1, 0
Deck Dist Width WeirC Skew NumUp NumDn MinLoCord MaxHiCord MaxSubmerge Is_Ogee
12.75,28.4,2.6,25, 16, 16, , , 0.98, 0, 0,0,,
-112.899 -99.552 -52.987 -46.594 -45.227   -8.95  -8.519    .237   8.519  10.467
  31.429  32.627  66.367 127.382 187.862 241.563
  954.93  954.93  950.81  950.15   952.4  949.96 949.941  949.56 948.848  948.68
  947.25  944.71  943.76  944.92  949.49  954.16
                                                  946.26 945.814  944.98
                                                
-112.899 -99.552 -52.987 -46.594 -45.227   -8.95  -8.519    .237   8.519  10.467
  31.429  32.627  66.367 127.382 187.862 241.563
  954.93  954.93  950.81  950.15   952.4  949.96 949.941  949.56 948.848  948.68
  947.25  944.71  943.76  944.92  949.49  954.16
                                                  946.26 945.814  944.98
                                                
BR Coef=-1 , 0 , 0 ,, 0 ,,,0.8,-1,1.2,0,
WSPro=,,,, 1 ,,,, 0 ,,,, 0 ,,,,-1 ,-1 ,-1 , 0 , 0 , 0 , 0 , 0
BC Design=,, 0 ,, 0 ,,,,,,
BC Use User HTab Curves=0
BC User HTab FreeFlow(D)= 0

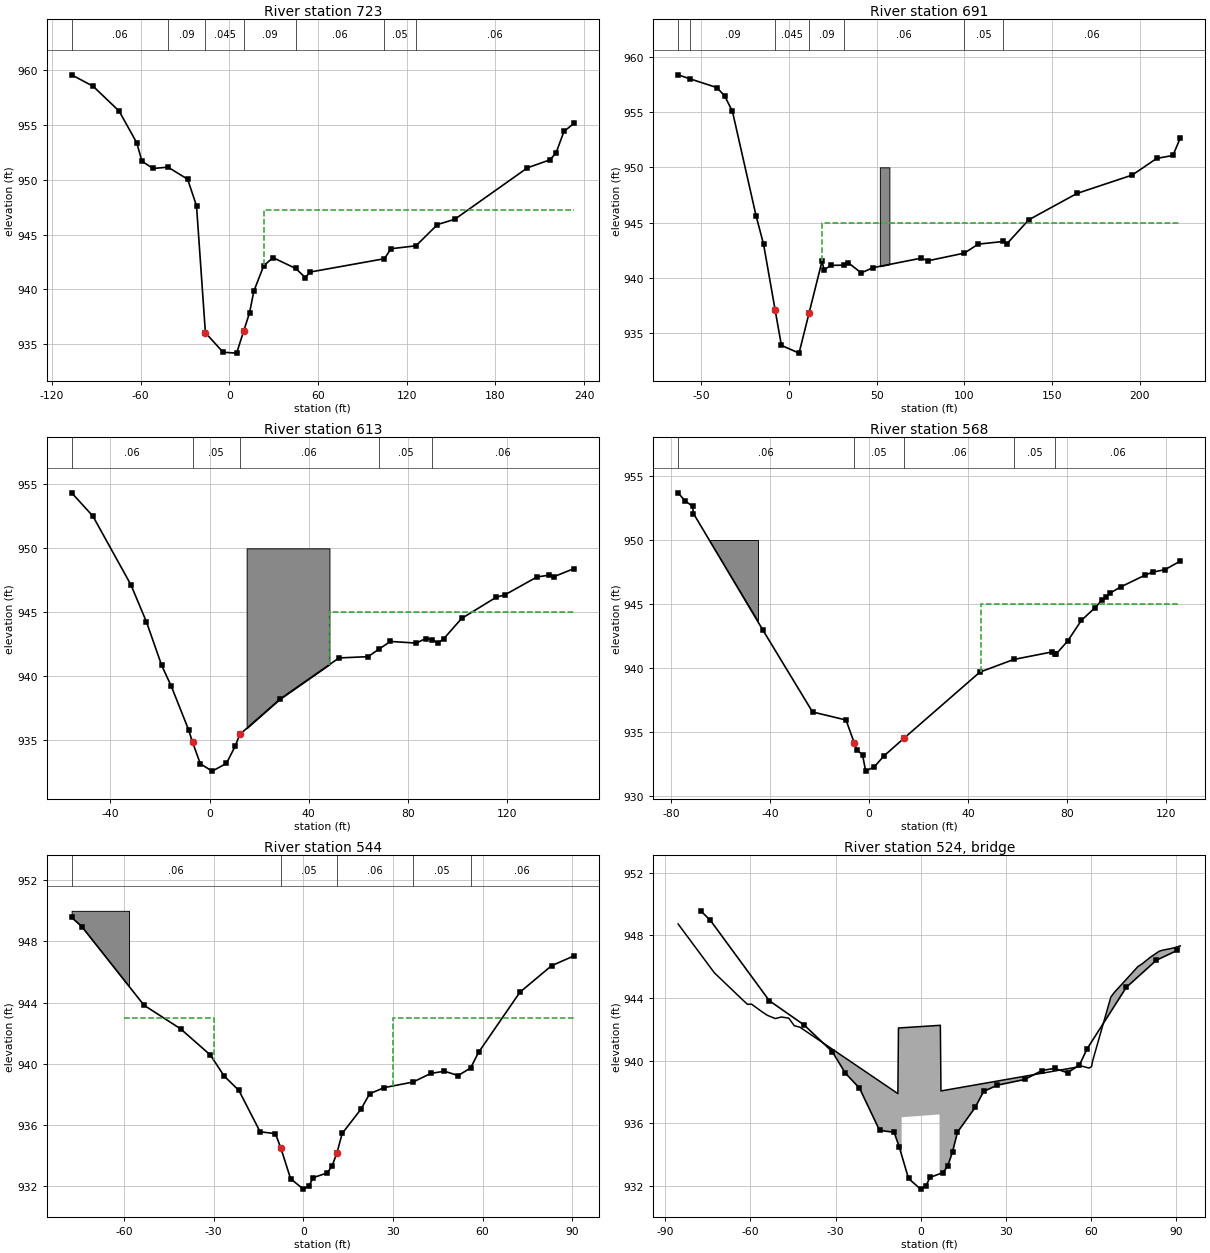
Type RM Length L Ch R = 1 ,723     ,45.4,32,11.37
BEGIN DESCRIPTION:
DS of Firehouse Road
END DESCRIPTION:
XS GIS Cut Line= 3
577924.1225137464371573.00149213577947.8112652394371552.82281748
578014.6100148644371503.31019047
#Sta/Elev= 30
-106.717  959.58 -92.147  958.53 -74.604  956.27  -62.74  953.39 -59.142  951.69
 -51.679  951.03 -41.539  951.15 -28.248  950.05 -22.242  947.62 -16.235  936.03
  -4.252  934.25   4.906  934.17     9.6 936.159  13.678  937.87  16.503  939.81
  23.193  942.14  29.497  942.89  44.869   941.9  51.441  941.06  54.444  941.57
 104.873  942.79 109.304   943.7 126.252  943.97 140.763  945.91 152.449  946.39
  201.63  951.09 216.883  951.82 221.017  952.46  226.34  954.41 233.029  955.14
#Mann= 7 ,-1 , 0
-106.717     .06       0 -41.539     .09       0 -16.235    .045       0
     9.6     .09       0  44.869     .06       0 104.873     .05       0
 126.252     .06       0
#XS Ineff= 2 ,-1
-106.717  -23.52  947.25   23.52 233.029  947.25
Permanent Ineff=
       F       F
Bank Sta=-16.235,9.6
XS Rating Curve= 0 ,0
Skew Angle= 25
Exp/Cntr=0.5,0.3

Type RM Length L Ch R = 1 ,691     ,77.46,78,48.73
BEGIN DESCRIPTION:
(Channel from survey data SCR_02)
END DESCRIPTION:
XS GIS Cut Line= 3
 577958.412514174371569.19149208577960.6436501974371545.67891499
578012.0701164334371508.07269053
#Sta/Elev= 30
 -63.255  958.36 -56.726  958.01 -41.175  957.21 -36.778  956.47 -32.283  955.07
 -18.766  945.61 -14.501  943.05    -7.9 937.105  -4.331  933.91   5.741  933.21
    11.5 936.861  18.832  941.51  20.046  940.73  23.786  941.14  31.332  941.16
  33.924  941.36   41.24  940.46  47.867  940.93  75.361  941.79  79.396  941.56
 100.098  942.25  107.94  943.06 122.375   943.3 124.442  943.11 136.811  945.26
 164.304  947.64 195.801   949.3 209.843  950.81 219.029  951.07 223.261  952.65
#Mann= 7 ,-1 , 0
 -63.255     .06       0 -56.726     .09       0    -7.9    .045       0
    11.5     .09       0  31.332     .06       0 100.098     .05       0
 122.375     .06       0
#XS Ineff= 1 ,-1
   18.83 223.261     945
Permanent Ineff=
       F
#Block Obstruct= 1 ,-1
  51.837  57.283     950
Bank Sta=-7.9,11.5
XS Rating Curve= 0 ,0
Exp/Cntr=0.5,0.3

Type RM Length L Ch R = 1 ,613     ,47.02,45,40.24
XS GIS Cut Line= 3
577978.1144816134371568.56634728577983.3533840784371530.46634681
578002.0857827094371516.65494424
#Sta/Elev= 30
  -55.61  954.34 -47.047  952.52 -31.693  947.14 -25.427  944.24 -19.291  940.84
 -15.453  939.23  -8.465  935.82  -6.857  934.84  -3.707  933.15    1.07  932.58
   6.791  933.18  10.367  934.54  12.205  935.45  28.346   938.2  52.198  941.43
  63.944  941.53  68.241  942.11  72.966  942.72  83.366  942.59  87.205  942.95
  89.862  942.87  91.962  942.58  94.455  942.93 101.673  944.52  115.65  946.18
 119.094  946.36 132.021  947.76 136.844   947.9 138.812  947.78 146.916  948.41
#Mann= 5 ,-1 , 0
  -55.61     .06       0  -6.857     .05       0  12.205     .06       0
  68.241     .05       0  89.862     .06       0
#XS Ineff= 1 ,-1
   48.36 146.916     945
Permanent Ineff=
       F
#Block Obstruct= 1 ,-1
  14.961   48.36     950
Bank Sta=-6.857,12.205
XS Rating Curve= 0 ,0
Exp/Cntr=0.3,0.1

Type RM Length L Ch R = 1 ,568     ,22.17,24,26.77
BEGIN DESCRIPTION:
(Surveyed XS SCR_01)
END DESCRIPTION:
XS GIS Cut Line= 4
577983.3533840784371571.84721452577992.2349513884371563.64413202
 577992.384912994371529.34529239578002.7039171174371517.91529225
#Sta/Elev= 30
 -77.067  953.69 -74.377  953.08  -71.26  952.64 -70.866  952.07 -42.848  942.95
 -22.802  936.54  -9.285  935.91      -6 934.137  -4.987  933.59  -2.625  933.18
  -1.345  931.91   2.198  932.26   5.971  933.09      14 934.466  44.751  939.66
  58.432  940.65  73.688  941.23  75.131  941.06  75.394  941.04  80.249  942.11
  85.728  943.71  91.175  944.69  94.062  945.31  95.702  945.52  97.178  945.83
 101.739  946.34 111.549  947.26   114.6  947.49  119.39  947.67 125.656  948.35
#Mann= 5 ,-1 , 0
 -77.067     .06       0      -6     .05       0      14     .06       0
  58.432     .05       0  75.131     .06       0
#XS Ineff= 1 ,-1
      45 125.656     945
Permanent Ineff=
       F
#Block Obstruct= 1 ,-1
 -77.067  -44.98     950
Bank Sta=-6,14
XS Rating Curve= 0 ,0
Exp/Cntr=0.5,0.3

Type RM Length L Ch R = 1 ,544     ,33.725,40,33.868
BEGIN DESCRIPTION:
US of Private driveway
END DESCRIPTION:
XS GIS Cut Line= 4
577990.3214169644371573.79549614577997.1785026494371567.44895046
577998.3404002634371555.26457031578001.0366610974371522.43608591
#Sta/Elev= 30
 -77.537  949.57 -74.146  948.97 -53.336  943.83 -41.066  942.28 -31.108  940.57
 -26.513   939.2  -21.55  938.25 -14.459  935.55  -9.341  935.43  -7.491  934.47
  -4.255  932.48       0   931.8    1.85     932   3.329  932.55   7.985  932.86
   9.588  933.29  11.284  934.19   13.01  935.44  19.299  937.03  22.228  938.04
    27.1  938.44  36.687   938.8   42.73  939.37  47.231  939.51  51.825  939.23
  55.987  939.72  58.639  940.74  72.511  944.68  83.087  946.41  90.547  947.05
#Mann= 5 ,-1 , 0
 -77.537     .06       0  -7.491     .05       0  11.284     .06       0
  36.687     .05       0  55.987     .06       0
#XS Ineff= 2 ,-1
      30  90.547     943     -60     -30     943
Permanent Ineff=
       F       F
#Block Obstruct= 1 ,-1
 -77.537  -58.33     950
Bank Sta=-7.491,11.284
XS Rating Curve= 0 ,0
Skew Angle= 20
Exp/Cntr=0.5,0.3

Type RM Length L Ch R = 3 ,524     ,,,
BEGIN DESCRIPTION:
Private driveway (Surveyed Structure SCR_01)
END DESCRIPTION:
Bridge Culvert--1,0,-1,-1, 0
Deck Dist Width WeirC Skew NumUp NumDn MinLoCord MaxHiCord MaxSubmerge Is_Ogee
11,11.6,2.8,20, 39, 39, , , 0.98, 0, 0,0,,
 -85.491 -72.697  -62.77 -61.043 -59.594 -55.956 -54.045 -53.798 -51.209 -49.081
 -46.491 -44.518 -42.546  -8.016    -7.8  -6.681  -6.672   6.672   6.681   6.968
   7.183  56.974  59.378  60.272  60.673  67.086  68.349  72.388  72.419   72.45
  76.612  78.215  80.866  84.042  85.152  88.204  89.191  89.591  91.565
  948.73  945.61  943.89   943.6  943.61  943.13   942.9  942.88  942.69  942.79
  942.72  942.23  942.14   937.9  942.09 942.103 942.103 942.257 942.257  942.26
  938.07  939.65  939.53  939.62     940  944.07  944.37  945.17  945.17  945.18
  946.01   946.2  946.59  946.98  947.05  947.16   947.2  947.22  947.33
                                                                                
                                                  936.39  936.57
                                                                                
                                                                        
 -93.978 -75.697  -65.77 -64.043 -62.594 -58.956 -57.045 -56.798 -54.209 -52.081
 -49.491 -47.518 -45.546 -11.016   -10.8  -9.681  -9.672   3.672   3.681   3.968
   4.183  53.974  56.378  57.272  57.673  64.086  65.349  69.388  69.419   69.45
  73.612  75.215  77.866  81.042  82.152  85.204  86.191  86.591  88.565
  948.73  945.61  943.89   943.6  943.61  943.13   942.9  942.88  942.69  942.79
  942.72  942.23  942.14   937.9  942.09 942.103 942.103 942.257 942.257  942.26
  938.07  939.65  939.53  939.62     940  944.07  944.37  945.17  945.17  945.18
  946.01   946.2  946.59  946.98  947.05  947.16   947.2  947.22  947.33
                                                                                
                                                  936.39  936.57
                                                                                
                                                                        
BR Coef=-1 , 1 , 0 ,, 0 ,,,0.8,0,1.2,0,
WSPro=,,,, 1 ,,,, 0 ,,,, 0 ,,,,-1 ,-1 ,-1 , 0 , 0 , 0 , 0 , 0
BC Design=,, 0 ,, 0 ,,,,,,
BC Use User HTab Curves=0
BC User HTab FreeFlow(D)= 0