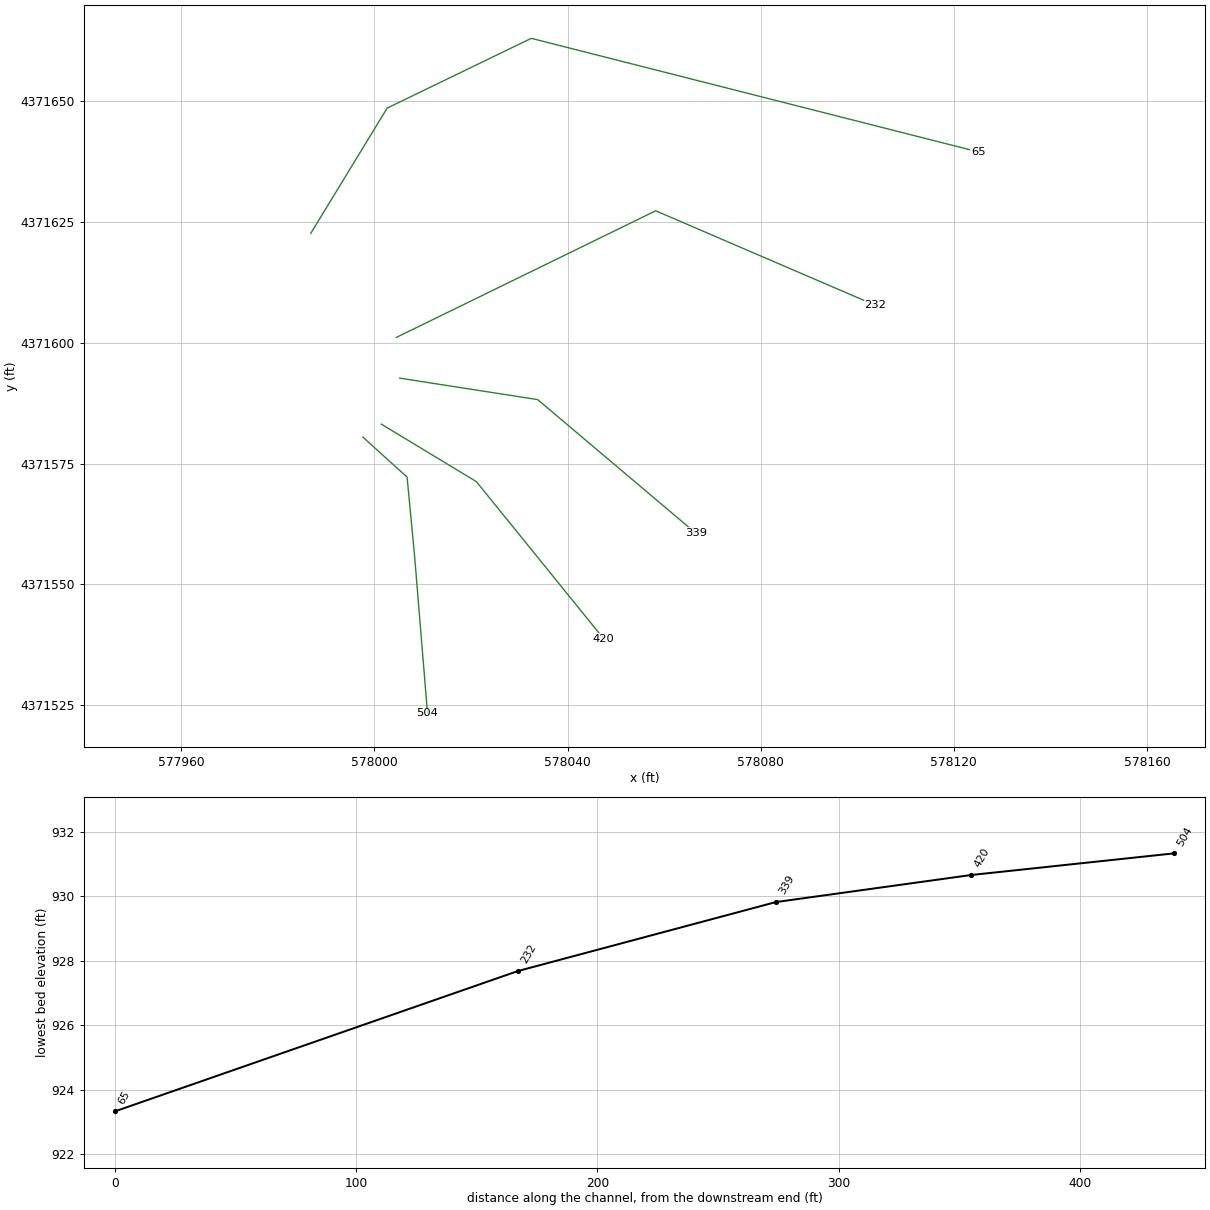
HEC-RAS study ScratchersRun.prj: Scratchers Run

--- ScratchersRun.g01 (geometry) --- (continued)

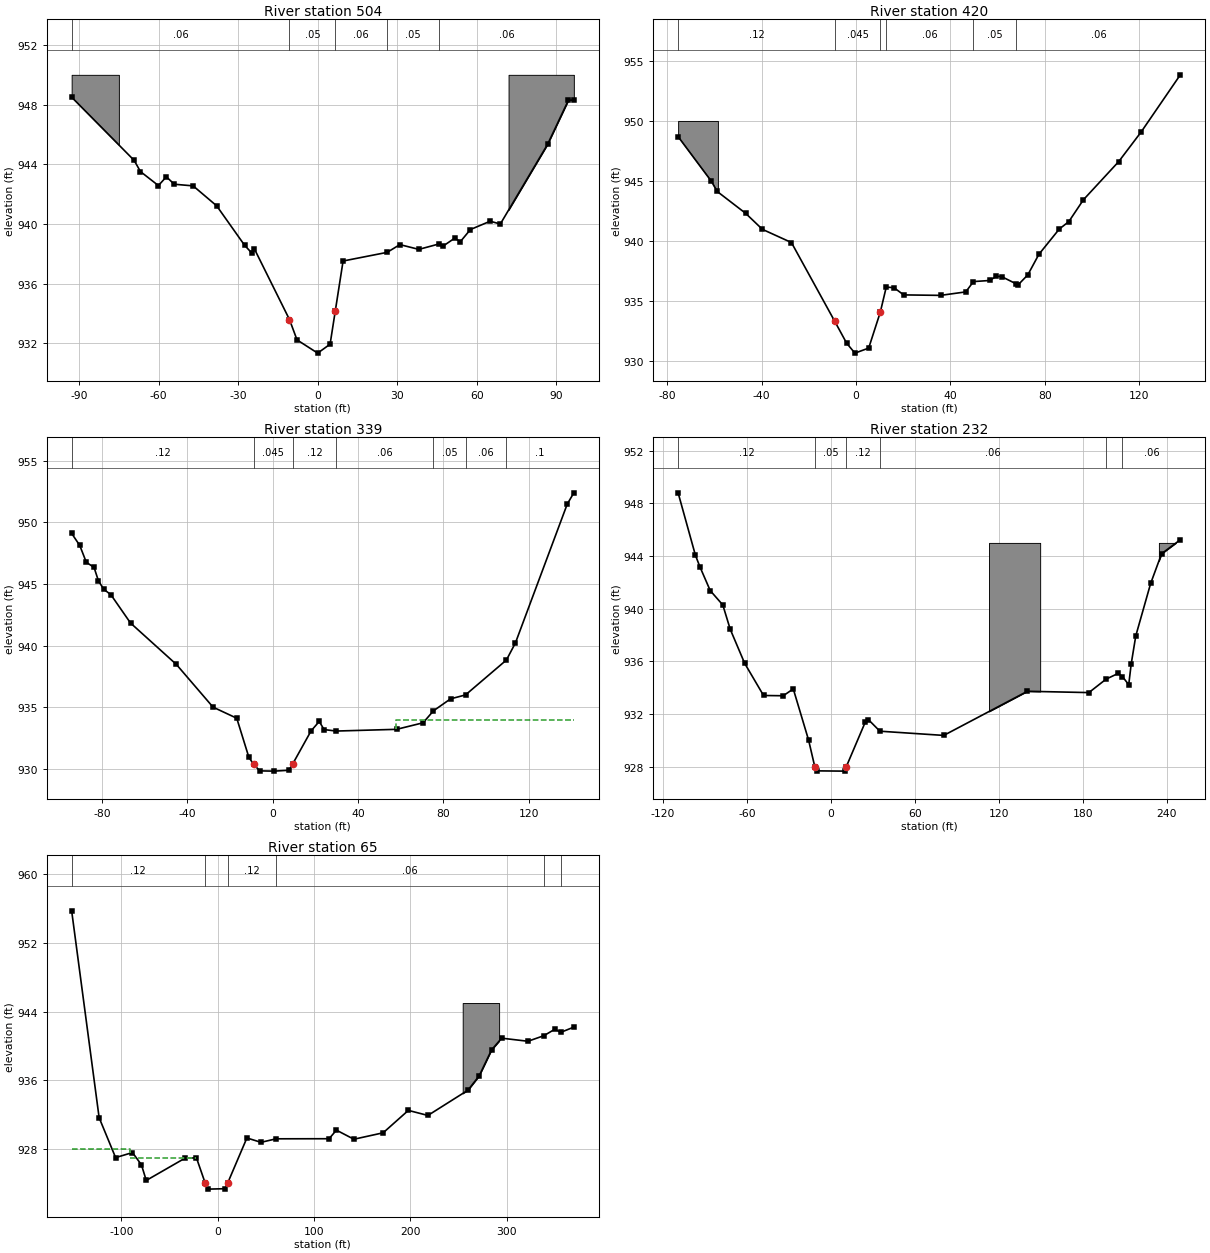
Type RM Length L Ch R = 1 ,504     ,62.36,84,93.4
BEGIN DESCRIPTION:
DS of Private driveway (Channel from survey data SCR_01)
END DESCRIPTION:
XS GIS Cut Line= 4
577997.6238154544371580.46299622578006.7705587674371572.20230652
578008.3015691864371556.14849032 578011.003011624371523.25477872
#Sta/Elev= 30
 -92.828   948.5 -69.244  944.26 -66.869  943.51 -60.088  942.57 -57.097  943.16
 -54.107  942.66 -46.985  942.55 -38.105  941.21 -27.593  938.57 -24.849  938.04
 -23.924  938.34  -10.64 933.582  -7.801  932.22       0  931.33   4.686  931.93
    6.66 934.178   9.587  937.51  26.205  938.09  31.015  938.61  38.167  938.29
  45.906  938.66  47.231   938.5  51.763  939.05  53.798   938.8  57.621  939.62
  65.082  940.18  68.905  939.99  86.724  945.33  94.586  948.29  96.621  948.31
#Mann= 5 ,-1 , 0
 -92.828     .06       0  -10.64     .05       0    6.66     .06       0
  26.205     .05       0  45.906     .06       0
#XS Ineff= 2 , 0
       0                      30       0
Permanent Ineff=
       F       F
#Block Obstruct= 2 ,-1
  72.018  96.651     950 -92.828 -75.009     950
Bank Sta=-10.64,6.66
XS Rating Curve= 0 ,0
Skew Angle= 20
Exp/Cntr=0.5,0.3

Type RM Length L Ch R = 1 ,420     ,71.95,81,89.97
XS GIS Cut Line= 3
578001.4338155014371583.16169546578021.1187141454371571.25529291
 578047.479952074371538.72033091
#Sta/Elev= 30
 -75.394  948.69 -61.253  944.96 -58.858  944.13 -46.752   942.3 -39.665  940.97
 -27.362  939.87      -9 933.308   -3.97  931.49    -.46  930.66   5.381  931.08
  10.302  934.07  12.828  936.16  16.109  936.11   20.21  935.51  35.827  935.47
  46.522  935.76  49.803  936.62   56.66  936.71  59.514  937.06   61.68  937.04
  67.979  936.42  68.832  936.37  72.835  937.18  77.526  938.89  86.188     941
   90.19  941.61  96.424  943.44 111.385  946.62 120.899  949.09 137.467  953.84
#Mann= 6 ,-1 , 0
 -75.394     .12       0      -9    .045       0  10.302     .12       0
  12.828     .06       0  49.803     .05       0  67.979     .06       0
#Block Obstruct= 1 ,-1
 -75.394  -58.53     950
Bank Sta=-9,10.302
XS Rating Curve= 0 ,0
Exp/Cntr=0.3,0.1

Type RM Length L Ch R = 1 ,339     ,86.79,107,170.58
XS GIS Cut Line= 3
578005.2438155484371592.68669557578033.8188159024371588.24149232
578066.5214179064371560.61899198
#Sta/Elev= 30
  -94.16   949.1 -90.354  948.12 -87.303  946.76 -83.661  946.34 -81.627  945.26
 -79.134  944.57 -75.787  944.13 -66.568  941.83 -45.079  938.47  -27.92  935.01
 -16.798  934.11 -11.122  930.94  -8.891  930.37  -6.004  929.84    .722  929.82
   7.677  929.89     9.5 930.429  18.012  933.08   21.85  933.85  24.114  933.19
  29.757  933.07  58.104  933.21  70.505  933.74  75.361  934.71  83.366  935.68
  90.387     936 109.547  938.83  113.78  940.22 138.058  951.48 141.142  952.39
#Mann= 7 ,-1 , 0
  -94.16     .12       0  -8.891    .045       0     9.5     .12       0
  29.757     .06       0  75.361     .05       0  90.387     .06       0
 109.547      .1       0
#XS Ineff= 1 ,-1
      58 141.142     934
Permanent Ineff=
       F
Bank Sta=-8.891,9.5
XS Rating Curve= 0 ,0
Exp/Cntr=0.3,0.1

Type RM Length L Ch R = 1 ,232     ,167.08,167,149.97
XS GIS Cut Line= 3
 578004.537898744371601.11258688578058.266519404  4371627.347028
578103.7749887664371607.76789496
#Sta/Elev= 30
-109.186   948.8  -96.85  944.07 -93.635  943.19 -86.253  941.38 -77.264  940.29
 -71.982  938.45 -61.647  935.86 -48.163  933.42 -34.088   933.4 -26.936  933.92
 -15.978  930.03   -11.5 927.981 -10.335   927.7   9.777  927.68   10.85 927.994
  24.409  931.38  26.706  931.59  34.941  930.71  80.545  930.39 140.289  933.74
 184.219  933.64  196.49  934.66 205.217   935.1 208.202  934.85 212.664  934.24
 214.469  935.84 217.717  937.95 228.314  941.92 236.155  944.18 249.508  945.24
#Mann= 6 ,-1 , 0
-109.186     .12       0   -11.5     .05       0   10.85     .12       0
  34.941     .06       0  196.49     .05       0 208.202     .06       0
#Block Obstruct= 2 ,-1
 112.894 149.409     945 234.219 249.508     945
Bank Sta=-11.5,10.85
XS Rating Curve= 0 ,0
Exp/Cntr=0.3,0.1

Type RM Length L Ch R = 1 ,65      ,54.72,65,89.23
XS GIS Cut Line= 4
577986.8375529214371622.69943755578002.6508819164371648.61962987
578032.4959838854371663.06593084578125.0424090294371639.55853535
#Sta/Elev= 30
-151.772  955.74-123.228  931.65-106.102     927 -88.583  927.59 -79.265  926.16
 -74.278  924.34 -34.252  926.92 -22.146  926.98   -13.2 924.085 -10.367  923.33
   7.972  923.38    10.5 924.088  30.282  929.29  44.882  928.78  60.696  929.19
  115.65   929.2 123.261   930.2 141.437  929.14 171.818  929.89 197.999   932.5
 218.307  931.91 259.875  934.85 271.555  936.52 284.416  939.54 294.915  940.91
 322.244  940.55 338.812   941.2 350.328  941.96 356.201  941.58 369.915   942.2
#Mann= 6 ,-1 , 0
-151.772     .12       0   -13.2    .045       0    10.5     .12       0
  60.696     .06       0 338.812     .05       0 356.201     .06       0
#XS Ineff= 2 ,-1
-151.772  -90.71     928  -90.71  -22.15  926.98
Permanent Ineff=
       F       F
#Block Obstruct= 1 ,-1
 254.462  292.29     945
Bank Sta=-13.2,10.5
XS Rating Curve= 0 ,0
Exp/Cntr=0.3,0.1
Stream Node=Scratchers Run  ,Reach 1         , 0 , 0 ,Upstream end
Stream Node=Scratchers Run  ,Reach 1         , 0 , 1 ,Downstream end

Chan Stop Cuts=-1
Use User Specified Reach Order=0
Composite Channel Slope=5